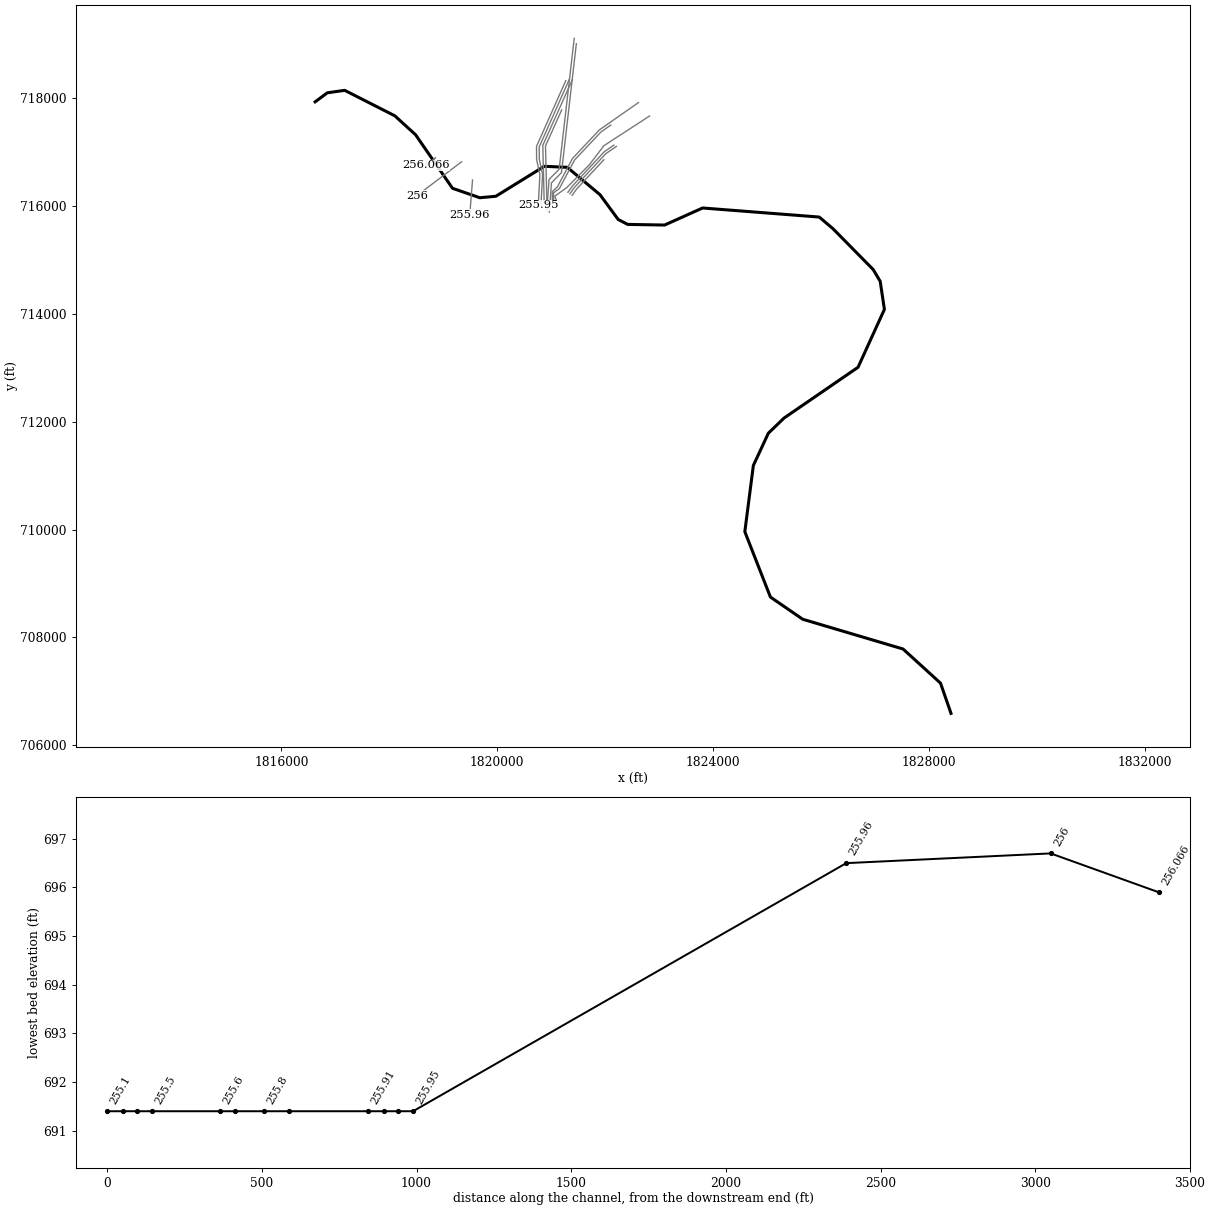
--- FRA-70-1321R.prj (project) ---

Proj Title=FRA-70-1321R
Current Plan=p19
Current HD=h03
Default Exp/Contr=0.3,0.1
English Units
Geom File=g02
Geom File=g05
Geom File=g01
Geom File=g03
Geom File=g11
Geom File=g12
Geom File=g04
Geom File=g06
Geom File=g07
Geom File=g09
Geom File=g08
Geom File=g10
Geom File=g13
Flow File=f02
Flow File=f01
Flow File=f03
Flow File=f04
Flow File=f05
Plan File=p01
Plan File=p03
Plan File=p04
Plan File=p02
Plan File=p09
Plan File=p11
Plan File=p12
Plan File=p13
Plan File=p14
Plan File=p15
Plan File=p16
Plan File=p17
Plan File=p18
Plan File=p19
Plan File=p20
Plan File=p05
Plan File=p06
Plan File=p07
Plan File=p08
HD File=h02
HD File=h03
HD File=h04
Y Axis Title=Elevation
X Axis Title(PF)=Main Channel Distance
X Axis Title(XS)=Station
BEGIN DESCRIPTION:
Scioto Greenways Model (Sciotogreenways.prj)
30% Preliminary Design Model
Model Version: HEC-RAS version 4.1.0
By: Stantec Consulting Services Inc. - Columbus, OH
Project Number: 173408853
Project Name: Scioto Greenways
November 2012
URS Edits December 2013:
Utilize Stantec Pre-Project conditions model and add additional field survey information of existing I-70/I-71 bridge over Scioto River
Plans:
Duplicate Effective - The effective HEC-RAS geometry imported into and shortened to                                                       project area, cross sections are not geo-referenced.
                                 Vertical Datum = NGVD29.
Pre-Project Conditions - The  existing conditions using 2011 LiDAR Data & field survey data.
                                       Vertical Datum = NAVD 88.
Post-Project Conditions - Pre-project channel geometry modified based on proposed conditions                                                  grading plan.
		         VerticalDatum = NAVD 88.
Known WSEL for SPF flood was taken directly from the USACE HEC-2 Model.
END DESCRIPTION:
DSS Export Rating Curves= 0
DSS Export Rating Curve Sorted= 0
DSS Export Volume Flow Curves= 0
DXF Filename=..\..\Working\KAS\USF.dxf
DXF OffsetX= 0
DXF OffsetY= 0
DXF ScaleX= 1
DXF ScaleY= 1

--- FRA-70-1321R.p19 (plan) ---

Plan Title=Prop_Preferred_No-dam_High-N
Program Version=5.06
Geom File=g06
Flow File=f02
Subcritical Flow
K Sum by GR= 0
Std Step Tol= 0.01
Critical Tol= 0.01
Num of Std Step Trials= 20
Max Error Tol= 0.3
Flow Tol Ratio= 0.001
Split Flow NTrial= 30
Split Flow Tol= 0.02
Split Flow Ratio= 0.02
Log Output Level= 0
Friction Slope Method= 1
Unsteady Friction Slope Method= 2
Unsteady Bridges Friction Slope Method= 1
Calc Critical at every XS
Parabolic Critical Depth
Global Vel Dist= 0 , 0 , 0
Global Log Level= 0
CheckData=True
Encroach Param=-1 ,0,0, 0
Computation Interval=1HOUR
Output Interval=1HOUR
Instantaneous Interval=1HOUR
Mapping Interval=1HOUR
Computation Time Step Use Courant=        0
Computation Time Step Use Time Series=    0
Computation Time Step Count To Double=0
Computation Time Step Max Doubling=0
Computation Time Step Max Halving=0
Computation Time Step Residence Courant=0
Run HTab= 0
Run UNet= 0
Run Sediment= 0
Run PostProcess= 0
Run WQNet= 0
Run RASMapper= 0
UNET Theta= 1
UNET Theta Warmup= 1
UNET ZTol= 0.02
UNET ZSATol= 0.05
UNET MxIter= 20
UNET Max Iter WO Improvement= 0
UNET MaxInSteps= 0
UNET DtIC= 0
UNET DtMin= 0
UNET MaxCRTS= 20
UNET WFStab= 2
UNET SFStab= 1
UNET WFX= 1
UNET SFX= 1
UNET 1D Methodology=Finite Difference
UNET DSS MLevel= 4
UNET Pardiso=0
UNET DZMax Abort= 100
UNET Use Existing IB Tables=-1
UNET Froude Reduction=False
UNET Froude Limit= 1
UNET Froude Power= 10
UNET D1 Cores= 0
UNET D2 Coriolis=0
UNET D2 Cores= 0
UNET D2 Theta= 1
UNET D2 Theta Warmup= 1
UNET D2 Z Tol= 0.01
UNET D2 Volume Tol= 0.01
UNET D2 Max Iterations= 20
UNET D2 Equation= 0
UNET D2 RampUpFraction=0.1
UNET D2 TimeSlices= 1
UNET D2 BCVolumeCheck=0
UNET D1D2 MaxIter= 0
UNET D1D2 ZTol=0.01
UNET D1D2 QTol=0.1
UNET D1D2 MinQTol=1
Write IC File= 0
Write IC File at Fixed DateTime=0
Write IC File at Sim End=0
Echo Input=False
Echo Parameters=False
Echo Output=False
Write Detailed= 0
HDF Write Warmup=0
HDF Write Time Slices=0
HDF Flush=0
HDF Face Node Velocities=0
HDF Compression= 1
HDF Chunk Size= 1
HDF Spatial Parts= 1
HDF Use Max Rows=0
HDF Fixed Rows= 1
Calibration Method= 0
Calibration Iterations= 20
Calibration Max Change=0.05
Calibration Tolerance=0.2
Calibration Maximum=1.5
Calibration Minimum=0.5
Calibration Optimization Method= 1
WQ AD Non Conservative
WQ ULTIMATE=-1
WQ Max Comp Step=1HOUR
WQ Output Interval=15MIN
WQ Output Selected Increments= 0
WQ Output face flow=0
WQ Output face velocity=0
WQ Output face area=0
WQ Output face dispersion=0
WQ Output cell volume=0
WQ Output cell surface area=0
WQ Output cell continuity=0
WQ Output cumulative cell continuity=0
WQ Output face conc=0
WQ Output face dconc_dx=0
WQ Output face courant=0
WQ Output face peclet=0
WQ Output face adv mass=0
WQ Output face disp mass=0
WQ Output cell mass=0
WQ Output cell source sink temp=0
WQ Output nsm pathways=0
WQ Output nsm derived pathways=0
WQ Output MaxMinRange=-1
WQ Daily Max Min Mean=-1
WQ Daily Range=0
WQ Daily Time=0
WQ Create Restart=0
WQ Fixed Restart=0
WQ System Summary=0
WQ Write To DSS=0
WQ Use Fixed Temperature=0
Sorting and Armoring Iterations= 10
XS Update Threshold= 0.02
Bed Roughness Predictor= 0
Hydraulics Update Threshold= 0.02
Energy Slope Method= 1
Volume Change Method= 0
Sediment Retention Method= 0
XS Weighting Method= 0
Number of US Weighted Cross Sections= 1
Number of DS Weighted Cross Sections= 1
Upstream XS Weight=0.25
Main XS Weight=0.5
Downstream XS Weight=0.25
Number of DS XS's Weighted with US Boundary= 1
Upstream Boundary Weight= 1
Weight of XSs Associated with US Boundary= 0
Number of US XS's Weighted with DS Boundary= 1
Downstream Boundary Weight= 0.5
Weight of XSs Associated with DS Boundary= 0.5
Percentile Method= 0
Sediment Output Level= 4
Mass or Volume Output= 0
Output Increment Type= 1
Profile and TS Output Increment= 10
XS Output Flag= 0
XS Output Increment= 10
Write Gradation File= 0
Read Gradation Hotstart= 0
Write HDF5 File= 1
Write Binary Output= 1
Write DSS Sediment File= 0
SV Curve= 0
Specific Gage Flag= 0

--- FRA-70-1321R.p01 (plan) ---

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Plan Title=Duplicate_Effective_(Stantec)
Program Version=4.10
Short Identifier=Duplicate
Geom File=g02
Flow File=f01
BEGIN DESCRIPTION:
Duplicate Effective Model - Geometry imported from effective HEC-RAS model. Elevations in NGVD 29
END DESCRIPTION:
UNET Convert EG Bridges= 0
UNET Time Slicing=0,0, 5
UNET Junction Losses=0
WQ Output cell source sink nsm=0
Disregard all LS=0
Disregard all Conn=0
Disregard all Breaches=0
Disregard all Pumps=0

--- FRA-70-1321R.p02 (plan) ---

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Plan Title=Corrected Effective / Existing
Program Version=4.10
Short Identifier=Existing
Geom File=g03
Flow File=f02
Global Vel Dist= 2 , 4 , 2
BEGIN DESCRIPTION:
Pre-project Plan - Includes survey elevations for existing 70/71 bridge low chord.  Channel geometry based on 2011 bathymetric survey by Resouce International. Overbank geometry based on 2011 topographic survey by Resource International and 2011 City of Columbus LiDAR data.
Vertical Datum = NAVD 88.
Projection = State Plane Ohio South
END DESCRIPTION:
UNET Convert EG Bridges= 0
UNET Time Slicing=0,0, 5
UNET Junction Losses=0
DSS File=dss
WQ Output cell source sink nsm=0
Disregard all LS=0
Disregard all Conn=0
Disregard all Breaches=0
Disregard all Pumps=0

--- FRA-70-1321R.p03 (plan) ---

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Plan Title=Post-Project_(Stantec)
Program Version=4.10
Short Identifier=PostProjStantec
Geom File=g01
Flow File=f02
Global Vel Dist= 2 , 4 , 2
BEGIN DESCRIPTION:
Post Project - Pre-project channel geometry modified based on proposed conditions grading plan.
Vertical Datum = NAVD 88.
Projection = State Plane Ohio South
END DESCRIPTION:
UNET Convert EG Bridges= 0
UNET Time Slicing=0,0, 5
UNET Junction Losses=0
WQ Output cell source sink nsm=0
Disregard all LS=0
Disregard all Conn=0
Disregard all Breaches=0
Disregard all Pumps=0

--- FRA-70-1321R.p04 (plan) ---

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Plan Title=Corrected Effective / Pre-projectStantec
Program Version=4.10
Short Identifier=Pre-PrjctStantec
Geom File=g05
Flow File=f02
Global Vel Dist= 2 , 4 , 2
BEGIN DESCRIPTION:
Pre-project Plan - Channel geometry based on 2011 bathymetric survey by Resouce International. Overbank geometry based on 2011 topographic survey by Resource International and 2011 City of Columbus LiDAR data.
Vertical Datum = NAVD 88.
Projection = State Plane Ohio South
END DESCRIPTION:
UNET Convert EG Bridges= 0
UNET Time Slicing=0,0, 5
UNET Junction Losses=0
DSS File=dss
WQ Output cell source sink nsm=0
Disregard all LS=0
Disregard all Conn=0
Disregard all Breaches=0
Disregard all Pumps=0

--- FRA-70-1321R.p05 (plan) ---

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Plan Title=FRA-70-1321R - 5 bridges - Scioto River
Program Version=4.10
Short Identifier=FRA-70-1321R
Geom File=g13
Flow File=f01
BEGIN DESCRIPTION:
Duplicate Effective Model - Geometry imported from effective HEC-RAS model. Elevations in NGVD 29
END DESCRIPTION:
UNET Convert EG Bridges= 0
UNET Time Slicing=0,0, 5
UNET Junction Losses=0
WQ Output cell source sink nsm=0
Disregard all LS=0
Disregard all Conn=0
Disregard all Breaches=0
Disregard all Pumps=0

--- FRA-70-1321R.p06 (plan) ---

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Plan Title=Prpsd_Cndtn_1_without_dam
Program Version=4.10
Short Identifier=PC1_wo_dam
Geom File=g08
Flow File=f02
BEGIN DESCRIPTION:
Duplicate Effective Model - Geometry imported from effective HEC-RAS model. Elevations in NGVD 29
END DESCRIPTION:
UNET Convert EG Bridges= 0
UNET Time Slicing=0,0, 5
UNET Junction Losses=0
WQ Output cell source sink nsm=0
Disregard all LS=0
Disregard all Conn=0
Disregard all Breaches=0
Disregard all Pumps=0

--- FRA-70-1321R.p07 (plan) ---

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Plan Title=Prpsd_Cndtn_2_without_dam
Program Version=4.10
Short Identifier=PC2_wo-dam
Geom File=g10
Flow File=f02
UNET Convert EG Bridges= 0
UNET Time Slicing=0,0, 5
UNET Junction Losses=0
WQ Output cell source sink nsm=0
Disregard all LS=0
Disregard all Conn=0
Disregard all Breaches=0
Disregard all Pumps=0

--- FRA-70-1321R.p08 (plan) ---

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Plan Title=Corrected_Effective_Existing_ODOT
Program Version=4.10
Short Identifier=CrctdEfctvExODOT
Geom File=g13
Flow File=f02
UNET Convert EG Bridges= 0
UNET Time Slicing=0,0, 5
UNET Junction Losses=0
WQ Output cell source sink nsm=0
Disregard all LS=0
Disregard all Conn=0
Disregard all Breaches=0
Disregard all Pumps=0

--- FRA-70-1321R.p09 (plan) ---

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Plan Title=Prop_5_span_prof2_ms_optional
Program Version=4.10
Short Identifier=ms_optional
Geom File=g09
Flow File=f02
UNET Convert EG Bridges= 0
UNET Time Slicing=0,0, 5
UNET Junction Losses=0
WQ Output cell source sink nsm=0
Disregard all LS=0
Disregard all Conn=0
Disregard all Breaches=0
Disregard all Pumps=0

--- FRA-70-1321R.p11 (plan) ---

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Plan Title=Prpsd_Cndtn_3_Prfrrd_without_dam
Short Identifier=PC3_wo-dam
Geom File=g12
Flow File=f02

--- FRA-70-1321R.p12 (plan) ---

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Plan Title=Ordinary_High_Water
Program Version=4.10
Short Identifier=OHW
Geom File=g12
Flow File=f03
UNET Convert EG Bridges= 0
UNET Time Slicing=0,0, 5
UNET Junction Losses=0
WQ Output cell source sink nsm=0
Disregard all LS=0
Disregard all Conn=0
Disregard all Breaches=0
Disregard all Pumps=0

--- FRA-70-1321R.f02 (steady flow) ---

Flow Title=Preproject_Flow
Program Version=4.10
Number of Profiles= 5
Profile Names=100-Year,10-Year,50-Year,500-Year,SPF
River Rch & RM=SciotoRiver,SciotoRiver     ,256.066
   57000   28900   47500   87000   87468
River Rch & RM=SciotoRiver,SciotoRiver     ,253.6
   75000   36800   62100  114000  110000
Boundary for River Rch & Prof#=SciotoRiver,SciotoRiver     , 1
Up Type= 0
Dn Type= 1
Dn Known WS=714.3933
Boundary for River Rch & Prof#=SciotoRiver,SciotoRiver     , 2
Up Type= 0
Dn Type= 1
Dn Known WS=707.0744
Boundary for River Rch & Prof#=SciotoRiver,SciotoRiver     , 3
Up Type= 0
Dn Type= 1
Dn Known WS=712.2988
Boundary for River Rch & Prof#=SciotoRiver,SciotoRiver     , 4
Up Type= 0
Dn Type= 1
Dn Known WS=718.8723
Boundary for River Rch & Prof#=SciotoRiver,SciotoRiver     , 5
Up Type= 0
Dn Type= 1
Dn Known WS=718.71
DSS Import GetInterval= 0
DSS Import GetPeak= 0
DSS Import FillOption= 0

--- FRA-70-1321R.f01 (steady flow) ---

Flow Title=DuplicateEffective
Program Version=4.10
Number of Profiles= 5
Profile Names=100-Year,10-Year,50-Year,500-Year,SPF
River Rch & RM=SciotoRiver,SciotoRiver     ,256.066
   57000   28900   47500   87000   87468
River Rch & RM=SciotoRiver,SciotoRiver     ,253.6
   75000   36800   62100  114000  110000
Boundary for River Rch & Prof#=SciotoRiver,SciotoRiver     , 1
Up Type= 0
Dn Type= 1
Dn Known WS=714.9933
Boundary for River Rch & Prof#=SciotoRiver,SciotoRiver     , 2
Up Type= 0
Dn Type= 1
Dn Known WS=707.6744
Boundary for River Rch & Prof#=SciotoRiver,SciotoRiver     , 3
Up Type= 0
Dn Type= 1
Dn Known WS=712.8988
Boundary for River Rch & Prof#=SciotoRiver,SciotoRiver     , 4
Up Type= 0
Dn Type= 1
Dn Known WS=719.4723
Boundary for River Rch & Prof#=SciotoRiver,SciotoRiver     , 5
Up Type= 0
Dn Type= 1
Dn Known WS=719.31
DSS Import GetInterval= 0
DSS Import GetPeak= 0
DSS Import FillOption= 0

--- FRA-70-1321R.f03 (steady flow) ---

Flow Title=Ordinary_High_Water
Program Version=4.10
Number of Profiles= 1
Profile Names=PF 1
River Rch & RM=SciotoRiver,SciotoRiver     ,256.066
    3130
Boundary for River Rch & Prof#=SciotoRiver,SciotoRiver     , 1
Up Type= 0
Dn Type= 1
Dn Known WS=696.5
DSS Import GetInterval= 0
DSS Import GetPeak= 0
DSS Import FillOption= 0

--- FRA-70-1321R.f04 (steady flow) ---

Flow Title=Normal_Water
Program Version=4.10
Number of Profiles= 1
Profile Names=PF 1
River Rch & RM=SciotoRiver,SciotoRiver     ,256.066
    6260
Boundary for River Rch & Prof#=SciotoRiver,SciotoRiver     , 1
Up Type= 0
Dn Type= 1
Dn Known WS=696.5
DSS Import GetInterval= 0
DSS Import GetPeak= 0
DSS Import FillOption= 0

--- FRA-70-1321R.f05 (steady flow) ---

Flow Title=OHW_698-3
Program Version=4.10
Number of Profiles= 1
Profile Names=PF 1
River Rch & RM=SciotoRiver,SciotoRiver     ,256.066
   19500
Boundary for River Rch & Prof#=SciotoRiver,SciotoRiver     , 1
Up Type= 0
Dn Type= 1
Dn Known WS=696.5
DSS Import GetInterval= 0
DSS Import GetPeak= 0
DSS Import FillOption= 0

--- FRA-70-1321R.g06 (geometry) ---

Geom Title=Prpsd_Cndtn_3_Prfrrd_wo_dam_with _High-
Program Version=4.10
BEGIN GEOM DESCRIPTION:
Vertical Datum = NAVD 88
Projection = State Plane Ohio South
END GEOM DESCRIPTION:

River Reach=SciotoRiver     ,SciotoRiver
Reach XY= 30
1816626.45005803717921.0800985251816851.00013386718088.000040263
1817174.00014402718133.9999482631818101.99992844717661.999908015
1818486.00014469717311.9999518541819170.00008902716319.999967352
1819676.00006127716144.9999892711819973.00012344716171.999935269
1820869.99996985716727.000137597 1821296.0001021716707.999847516
1821900.99987637716201.9998752771822238.99985653715742.000139102
1822414.00016269715650.9999930261823098.00010702715639.000017017
1823802.00001135715955.0000411871825961.99995644715787.000049099
1826217.00010261 715571.000153021826961.99992494714814.000026599
1827090.99999502714597.0001325161827168.99983902714076.999860182
1826681.00015886713005.0000356881825310.53013077712064.600013599
1825019.99987194711783.9998530151824742.00009985711186.000064775
1824584.00008777709959.9998921011825058.00012402708749.000017524
1825655.99991228708337.9998552651827514.00013328707786.999973014
1828208.00005761 707154.999924691828402.37991819706594.659838021

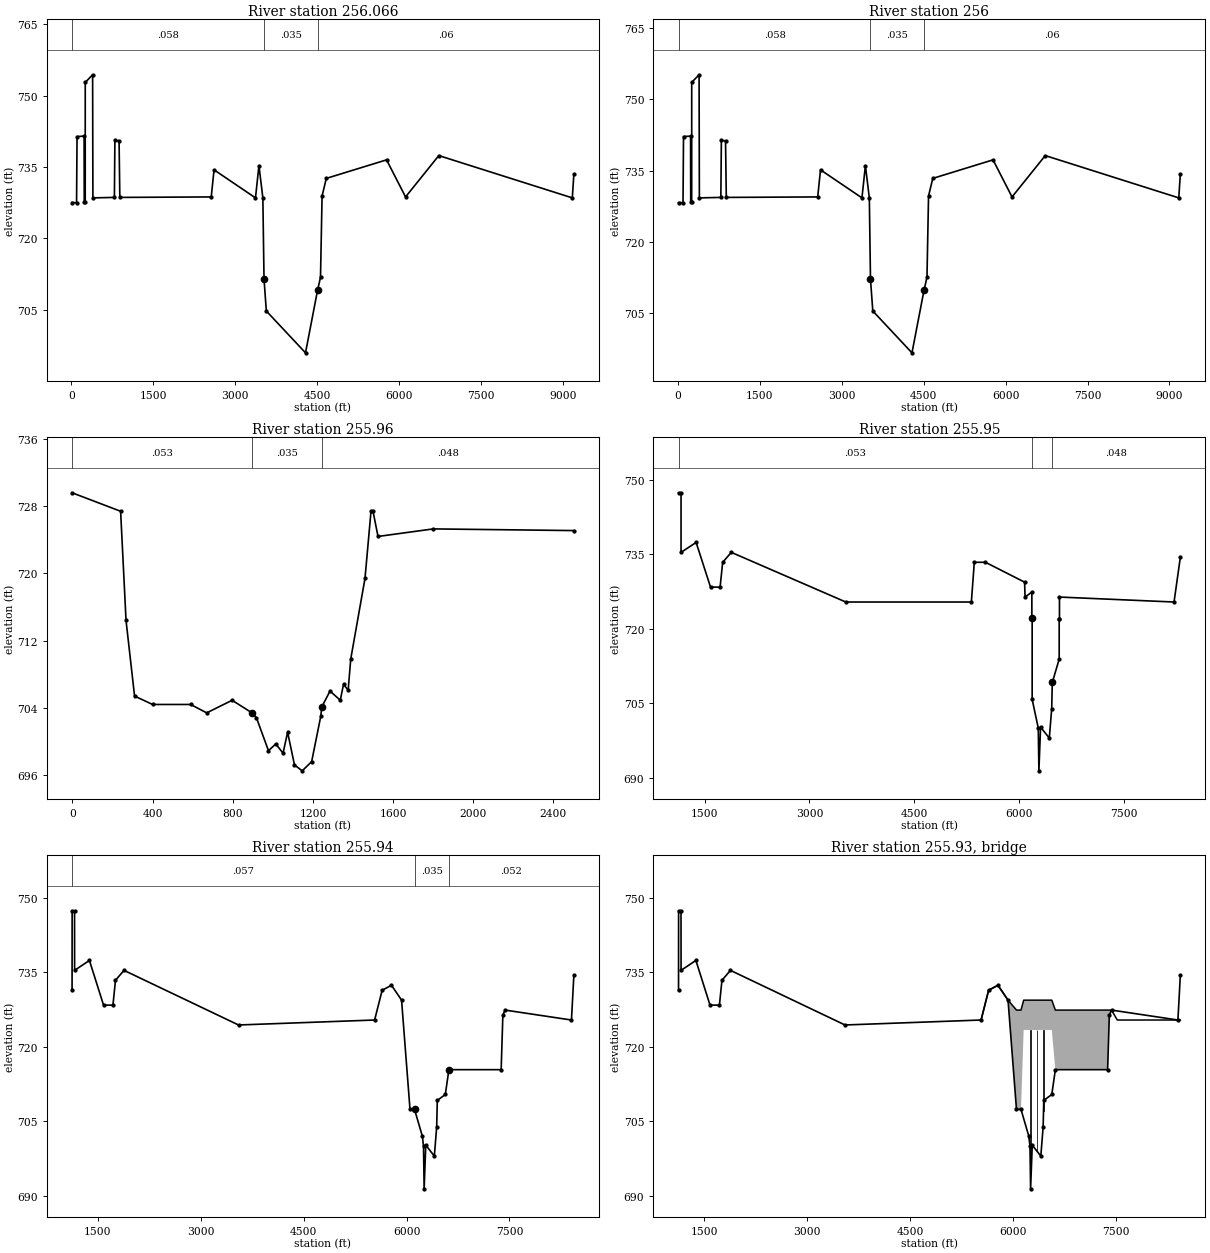
Type RM Length L Ch R = 1 ,256.066 ,350,350,350
BEGIN DESCRIPTION:
Sect. 256 Copied Upstream 350' and adjusted vertically for Splitflow Analysis
END DESCRIPTION:
XS GIS Cut Line= 2
   1818856.66607   716884.761305 1818676.6893958  716748.5125617
#Sta/Elev= 30
    15.4   727.5    97.6   727.5   106.5   741.4   235.6   741.5   238.4   727.7
     256   727.7   256.7   752.8   391.4   754.4   396.7   728.5   789.9   728.6
   799.1   740.6   875.5   740.5   889.6   728.6  2562.2   728.7  2613.8   734.4
  3372.1   728.5  3435.2   735.3    3507   728.5  3528.2   711.4  3570.6   704.7
  4287.5   695.9  4508.5   709.1  4561.9   711.8  4590.7   728.9  4668.2   732.6
  5770.6   736.5  6118.5   728.7    6727   737.4  9170.2   728.5  9198.5   733.5
#Mann= 3 , 0 , 0
    15.4    .058       0  3528.2    .035       0  4508.5     .06       0
#Block Obstruct= 2 , 0
                            4900
Bank Sta=3528.2,4508.5
XS Rating Curve= 0 ,0
Exp/Cntr=0.3,0.1

Type RM Length L Ch R = 1 ,256     ,660.8,660.8,660.8
XS GIS Cut Line= 2
  1819340.051586  716811.7194563 1818509.9781151  716183.3240596
#Sta/Elev= 30
    15.4   728.3    97.6   728.3   106.5   742.2   235.6   742.3   238.4   728.5
     256   728.5   256.7   753.6   391.4   755.2   396.7   729.3   789.9   729.4
   799.1   741.4   875.5   741.3   889.6   729.4  2562.2   729.5  2613.8   735.2
  3372.1   729.3  3435.2   736.1    3507   729.3  3528.2   712.2  3570.6   705.5
  4287.5   696.7  4508.5   709.9  4561.9   712.6  4590.7   729.7  4668.2   733.4
  5770.6   737.3  6118.5   729.5    6727   738.2  9170.2   729.3  9198.5   734.3
#Mann= 3 , 0 , 0
    15.4    .058       0  3528.2    .035       0  4508.5     .06       0
#Block Obstruct= 2 , 0
                            4900
Bank Sta=3528.2,4508.5
XS Rating Curve= 0 ,0
Exp/Cntr=0.3,0.1

Type RM Length L Ch R = 1 ,255.96  ,1400.37,1400.37,1400.37
XS GIS Cut Line= 2
  1819541.408795  716474.3165878 1819490.1129658  715831.6000255
#Sta/Elev= 30
    -1.9   729.6   240.4   727.4   267.4   714.4     310   705.4     400   704.4
     590   704.4     670   703.4   796.9   704.9   896.2   703.4   918.5   702.8
   978.3   698.9  1014.8   699.7  1051.1   698.6  1073.8   701.1  1108.1   697.2
  1146.7   696.5  1193.8   697.6  1239.3     703  1244.4   704.1  1285.4     706
  1336.7   704.9  1352.8   706.8    1376   706.1  1388.8   709.8    1460   719.4
    1490   727.4    1500   727.4    1525   724.4  1800.9   725.3  2502.4   725.1
#Mann= 3 , 0 , 0
    -1.9    .053       0   896.2    .035       0  1244.4    .048       0
#Block Obstruct= 2 , 0
                            1330
Bank Sta=896.2,1244.4
XS Rating Curve= 0 ,0
Exp/Cntr=0.3,0.1

Type RM Length L Ch R = 1 ,255.95  ,50,50,50
XS GIS Cut Line= 5
  1821267.974895  718313.5153372 1820725.9293918  717095.3268287
 1820727.7902805  716853.6658947 1820788.6366155  716571.5306322
 1820758.1632512  716002.6892502
#Sta/Elev= 30
    1125   747.4    1161   747.4    1161   735.4    1377   737.4    1583   728.4
    1720   728.4    1757   733.4    1881   735.4    3520   725.4    5318   725.4
    5360   733.4    5520   733.4    6080   729.4    6087   726.4    6184   727.4
    6184   722.1  6188.5   722.1  6188.5   705.8    6276     700  6284.9   691.4
    6309   700.2    6434     698  6468.1   703.9  6476.9   709.2  6575.5   713.9
  6575.5     722  6579.5     722  6579.5   726.4    8220   725.4    8310   734.4
#Mann= 3 , 0 , 0
    1125    .053       0  6188.5    .035       0  6476.9    .048       0
#Block Obstruct= 2 , 0
                            6638
Bank Sta=6188.5,6476.9
XS Rating Curve= 0 ,0
Exp/Cntr=0.3,0.1

Type RM Length L Ch R = 1 ,255.94  ,45.5,45.5,45.5
BEGIN DESCRIPTION:
I-670 Ramp (Upstream) Crossing #1 - Upstream Section
END DESCRIPTION:
XS GIS Cut Line= 5
  1821334.393069  718339.7912033 1820776.0113126  717084.8888575
 1820777.7491701   716859.186553 1820838.9229322  716575.5342331
 1820808.0916291  716000.0143868
#Sta/Elev= 30
    1124   731.4    1125   747.4    1160   747.4    1161   735.4    1377   737.4
    1583   728.4    1720   728.4    1757   733.4    1881   735.4    3551   724.4
    5535   725.4    5645   731.4    5781   732.4    5928   729.4    6051   707.4
    6117   707.4    6231     702    6248     700    6257   691.4    6281   700.2
    6406     698    6440   703.9    6449   709.2    6566   710.4    6618   715.4
    7380   715.4    7405   726.4    7437   727.4    8405   725.4    8440   734.4
#Mann= 3 , 0 , 0
    1124    .057       0    6117    .035       0    6618    .052       0
#Block Obstruct= 2 , 0
                            6950
Bank Sta=6117,6618
XS Rating Curve= 0 ,0
Exp/Cntr=0.3,0.1

Type RM Length L Ch R = 3 ,255.93  ,,,
BEGIN DESCRIPTION:
Structure #17 Interstate 670 Ramp Bridge (upstream), Crossing #1
END DESCRIPTION:
Bridge Culvert--1,0,-1,-1, 0
Deck Dist Width WeirC Skew NumUp NumDn MinLoCord MaxHiCord MaxSubmerge Is_Ogee
1,43,2.6,0, 15, 13, 727.4, , 0.95, 0, 0,0,,
    5535    5645    5781    5928    6051    6117    6156    6566    6618    6959
    7380    7405    7437    7521    8440
   725.4   731.4   732.4   729.4   727.4   727.4   729.4   729.4   727.4   727.4
   727.4   727.4   727.4   725.4   725.4
   725.4   731.4   732.4   729.4   707.4   707.4   723.4   723.4   715.4   715.4
   715.4   726.4   727.4   725.4   725.4
    5535    5956    6017    6083    6122    6532    6584    6925    7346    7371
    7437    7521    8440
   725.4   726.4   727.4   727.4   729.4   729.4   727.4   727.4   727.4   727.4
   727.4   725.4   725.4
   725.4   726.4   707.4   707.4   723.4   723.4   715.4   715.4   715.4   726.4
   727.4   725.4   725.4
Pier Skew, UpSta & Num, DnSta & Num=  ,6252.5, 2 ,6218.5, 2 , 0 , 0 , 0 ,,
       9       9
   691.4   723.4
       9       9
   691.4   723.4
Pier Skew, UpSta & Num, DnSta & Num=  ,6348.5, 2 ,6314.5, 2 , 0 , 0 , 0 ,,
       9       9
   697.5   723.4
       9       9
   697.5   723.4
Pier Skew, UpSta & Num, DnSta & Num=  ,6445.5, 2 ,6411.5, 2 , 0 , 0 , 0 ,,
       9       9
   703.9   723.4
       9       9
   703.9   723.4
BR Coef=-1 , 0 , 0 ,, 0 ,,,0.8,-1,,0,
WSPro=,,,, 1 ,,,, 0 ,,,, 0 ,,,,-1 ,-1 ,-1 , 0 , 0 , 0 , 0 , 0
BC Design=,, 0 ,, 0 ,,,,,,
BC HTab HWMax=747.4
BC Use User HTab Curves=0
BC User HTab FreeFlow(D)= 0

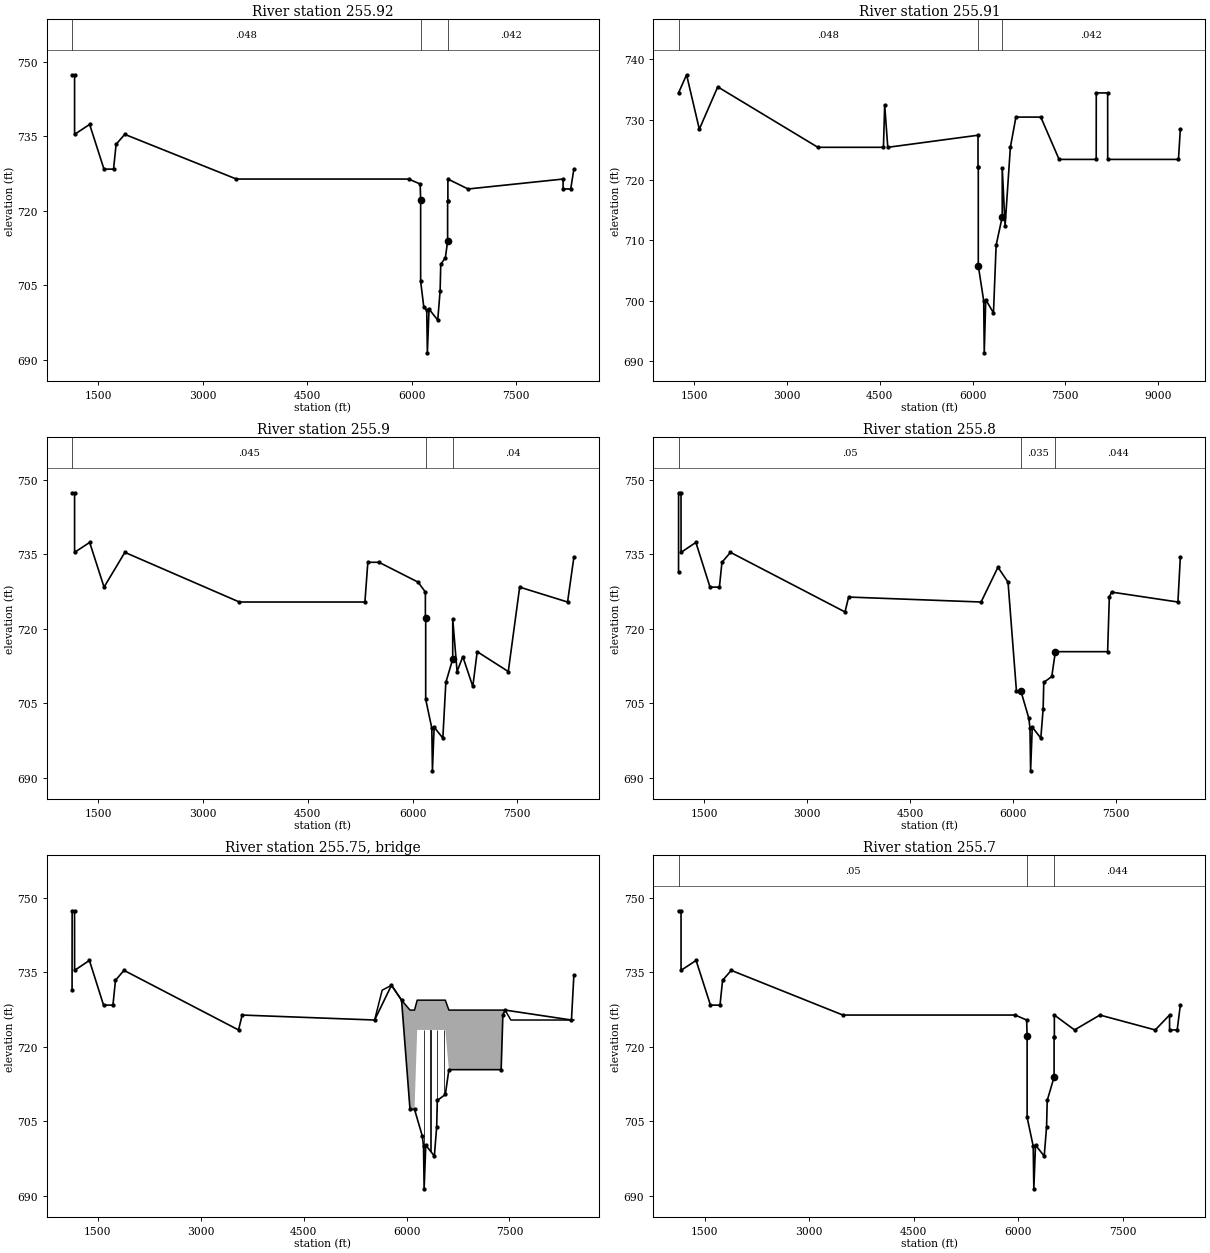
Type RM Length L Ch R = 1 ,255.92  ,50,50,50
BEGIN DESCRIPTION:
I-670 Ramp (Upstream) Crossing #1 - Downstream Section
END DESCRIPTION:
XS GIS Cut Line= 3
   1821390.72629  718333.3440377 1820842.3812586  717114.6207534
 1820868.6436733  716047.6947376
#Sta/Elev= 30
    1125   747.4    1161   747.4    1161   735.4    1377   737.4    1583   728.4
    1720   728.4    1757   733.4    1881   735.4    3483   726.4    5955   726.4
    6120   725.4  6126.5   722.1  6126.5   705.8    6172   700.6    6214     700
    6223   691.4    6247   700.2    6372     698    6406   703.9    6415   709.2
    6482   710.6  6513.5   713.9  6513.5     722  6517.5     722  6517.5   726.4
    6807   724.4    8170   726.4    8171   724.4    8280   724.4    8325   728.4
#Mann= 3 , 0 , 0
    1125    .048       0  6126.5    .035       0  6513.5    .042       0
#Block Obstruct= 2 , 0
                            6638
Bank Sta=6126.5,6513.5
XS Rating Curve= 0 ,0
Exp/Cntr=0.3,0.1

Type RM Length L Ch R = 1 ,255.91  ,255.6,255.6,255.6
XS GIS Cut Line= 3
  1821192.551818  717771.0341387 1820892.6459219  717104.4787133
 1820918.6288096  716048.9250501
#Sta/Elev= 30
    1247   734.4    1377   737.4    1583   728.4    1881   735.4    3500   725.4
    4560   725.4    4580   732.4    4630   725.4    6089   727.4    6089   722.1
  6093.5   722.1  6093.6   705.8    6181     700  6189.9   691.4    6214   700.2
    6339     698  6381.9   709.2  6480.5   713.9  6480.5     722    6527   712.4
    6612   725.4    6702   730.4    7104   730.4    7400   723.4    8000   723.4
    8001   734.4    8185   734.4    8186   723.4    9330   723.4    9360   728.4
#Mann= 3 , 0 , 0
    1247    .048       0  6093.6    .035       0  6480.5    .042       0
#Block Obstruct= 2 , 0
                            6638
Bank Sta=6093.6,6480.5
XS Rating Curve= 0 ,0
Exp/Cntr=0.3,0.1

Type RM Length L Ch R = 1 ,255.9   ,80.77,80.77,80.77
BEGIN DESCRIPTION:
AN
END DESCRIPTION:
Node Name=AN
XS GIS Cut Line= 4
  1821424.409622  719097.1568146 1821144.8822941  716673.5927641
 1820957.7018941  716481.7522685 1820917.3213975  715912.8124615
#Sta/Elev= 30
    1125   747.4    1161   747.4    1161   735.4    1377   737.4    1583   728.4
    1881   735.4    3520   725.4    5318   725.4    5360   733.4    5520   733.4
    6080   729.4    6184   727.4    6184   722.1  6188.5   722.1  6188.5   705.8
    6276     700  6284.9   691.4    6309   700.2    6434     698  6476.9   709.2
  6575.5   713.9  6575.5     722    6638   711.4    6720   714.4    6863   708.4
    6926   715.4    7371   711.4    7534   728.4    8220   725.4    8310   734.4
#Mann= 3 , 0 , 0
    1125    .045       0  6188.5    .035       0  6575.5     .04       0
#Block Obstruct= 2 , 0
                            6638
Bank Sta=6188.5,6575.5
XS Rating Curve= 0 ,0
Exp/Cntr=0.3,0.1

Type RM Length L Ch R = 1 ,255.8   ,92.5,92.5,92.5
BEGIN DESCRIPTION:
I-670 East/West Crossing #1 - Upstream Section
END DESCRIPTION:
XS GIS Cut Line= 4
  1821463.897404  718998.7311584 1821188.3982831  716610.0833766
 1821002.6135497  716419.6733244 1820964.3278651  715880.2452694
#Sta/Elev= 30
    1124   731.4    1125   747.4    1160   747.4    1161   735.4    1377   737.4
    1583   728.4    1720   728.4    1757   733.4    1881   735.4    3551   723.4
    3604   726.4    5535   725.4    5781   732.4    5928   729.4    6051   707.4
    6117   707.4    6231     702    6248     700    6257   691.4    6281   700.2
    6406     698    6440   703.9    6449   709.2    6566   710.4    6618   715.4
    7380   715.4    7405   726.4    7437   727.4    8405   725.4    8440   734.4
#Mann= 3 , 0 , 0
    1124     .05       0    6117    .035       0    6618    .044       0
#Block Obstruct= 2 , 0
                            6900
Bank Sta=6117,6618
XS Rating Curve= 0 ,0
Exp/Cntr=0.3,0.1

Type RM Length L Ch R = 3 ,255.75  ,,,
BEGIN DESCRIPTION:
Structure #16 Interstate 670 Bridge, Crossing #1
END DESCRIPTION:
Bridge Culvert--1,0,-1,-1, 0
Deck Dist Width WeirC Skew NumUp NumDn MinLoCord MaxHiCord MaxSubmerge Is_Ogee
1,90,2.6,0, 15, 13, 727.4, , 0.95, 0, 0,0,,
    5535    5645    5781    5928    6051    6117    6156    6566    6618    6959
    7380    7405    7437    7521    8440
   725.4   731.4   732.4   729.4   727.4   727.4   729.4   729.4   727.4   727.4
   727.4   727.4   727.4   725.4   725.4
   725.4   731.4   732.4   729.4   707.4   707.4   723.4   723.4   715.4   715.4
   715.4   726.4   727.4   725.4   725.4
    5535    5928    6017    6083    6122    6532    6584    6925    7346    7371
    7437    7521    8440
   725.4   725.4   727.4   727.4   729.4   729.4   727.4   727.4   727.4   727.4
   727.4   725.4   725.4
   725.4   725.4   707.4   707.4   723.4   723.4   715.4   715.4   715.4   726.4
   727.4   725.4   725.4
Pier Skew, UpSta & Num, DnSta & Num=  ,6252.5, 2 ,6218.5, 2 , 0 , 0 , 0 ,,
       9       9
   691.4   723.4
       9       9
   691.4   723.4
Pier Skew, UpSta & Num, DnSta & Num=  ,6348.5, 2 ,6314.5, 2 , 0 , 0 , 0 ,,
       9       9
   697.5   723.4
       9       9
   697.5   723.4
Pier Skew, UpSta & Num, DnSta & Num=  ,6445.5, 2 ,6411.5, 2 , 0 , 0 , 0 ,,
       9       9
   703.9   723.4
       9       9
   703.9   723.4
Pier Skew, UpSta & Num, DnSta & Num=  ,6549.5, 2 ,6515, 2 , 0 , 0 , 0 ,,
       4       4
   713.9   723.6
       3       3
   713.9   723.6
BR Coef=-1 , 0 , 0 ,, 0 ,,,0.8,-1,,0,
WSPro=,,,, 1 ,,,, 0 ,,,, 0 ,,,,-1 ,-1 ,-1 , 0 , 0 , 0 , 0 , 0
BC Design=,, 0 ,, 0 ,,,,,,
BC HTab HWMax=747.4
BC Use User HTab Curves=0
BC User HTab FreeFlow(D)= 0

Type RM Length L Ch R = 1 ,255.7   ,50,50,50
BEGIN DESCRIPTION:
I-670 East/West Crossing #1 - Downstream Section
END DESCRIPTION:
XS GIS Cut Line= 6
  1822614.656257  717907.6221201 1821891.3676777  717402.1910444
 1821393.5254976  716873.2249107 1821113.4633936  716347.7722215
 1821016.6535479  716257.0811299 1821020.0098404  716095.9876201
#Sta/Elev= 30
    1125   747.4    1161   747.4    1161   735.4    1377   737.4    1583   728.4
    1720   728.4    1757   733.4    1881   735.4    3483   726.4    5955   726.4
    6120   725.4  6126.5   722.1  6126.5   705.8    6214     700    6223   691.4
    6247   700.2    6372     698    6406   703.9    6415   709.2  6513.5   713.9
  6513.5     722  6517.5     722  6517.5   726.4    6807   723.4    7171   726.4
    7965   723.4    8170   726.4    8171   723.4    8280   723.4    8325   728.4
#Mann= 3 , 0 , 0
    1125     .05       0  6126.5    .035       0  6513.5    .044       0
#Block Obstruct= 2 , 0
                            6638
Bank Sta=6126.5,6513.5
XS Rating Curve= 0 ,0
Exp/Cntr=0.3,0.1

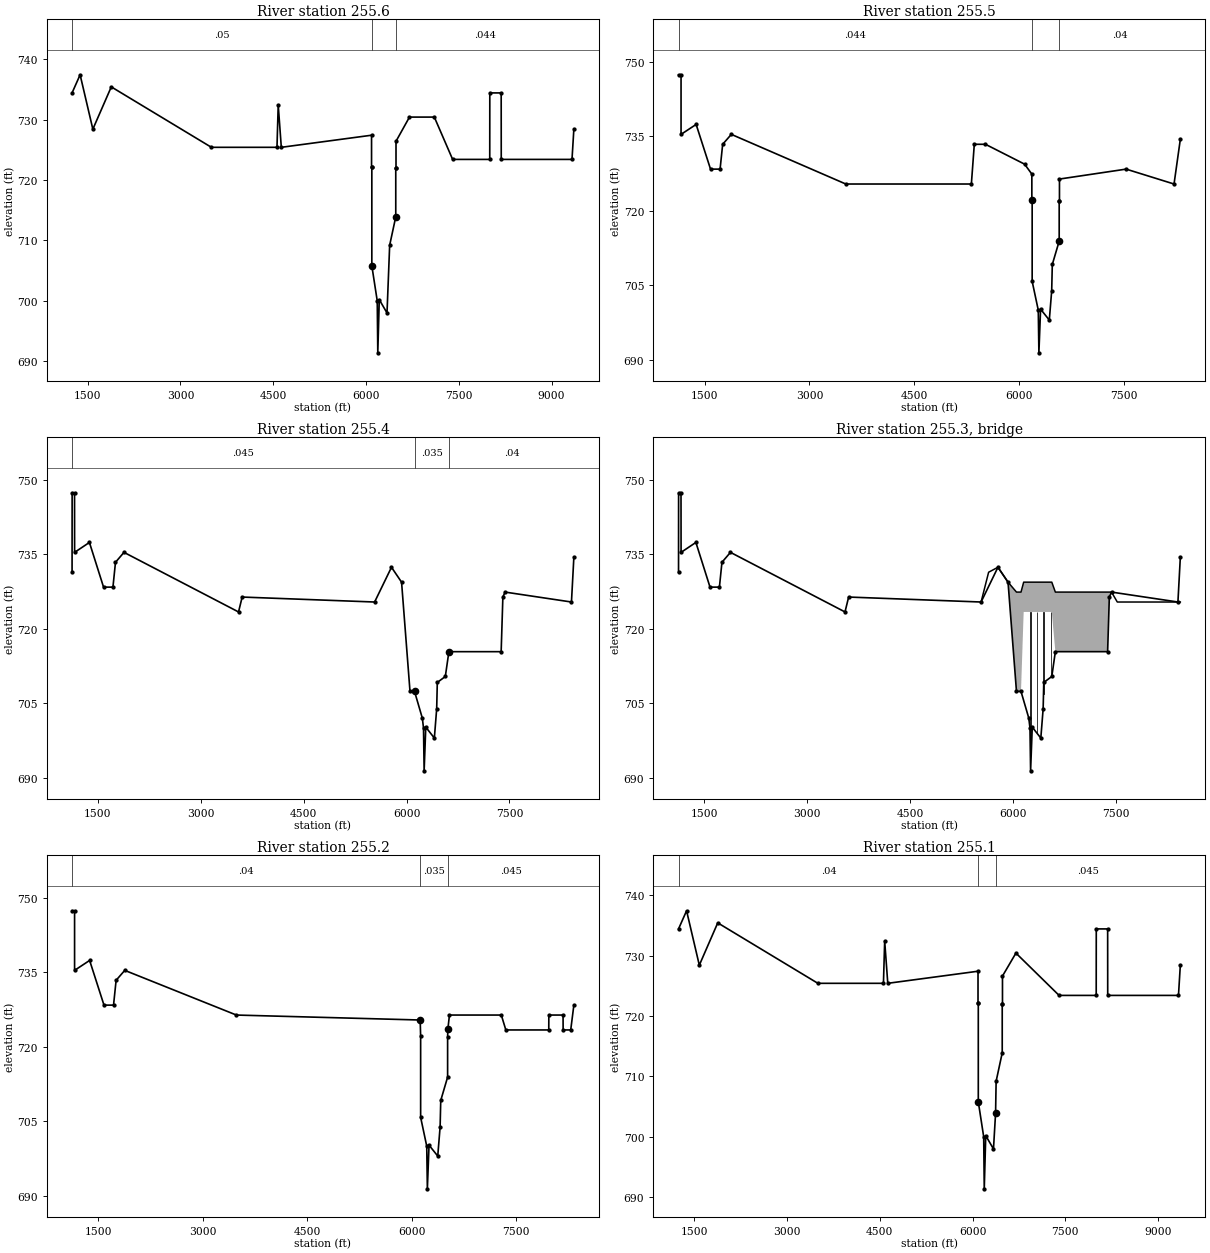
Type RM Length L Ch R = 1 ,255.6   ,218.8,218.8,218.8
XS GIS Cut Line= 6
  1822099.710436  717489.1268941 1821920.8836948  717364.1635614
 1821431.1540312  716843.8171611 1821148.7238218  716313.9215674
 1821039.5862448  716235.8360936 1821042.8929967  716087.4154587
#Sta/Elev= 30
    1247   734.4    1377   737.4    1583   728.4    1881   735.4    3500   725.4
    4560   725.4    4580   732.4    4630   725.4    6089   727.4    6089   722.1
  6093.5   722.1  6093.6   705.8    6181     700  6189.9   691.4    6214   700.2
    6339     698  6381.9   709.2  6480.5   713.9  6480.5     722  6484.5     722
  6484.5   726.4    6702   730.4    7104   730.4    7400   723.4    8000   723.4
    8001   734.4    8185   734.4    8186   723.4    9330   723.4    9360   728.4
#Mann= 3 , 0 , 0
    1247     .05       0  6093.6    .035       0  6480.5    .044       0
#Block Obstruct= 2 , 0
                            6638
Bank Sta=6093.6,6480.5
XS Rating Curve= 0 ,0
Exp/Cntr=0.3,0.1

Type RM Length L Ch R = 1 ,255.5   ,50,50,50
XS GIS Cut Line= 6
  1822819.987539  717658.5802954  1821974.057473  717108.7382192
 1821708.9864808   716761.017458 1821285.9696103   716332.199418
 1821064.2259593  716174.4510458 1821091.6074662  716104.5000702
#Sta/Elev= 30
    1125   747.4    1161   747.4    1161   735.4    1377   737.4    1583   728.4
    1720   728.4    1757   733.4    1881   735.4    3520   725.4    5318   725.4
    5360   733.4    5520   733.4    6080   729.4    6184   727.4    6184   722.1
  6188.5   722.1  6188.5   705.8    6276     700  6284.9   691.4    6309   700.2
    6434     698  6468.1   703.9  6476.9   709.2  6575.5   713.9  6575.5     722
  6579.5     722  6579.5   726.4    7534   728.4    8220   725.4    8310   734.4
#Mann= 3 , 0 , 0
    1125    .044       0  6188.5    .035       0  6575.5     .04       0
#Block Obstruct= 2 , 0
                            6638
Bank Sta=6188.5,6575.5
XS Rating Curve= 0 ,0
Exp/Cntr=0.3,0.1

Type RM Length L Ch R = 1 ,255.4   ,45.5,45.5,45.5
BEGIN DESCRIPTION:
I-670 Ramp (Downstream) Crossing #1 - Upstream Section
END DESCRIPTION:
XS GIS Cut Line= 4
  1822159.492797  717119.3015183 1821978.3714407  716994.5173191
 1821397.7695836  716370.0700771 1821308.2743557  716245.8902074
#Sta/Elev= 30
    1124   731.4    1125   747.4    1160   747.4    1161   735.4    1377   737.4
    1583   728.4    1720   728.4    1757   733.4    1881   735.4    3551   723.4
    3604   726.4    5535   725.4    5781   732.4    5928   729.4    6051   707.4
    6117   707.4    6231     702    6248     700    6257   691.4    6281   700.2
    6406     698    6440   703.9    6449   709.2    6566   710.4    6618   715.4
    7380   715.4    7405   726.4    7437   727.4    8405   725.4    8440   734.4
#Mann= 3 , 0 , 0
    1124    .045       0    6117    .035       0    6618     .04       0
#Block Obstruct= 2 , 0
                            6900
Bank Sta=6117,6618
XS Rating Curve= 0 ,0
Exp/Cntr=0.5,0.3

Type RM Length L Ch R = 3 ,255.3   ,,,
BEGIN DESCRIPTION:
Structure #15 Interstate 670 Ramp Bridge (downstream), Crossing #1
END DESCRIPTION:
Bridge Culvert--1,0,-1,-1, 0
Deck Dist Width WeirC Skew NumUp NumDn MinLoCord MaxHiCord MaxSubmerge Is_Ogee
1,43,2.6,0, 15, 13, 727.4, , 0.95, 0, 0,0,,
    5535    5645    5781    5928    6051    6117    6156    6566    6618    6959
    7380    7405    7437    7521    8440
   725.4   731.4   732.4   729.4   727.4   727.4   729.4   729.4   727.4   727.4
   727.4   727.4   727.4   725.4   725.4
   725.4   731.4   732.4   729.4   707.4   707.4   723.4   723.4   715.4   715.4
   715.4   726.4   727.4   725.4   725.4
    5535    5928    6016    6082    6121    6531    6583    6924    7345    7370
    7437    7521    8440
   725.4   726.4   727.4   727.4   729.4   729.4   727.4   727.4   727.4   727.4
   727.4   725.4   725.4
   725.4   726.4   707.4   707.4   723.4   723.4   715.4   715.4   715.4   726.4
   727.4   725.4   725.4
Pier Skew, UpSta & Num, DnSta & Num=  ,6252.5, 2 ,6217.5, 2 , 0 , 0 , 0 ,,
       9       9
   691.4   723.4
       9       9
   691.4   723.4
Pier Skew, UpSta & Num, DnSta & Num=  ,6348.5, 2 ,6313.5, 2 , 0 , 0 , 0 ,,
       9       9
   698.6   723.4
       9       9
   697.5   723.4
Pier Skew, UpSta & Num, DnSta & Num=  ,6445, 2 ,6410, 2 , 0 , 0 , 0 ,,
       9       9
   703.9   723.4
       9       8
   703.9   723.4
Pier Skew, UpSta & Num, DnSta & Num=  ,6549.5, 2 ,6514.5, 2 , 0 , 0 , 0 ,,
       4       4
   713.9   723.6
       4       4
   713.9   723.6
BR Coef=-1 , 0 , 0 ,, 0 ,,,0.8,-1,,0,
WSPro=,,,, 1 ,,,, 0 ,,,, 0 ,,,,-1 ,-1 ,-1 , 0 , 0 , 0 , 0 , 0
BR D #Sta/Elev= 86
    1125   747.4    1161   747.4    1161   735.4    1240   734.5    1247   734.4
    1313   737.4    1377   737.4    1417   734.4    1583   728.4    1700   728.4
    1720   728.4    1757   733.4    1881   735.4    2018   733.4    2154   733.4
    2376   732.4    2644   731.4    2934   730.4    3043   728.4    3095   728.4
    3193   727.4    3397   727.4    3483   726.4    3520   726.4    3800   726.4
    4000   726.4    4200   726.4    4400   726.4    4600   726.4    4800   726.4
    4920   726.4    5000   726.4    5060   726.4    5200   726.4    5400   726.4
    5600   726.4    5800   726.4    5955   726.4    5956   725.4    6120   725.4
    6123   722.1  6126.5   722.1  6126.5   705.8    6153   704.2    6158   703.3
    6172   700.6    6197     702    6214     700    6223   691.4    6247   700.2
    6272   700.4    6310   698.6    6319   697.5    6347   698.8    6372     698
    6406   703.9    6415   709.2    6420   709.4    6447   710.5    6482   710.6
  6513.5   713.9  6513.5     722  6517.5   723.6    6540   726.4    6576   726.4
    6660   726.4    6807   726.4    6958   726.4    7171   726.4    7284   726.4
    7349   723.4    7451   725.4    7480   723.4    7550   723.4    7735   723.4
    7740   724.4    7765   724.4    7780   723.4    7965   723.4    7966   726.4
    8170   726.4    8171   723.4    8280   723.4    8290   726.4    8310   726.4
    8325   728.4
BR D #Mann= 3
    1125     .04    6120    .035  6517.5    .045
BR D Banks=6120,6517.5
BC Design=,, 0 ,, 0 ,,,,,,
BC HTab HWMax=747.4
BC Use User HTab Curves=0
BC User HTab FreeFlow(D)= 0

Type RM Length L Ch R = 1 ,255.2   ,50,50,50
BEGIN DESCRIPTION:
I-670 Ramp (Downstream) Crossing #1 - Downstream Section
END DESCRIPTION:
XS GIS Cut Line= 4
  1822205.874594  717096.0033366 1822008.2952654  716959.8802492
 1821433.0234501  716341.1656074 1821345.1873396  716219.2875703
#Sta/Elev= 30
    1125   747.4    1161   747.4    1161   735.4    1377   737.4    1583   728.4
    1720   728.4    1757   733.4    1881   735.4    3483   726.4    6120   725.4
  6126.5   722.1  6126.5   705.8    6214     700    6223   691.4    6247   700.2
    6372     698    6406   703.9    6415   709.2  6513.5   713.9  6513.5     722
  6517.5   723.6    6540   726.4    7284   726.4    7349   723.4    7965   723.4
    7966   726.4    8170   726.4    8171   723.4    8280   723.4    8325   728.4
#Mann= 3 , 0 , 0
    1125     .04       0    6120    .035       0  6517.5    .045       0
#Block Obstruct= 2 , 0
                            6576
Bank Sta=6120,6517.5
XS Rating Curve= 0 ,0
Exp/Cntr=0.5,0.3

Type RM Length L Ch R = 1 ,255.1   ,448.2,448.2,448.2
XS GIS Cut Line= 3
  1821973.131949  716848.6324402 1821471.7638581  716309.4025476
 1821385.7505787   716190.054033
#Sta/Elev= 30
    1247   734.4    1377   737.4    1583   728.4    1881   735.4    3500   725.4
    4560   725.4    4580   732.4    4630   725.4    6089   727.4    6089   722.1
  6093.5   722.1  6093.6   705.8    6181     700  6189.9   691.4    6214   700.2
    6339     698    6373   703.9  6381.9   709.2  6480.5   713.9  6480.5     722
  6484.5     722  6484.5   726.6    6702   730.4    7400   723.4    8000   723.4
    8001   734.4    8185   734.4    8186   723.4    9330   723.4    9360   728.4
#Mann= 3 , 0 , 0
    1247     .04       0  6093.6    .035       0    6373    .045       0
#Block Obstruct= 2 , 0
                            6527
Bank Sta=6093.6,6373
XS Rating Curve= 0 ,0
Exp/Cntr=0.5,0.3