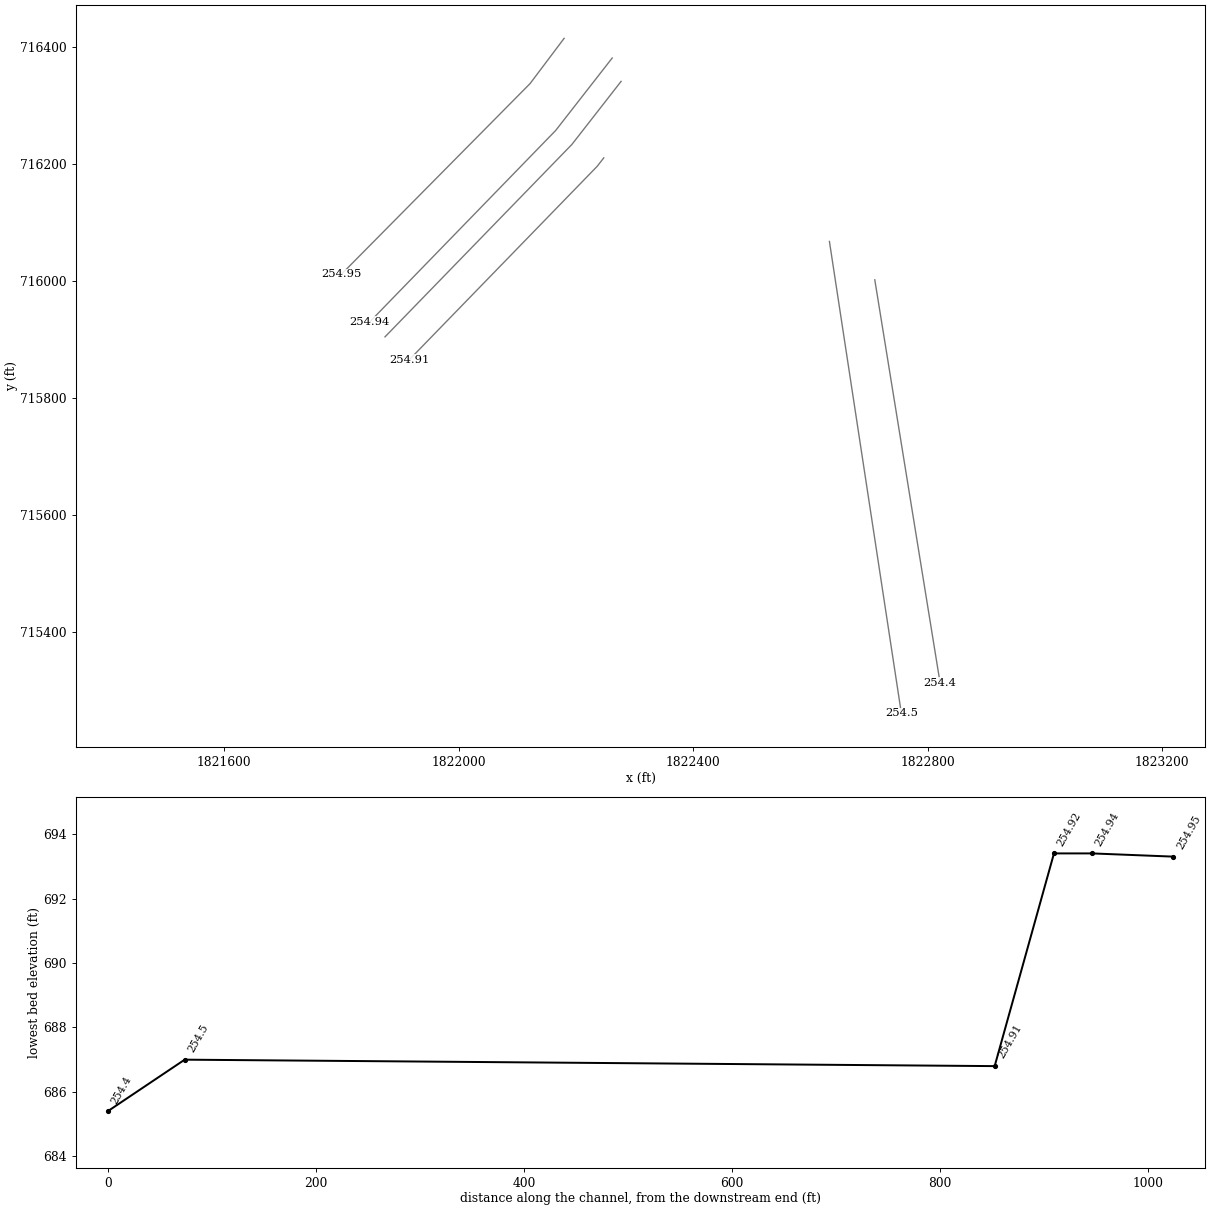
HEC-RAS study FRA-70-1321R.prj: FRA-70-1321R

--- FRA-70-1321R.g06 (geometry) --- (continued)

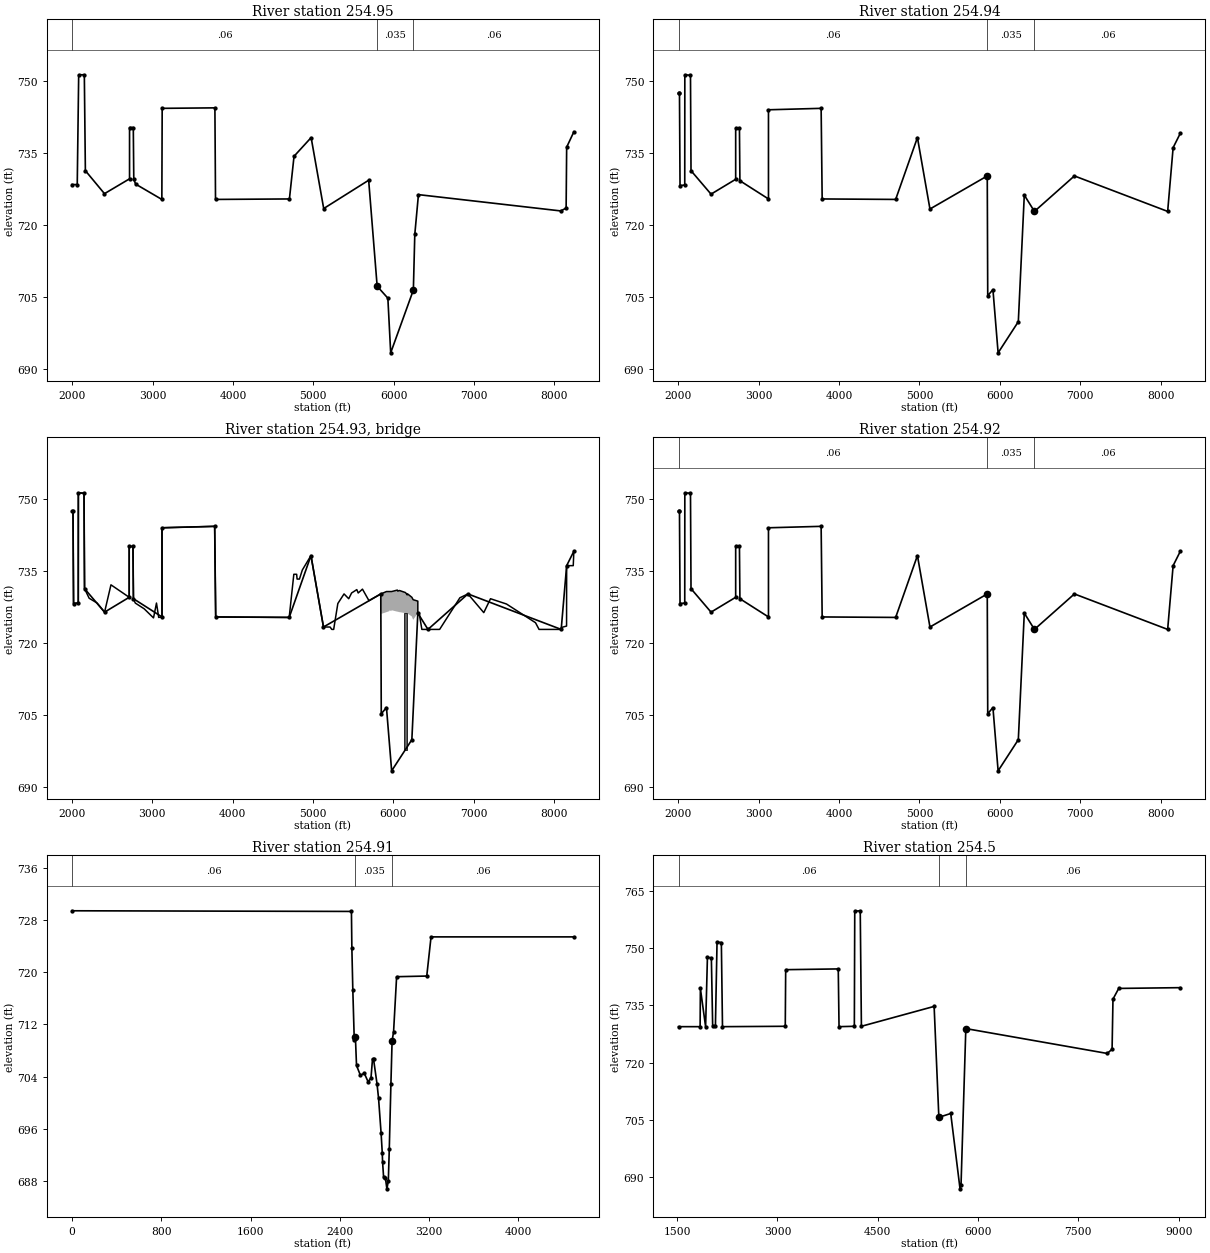
Type RM Length L Ch R = 1 ,254.95  ,78.33,78.33,78.33
XS GIS Cut Line= 3
  1822179.787704  716414.3026002 1822121.8038966  716337.0717836
 1821799.4187146  716010.5721085
#Sta/Elev= 30
  1996.4   728.4  2060.8   728.4  2078.8   751.3  2149.1   751.3    2162   731.3
  2399.8   726.5    2712   729.6    2712   740.3  2758.7   740.3  2764.7   729.5
  2787.6   728.5  3114.2   725.3  3118.3   744.3  3774.7   744.4  3782.3   725.3
  4702.4   725.4  4759.8   734.3  4972.8   738.2  5129.2   723.4    5689   729.3
  5794.7   707.2  5928.1   704.7  5963.2   693.3  6245.5   706.4  6263.3     718
  6308.7   726.3  8080.8   722.9  8147.4   723.5  8154.1   736.2  8243.7   739.4
#Mann= 3 , 0 , 0
  1996.4     .06       0  5794.7    .035       0  6245.5     .06       0
#Block Obstruct= 2 , 0
                            6400
Bank Sta=5794.7,6245.5
XS Rating Curve= 0 ,0
Exp/Cntr=0.3,0.1

Type RM Length L Ch R = 1 ,254.94  ,36.5,36.5,36.5
BEGIN DESCRIPTION:
REPEATED section.  Souder Avenue Bridge - Upstream Section
END DESCRIPTION:
XS GIS Cut Line= 3
  1822261.794102  716380.6435468 1822165.3992819  716256.8183351
 1821848.0062159  715929.3685307
#Sta/Elev= 30
  2002.7   747.5  2014.4   747.5  2021.3   728.3    2080   728.4    2081   751.4
  2151.4   751.3  2157.9   731.4  2407.1   726.5  2713.6   729.6  2713.6   740.2
  2760.5   740.2  2766.2   729.3  3121.6   725.5  3121.6   744.1  3776.8   744.4
  3789.6   725.5  4703.9   725.4  4974.8   738.3  5130.6   723.4  5843.5   730.3
  5849.4   705.3  5914.2   706.6  5978.6   693.4    6230   699.9  6304.3   726.3
  6430.5   722.9  6927.7   730.3  8087.9   722.9  8155.9   736.2  8245.5   739.2
#Mann= 3 , 0 , 0
  2002.7     .06       0  5843.5    .035       0  6430.5     .06       0
#XS Ineff= 2 , 0
          5843.5   722.9  6430.5           722.9
Permanent Ineff=
       F       F
#Block Obstruct= 2 , 0
                            6400
Bank Sta=5843.5,6430.5
XS Rating Curve= 0 ,0
Exp/Cntr=0.3,0.1

Type RM Length L Ch R = 3 ,254.93  ,,,
BEGIN DESCRIPTION:
Structure #14 North Souder Avenue Bridge
END DESCRIPTION:
Bridge Culvert--1,0,-1,-1, 0
Deck Dist Width WeirC Skew NumUp NumDn MinLoCord MaxHiCord MaxSubmerge Is_Ogee
1,35,2.6,0, 80, 80, 728.4, , 0.95, 0, 0,0,,
  2002.7  2014.4  2021.3    2080    2081  2151.4  2157.9  2215.4  2314.4  2407.1
  2486.5  2713.6  2713.6  2760.5  2766.2  2789.1  2899.8    3016  3052.9  3080.5
  3121.6  3121.6  3776.8  3789.6  4703.9  4761.6  4796.8  4802.1  4831.4  4867.6
  4974.8  5130.6  5212.6  5233.9  5257.3  5309.1  5386.4  5444.5  5480.3  5545.1
  5562.3  5615.5  5696.3  5843.5  5843.5  5914.2  5949.3  5955.2  5972.8  5978.6
  6049.1  6054.9  6072.5  6078.4  6148.4  6160.1  6171.6  6177.6    6230    6246
  6304.3  6304.3  6321.8  6354.4  6430.5  6552.4  6575.4  6827.7  6927.7  7124.8
  7208.5  7407.1  7768.4  7812.5  8087.9  8090.1  8154.7  8155.9  8237.9  8245.5
   747.5   747.5   728.3   728.4   751.4   751.3   731.4   729.4   728.4   726.5
   732.2   729.6   740.2   740.2   729.3   728.4   727.2   725.3   728.4   725.4
   725.5   744.1   744.4   725.5   725.4   734.4   734.4   733.4   733.4   735.3
   738.3   723.4   723.4   722.9   722.9   728.3   730.3   729.3   730.5   731.2
   730.5   731.3   728.9   730.3   730.3   730.8   730.8   730.8   730.8   730.8
   731.1   730.9     731     731   730.6   730.4   730.1   730.3   729.6   729.1
   728.8   726.3   726.2   722.9   722.9   722.9   722.9   729.5   730.3   726.4
   729.3   728.2   724.3   722.9   722.9   723.3   723.6   736.2   736.2   739.2
   747.5   747.5   728.3   728.4   751.4   751.3   731.4   729.4   728.4   726.5
   732.2   729.6   740.2   740.2   729.3   728.4   727.2   725.3   728.4   725.4
   725.5   744.1   744.4   725.5   725.4   734.4   734.4   733.4   733.4   735.3
   738.3   723.4   723.4   722.9   722.9   728.3   730.3   729.3   730.5   731.2
   730.5   731.3   728.9   730.3   726.1   726.5   726.7   726.9   726.7   726.9
   726.6   726.6   726.5   726.5   726.3   726.2   726.3   726.2   725.6   724.9
   724.4   726.3   726.2   722.9   722.9   722.9   722.9   729.5   730.3   726.4
   729.3   728.2   724.3   722.9   722.9   723.3   723.6   736.2   736.2   739.2
  2002.7  2014.4  2021.3    2080    2081  2151.4  2157.9  2215.4  2314.4  2407.1
  2486.5  2713.6  2713.6  2760.5  2766.2  2789.1  2899.8    3016  3052.9  3080.5
  3121.6  3121.6  3776.8  3789.6  4703.9  4761.6  4796.8  4802.1  4831.4  4867.6
  4974.8  5130.6  5212.6  5233.9  5257.3  5309.1  5386.4  5444.5  5480.3  5545.1
  5562.3  5615.5  5696.3  5843.5  5843.5  5914.2  5949.3  5955.2  5972.8  5978.6
  6049.1  6054.9  6072.5  6078.4  6148.4  6160.1  6171.6  6177.6    6230    6246
  6304.3  6304.3  6321.8  6354.4  6430.5  6552.4  6575.4  6827.7  6927.7  7124.8
  7208.5  7407.1  7768.4  7812.5  8087.9  8090.1  8154.7  8155.9  8237.9  8245.5
   747.5   747.5   728.3   728.4   751.4   751.3   731.4   729.4   728.4   726.5
   732.2   729.6   740.2   740.2   729.3   728.4   727.2   725.3   728.4   725.4
   725.5   744.1   744.4   725.5   725.4   734.4   734.4   733.4   733.4   735.3
   738.3   723.4   723.4   722.9   722.9   728.3   730.3   729.3   730.5   731.2
   730.5   731.3   728.9   730.3   730.3   730.8   730.8   730.8   730.8   730.8
   731.1   730.9     731     731   730.6   730.4   730.1   730.3   729.6   729.1
   728.8   726.3   726.2   722.9   722.9   722.9   722.9   729.5   730.3   726.4
   729.3   728.2   724.3   722.9   722.9   723.3   723.6   736.2   736.2   739.2
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Pier Skew, UpSta & Num, DnSta & Num=  ,5997.1, 2 ,5997.1, 2 , 0 , 0 , 0 ,,
    29.3    17.6
   693.4   726.9
    29.3    17.6
   693.4   726.9
Pier Skew, UpSta & Num, DnSta & Num=  ,6150.7, 2 ,6150.7, 2 , 0 , 0 , 0 ,,
    29.3    17.6
   693.4   726.6
    29.3    17.6
   693.4   726.6
BR Coef=-1 , 0 , 0 ,, 0 ,,,0.8,-1,,1,
WSPro=,,,, 1 ,,,, 0 ,,,, 0 ,,,,-1 ,-1 ,-1 , 0 , 0 , 0 , 0 , 0
BC Design=,, 0 ,, 0 ,,,,,,
BC HTab HWMax=751.4
BC Use User HTab Curves=0
BC User HTab FreeFlow(D)= 0

Type RM Length L Ch R = 1 ,254.92  ,57,57,57
BEGIN DESCRIPTION:
Souder Avenue Bridge - Downstream Section
END DESCRIPTION:
XS GIS Cut Line= 3
  1822276.989281  716340.7440203 1822192.9851847  716232.8354435
 1821874.2148249  715903.9647101
#Sta/Elev= 30
  2002.7   747.5  2014.4   747.5  2021.3   728.3    2080   728.4    2081   751.4
  2151.4   751.3  2157.9   731.4  2407.1   726.5  2713.6   729.6  2713.6   740.2
  2760.5   740.2  2766.2   729.3  3121.6   725.5  3121.6   744.1  3776.8   744.4
  3789.6   725.5  4703.9   725.4  4974.8   738.3  5130.6   723.4  5843.5   730.3
  5849.4   705.3  5914.2   706.6  5978.6   693.4    6230   699.9  6304.3   726.3
  6430.5   722.9  6927.7   730.3  8087.9   722.9  8155.9   736.2  8245.5   739.2
#Mann= 3 , 0 , 0
  2002.7     .06       0  5843.5    .035       0  6430.5     .06       0
#XS Ineff= 2 , 0
          5843.5   722.9  6430.5           722.9
Permanent Ineff=
       F       F
#Block Obstruct= 2 , 0
                            6400
Bank Sta=5843.5,6430.5
XS Rating Curve= 0 ,0
Exp/Cntr=0.3,0.1

Type RM Length L Ch R = 1 ,254.91  ,778.5,778.5,778.5
XS GIS Cut Line= 3
  1822247.387306  716209.9270247  1822236.064823  716195.3827625
 1821915.1435488  715864.2928735
#Sta/Elev= 30
       0   729.4  2504.3   729.3  2508.2   723.7  2516.7   717.3  2529.7   709.6
    2540     710  2549.9   705.7  2584.6   704.2  2619.7   704.5  2653.7   703.2
  2679.7   703.8  2693.3   706.7  2702.3   706.7  2733.6   702.9  2747.3   700.7
  2770.3   695.3  2780.7   692.3  2783.5   690.9  2792.6   688.6  2808.5   688.5
  2822.2   686.8    2835     688  2843.6   692.9  2858.1   702.8  2868.6   709.4
  2882.2   710.9  2909.3   719.3  3179.5   719.4  3217.9   725.4  4498.2   725.4
#Mann= 3 , 0 , 0
       0     .06       0    2540    .035       0  2868.6     .06       0
#Block Obstruct= 2 , 0
                            3250
Bank Sta=2540,2868.6
XS Rating Curve= 0 ,0
Exp/Cntr=0.3,0.1

Type RM Length L Ch R = 1 ,254.5   ,73.92,73.92,73.92
BEGIN DESCRIPTION:
AM
END DESCRIPTION:
Node Name=AM
XS GIS Cut Line= 2
  1822632.359634  716067.0601845 1822755.0942967   715260.276365
#Sta/Elev= 30
  1520.3   729.4  1843.1   729.4  1847.1   739.4  1925.2   729.4  1952.4   747.5
  2011.2   747.4  2030.8   729.6  2071.9   729.5  2096.1   751.5  2160.7   751.4
  2177.7   729.4  3116.6   729.5  3122.9   744.3  3909.2   744.5  3920.8   729.4
  4149.7   729.5  4155.9   759.6    4238   759.7  4255.3   729.5    5343   734.7
  5413.8   705.7  5591.3   706.7  5730.5     687  5745.5   688.1  5817.1   728.9
  7931.4   722.4  8004.6   723.5    8018   736.6  8103.9   739.4  9025.3   739.6
#Mann= 3 , 0 , 0
  1520.3     .06       0  5413.8    .035       0  5817.1     .06       0
#Block Obstruct= 2 , 0
                            5840
Bank Sta=5413.8,5817.1
XS Rating Curve= 0 ,0
Exp/Cntr=0.3,0.1

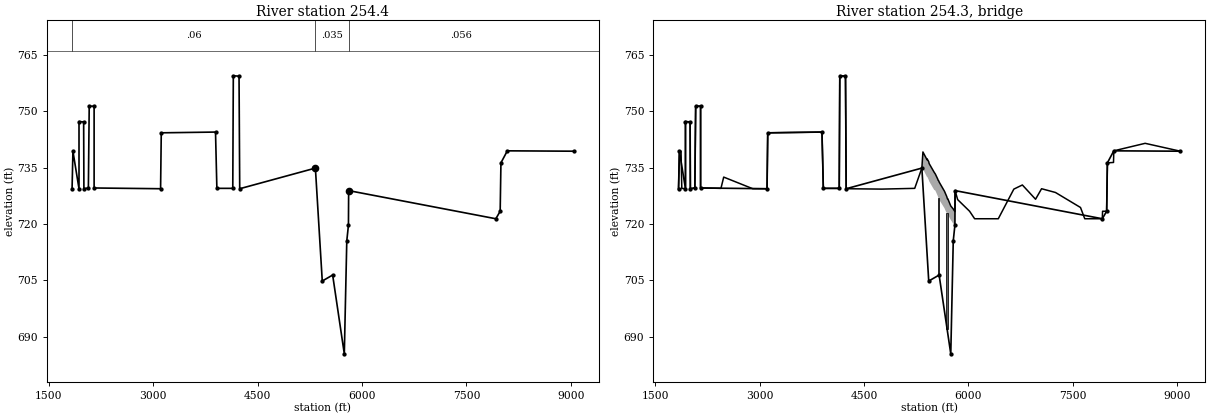
Type RM Length L Ch R = 1 ,254.4   ,148.5,148.5,148.5
BEGIN DESCRIPTION:
REPEATED section.  Ohio State Route 315 - Upstream Section
END DESCRIPTION:
XS GIS Cut Line= 2
  1822709.757445  716001.4412212 1822821.0767763  715313.0036217
#Sta/Elev= 30
  1836.9   729.4  1849.3   739.4  1936.5   729.4  1936.5   747.3  2003.3   747.2
  2006.8   729.4  2071.1   729.6  2083.1   751.4  2153.4   751.4  2153.4   729.6
  3107.9   729.4  3117.7   744.3  3896.6   744.5  3916.1   729.5  4144.5   729.5
  4152.2   759.5  4234.3   759.4  4244.1   729.4  5330.7   734.9  5429.4   704.8
  5578.6   706.4  5745.9   685.4  5781.5   715.5  5805.3   719.7  5808.2   728.9
  7921.7   721.4    7984   723.4  7994.9   736.3  8086.9   739.5    9042   739.4
#Mann= 3 , 0 , 0
  1836.9     .06       0  5330.7    .035       0  5808.2    .056       0
#XS Ineff= 2 , 0
          5330.7   729.4  5808.2           721.4
Permanent Ineff=
       F       F
#Block Obstruct= 2 , 0
                            5840
Bank Sta=5330.7,5808.2
XS Rating Curve= 0 ,0
Exp/Cntr=0.3,0.1

Type RM Length L Ch R = 3 ,254.3   ,,,
BEGIN DESCRIPTION:
Structure #13 Ohio State Route 315 Bridge
END DESCRIPTION:
Bridge Culvert--1,0,-1,-1, 0
Deck Dist Width WeirC Skew NumUp NumDn MinLoCord MaxHiCord MaxSubmerge Is_Ogee
1,147,2.6,0, 67, 67, 721.9, , 0.95, 0, 0,0,,
  1836.9  1849.3  1872.7  1883.7  1936.5  1936.5  2003.3  2006.8  2071.1  2083.1
  2153.4  2153.4    2446  2485.5  2902.9  3107.9  3117.7  3896.6  3916.1  4144.5
  4152.2  4234.3  4244.1  4753.8  5228.1  5330.7    5346  5405.7  5408.1  5423.4
  5429.4  5435.5    5507  5524.8  5560.6    5563  5572.6  5578.6  5656.1    5686
  5688.4  5698.1    5704  5745.9  5781.5  5805.3  5805.3  5808.2  5844.6  6016.1
  6088.4  6428.2  6651.4  6773.8  6963.3  7049.6  7249.3  7608.7  7669.9  7921.7
  7925.5    7984  7994.9  8082.6  8086.9  8536.8    9042
   729.4   739.4   739.4   729.5   729.4   747.3   747.2   729.4   729.6   751.4
   751.4   729.6   729.5   732.5   729.4   729.4   744.3   744.5   729.5   729.5
   759.5   759.4   729.4   729.3   729.5   734.9   739.2   737.1   737.3   736.8
   736.6   736.1   733.8   733.3   731.9   731.7   731.5   731.2   728.7   727.4
   727.3   726.7   726.7   724.8     724   723.3   724.7   728.9   726.5   723.4
   721.4   721.4   729.3   730.4   726.6   729.4   728.4   724.4   721.4   721.4
   723.4   723.4   736.3   736.4   739.5   741.5   739.4
   729.4   739.4   739.4   729.5   729.4   747.3   747.2   729.4   729.6   751.4
   751.4   729.6   729.5   732.5   729.4   729.4   744.3   744.5   729.5   729.5
   759.5   759.4   729.4   729.3   729.5   734.9   734.7   732.5   732.6     732
   731.8   731.4   729.1   728.9   727.4   727.2   726.9   726.5   724.2   722.9
   723.1   722.9   722.5   721.1   720.1   719.7   724.7   728.9   726.5   723.4
   721.4   721.4   729.3   730.4   726.6   729.4   728.4   724.4   721.4   721.4
   723.4   723.4   736.3   736.4   739.5   741.5   739.4
  1836.9  1849.3  1872.7  1883.7  1936.5  1936.5  2003.3  2006.8  2071.1  2083.1
  2153.4  2153.4    2446  2485.5  2902.9  3107.9  3117.7  3896.6  3916.1  4144.5
  4152.2  4234.3  4244.1  4753.8  5228.1  5330.7    5346  5405.7  5408.1  5423.4
  5429.4  5435.5    5507  5524.8  5560.6    5563  5572.6  5578.6  5656.1    5686
  5688.4  5698.1    5704  5745.9  5781.5  5805.3  5805.3  5808.2  5844.6  6016.1
  6088.4  6428.2  6651.4  6773.8  6963.3  7049.6  7249.3  7608.7  7669.9  7921.7
  7925.5    7984  7994.9  8082.6  8086.9  8536.8    9042
   729.4   739.4   739.4   729.5   729.4   747.3   747.2   729.4   729.6   751.4
   751.4   729.6   729.5   732.5   729.4   729.4   744.3   744.5   729.5   729.5
   759.5   759.4   729.4   729.3   729.5   734.9   739.2   737.1   737.3   736.8
   736.6   736.1   733.8   733.3   731.9   731.7   731.5   731.2   728.7   727.4
   727.3   726.7   726.7   724.8     724   723.3   724.7   728.9   726.5   723.4
   721.4   721.4   729.3   730.4   726.6   729.4   728.4   724.4   721.4   721.4
   723.4   723.4   736.3   736.4   739.5   741.5   739.4
   729.4   739.4   739.4   729.5   729.4   747.3   747.2   729.4   729.6   751.4
   751.4   729.6   729.5   732.5   729.4   729.4   744.3   744.5   729.5   729.5
   759.5   759.4   729.4   729.3   729.5   734.9   734.7   732.5   732.6     732
   731.8   731.4   729.1   728.9   727.4   727.2   726.9   726.5   724.2   722.9
   723.1   722.9   722.5   721.1   720.1   719.7   724.7   728.9   726.5   723.4
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Pier Skew, UpSta & Num, DnSta & Num=  ,5415.8, 2 ,5415.8, 2 , 0 , 0 , 0 ,,
    23.6    15.3
   704.8   732.6
    23.6    15.3
   704.8   732.6
Pier Skew, UpSta & Num, DnSta & Num=  ,5567.8, 2 ,5567.8, 2 , 0 , 0 , 0 ,,
      18     9.6
   704.5   727.2
      18     9.6
   704.5   727.2
Pier Skew, UpSta & Num, DnSta & Num=  ,5693.3, 2 ,5693.3, 2 , 0 , 0 , 0 ,,
      18     9.7
   685.7   723.1
      18     9.7
   685.7   723.1
BR Coef=-1 , 0 , 0 ,, 0 ,,,0.8,-1,,0,
WSPro=,,,, 1 ,,,, 0 ,,,, 0 ,,,,-1 ,-1 ,-1 , 0 , 0 , 0 , 0 , 0
BC Design=,, 0 ,, 0 ,,,,,,
BC HTab HWMax=759.5
BC Use User HTab Curves=0
BC User HTab FreeFlow(D)= 0