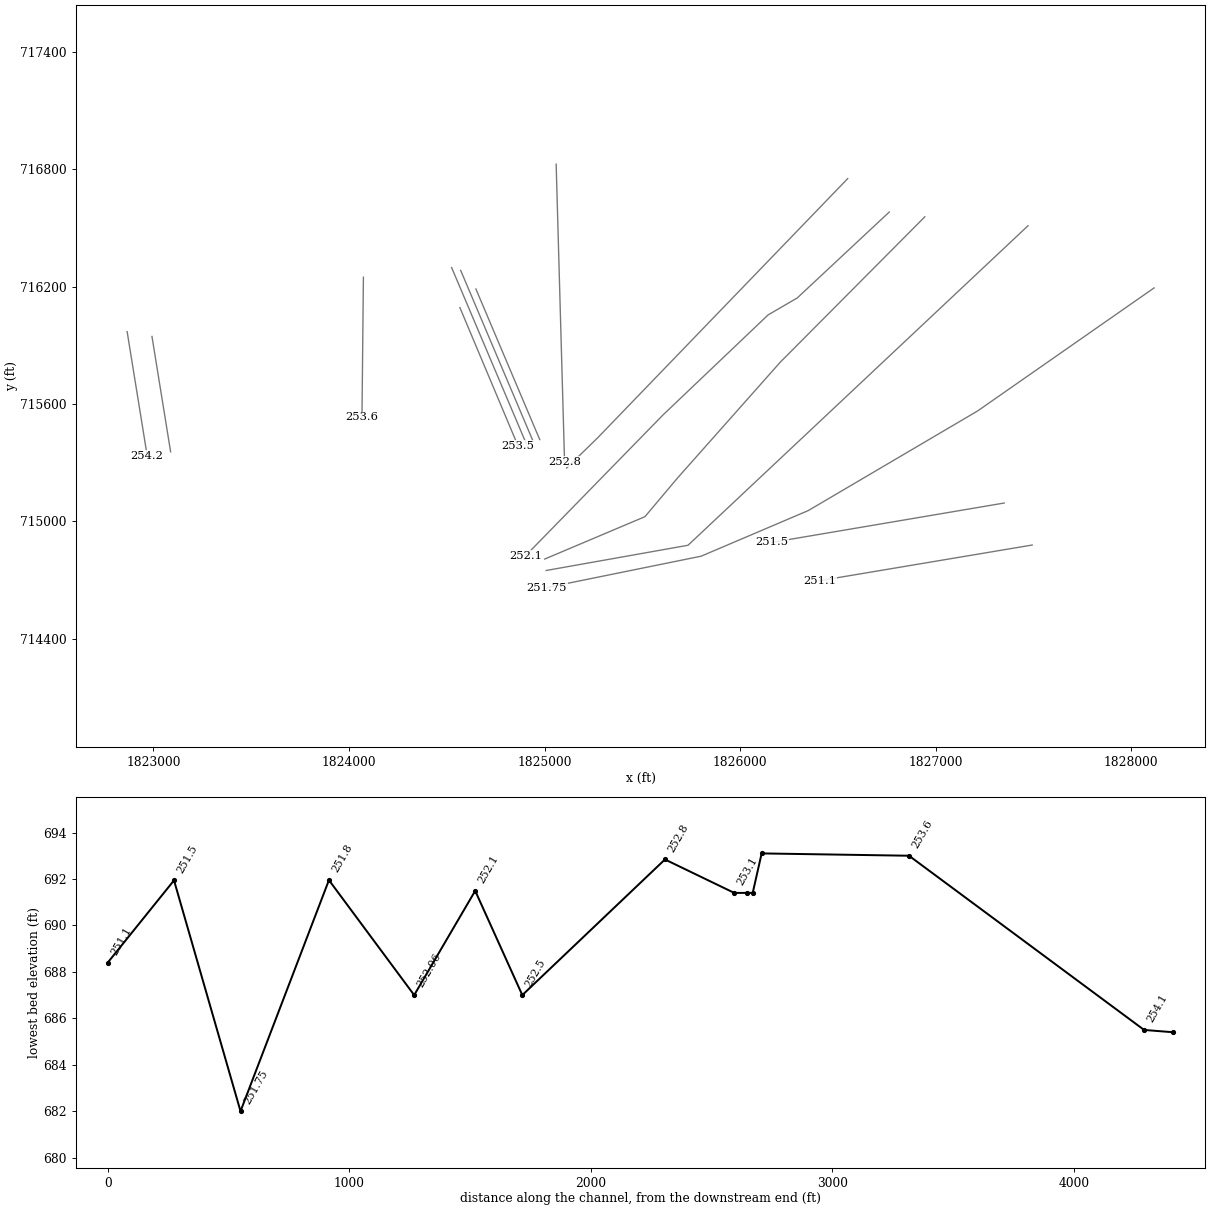
HEC-RAS study FRA-70-1321R.prj: FRA-70-1321R

--- FRA-70-1321R.g06 (geometry) --- (continued)

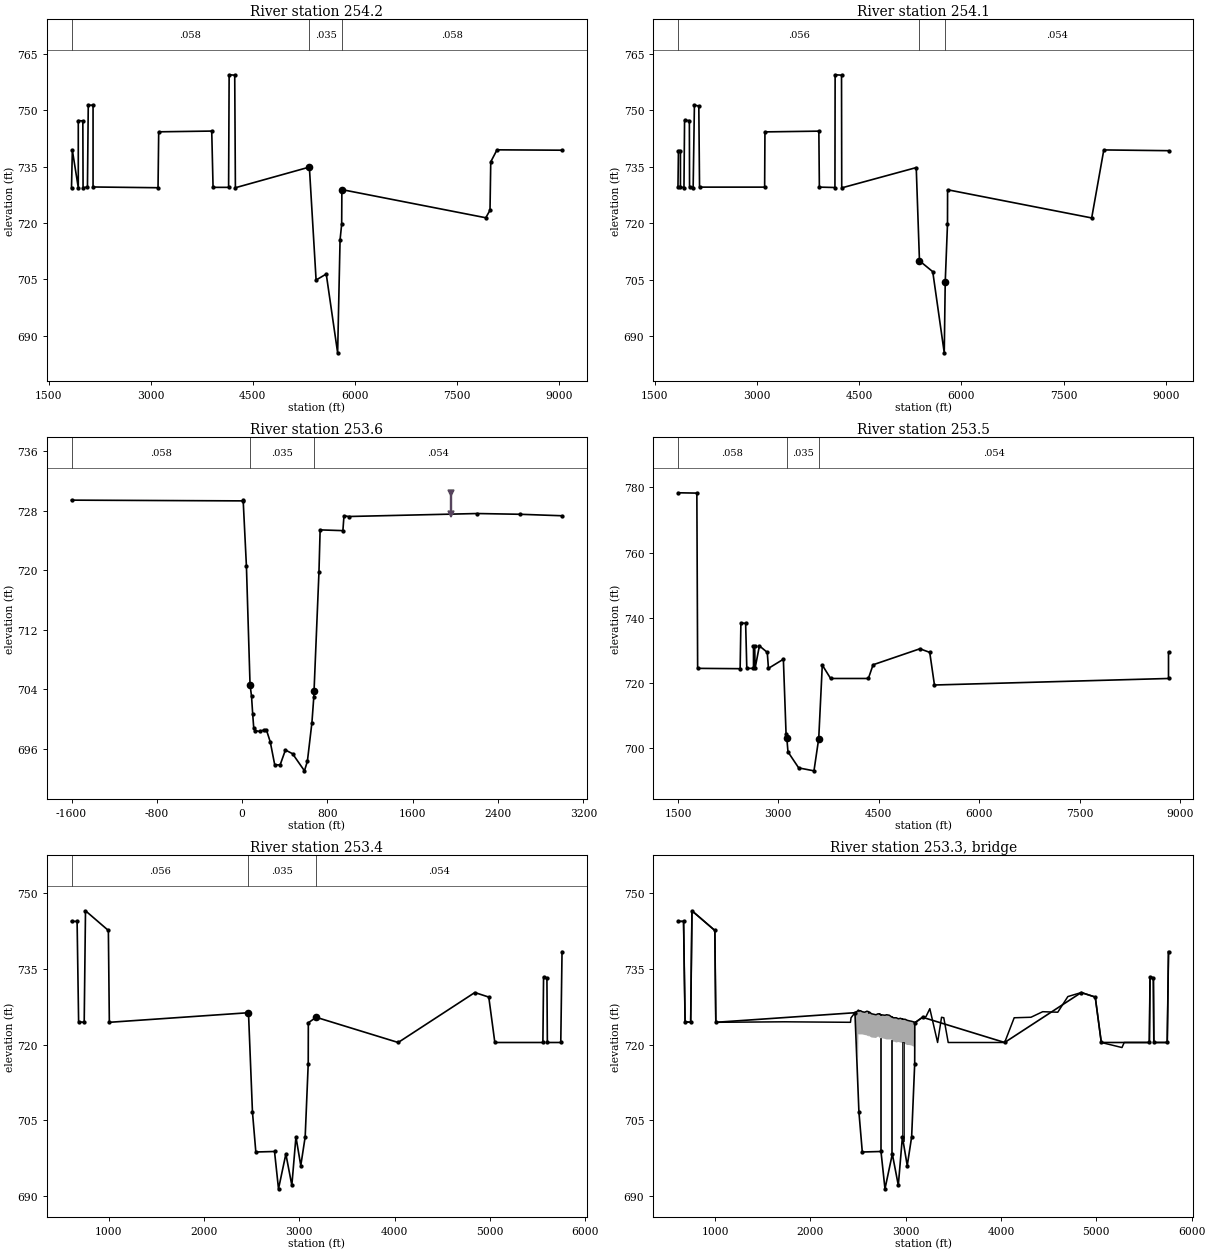
Type RM Length L Ch R = 1 ,254.2   ,121.43,121.43,121.43
BEGIN DESCRIPTION:
Ohio State Route 315 - Downstream Section
END DESCRIPTION:
XS GIS Cut Line= 2
  1822865.194142  715970.4701546 1822967.6726117  715336.7079706
#Sta/Elev= 30
  1836.9   729.4  1849.3   739.4  1936.5   729.4  1936.5   747.3  2003.3   747.2
  2006.8   729.4  2071.1   729.6  2083.1   751.4  2153.4   751.4  2153.4   729.6
  3107.9   729.4  3117.7   744.3  3896.6   744.5  3916.1   729.5  4144.5   729.5
  4152.2   759.5  4234.3   759.4  4244.1   729.4  5330.7   734.9  5429.4   704.8
  5578.6   706.4  5745.9   685.4  5781.5   715.5  5805.3   719.7  5808.2   728.9
  7921.7   721.4    7984   723.4  7994.9   736.3  8086.9   739.5    9042   739.4
#Mann= 3 , 0 , 0
  1836.9    .058       0  5330.7    .035       0  5808.2    .058       0
#XS Ineff= 2 , 0
          5330.7   729.4  5808.2           721.4
Permanent Ineff=
       F       F
#Block Obstruct= 2 , 0
                            6000
Bank Sta=5330.7,5808.2
XS Rating Curve= 0 ,0
Exp/Cntr=0.3,0.1

Type RM Length L Ch R = 1 ,254.1   ,973.27,973.27,973.27
XS GIS Cut Line= 2
   1822992.19356  715945.7818837 1823087.5457316   715356.091134
#Sta/Elev= 30
  1844.2   729.6  1851.1   739.3  1880.4   739.3  1880.4   729.6  1932.1   729.5
  1940.9   747.4  2011.2   747.3    2014   729.7  2066.8   729.5  2085.3   751.4
  2149.8   751.2  2160.5   729.6  3115.2   729.6  3119.6   744.3  3910.2   744.5
  3917.6   729.6    4146   729.5  4148.8   759.5  4242.6   759.4  4245.6   729.4
  5338.2   734.8  5385.6     710  5580.3   707.1  5749.1   685.5  5763.3   704.3
  5796.6   719.8    5798   728.9  7911.1   721.4  8088.7   739.5  9037.6   739.3
#Mann= 3 , 0 , 0
  1844.2    .056       0  5385.6    .035       0  5763.3    .054       0
#Block Obstruct= 2 , 0
                            5950
Bank Sta=5385.6,5763.3
XS Rating Curve= 0 ,0
Exp/Cntr=0.3,0.1

Type RM Length L Ch R = 1 ,253.6   ,610,610,610
BEGIN DESCRIPTION:
AL
END DESCRIPTION:
Node Name=AL
XS GIS Cut Line= 2
   1824073.55393  716248.8665794 1824066.1664777  715533.1869084
#Sta/Elev= 30
   -1600   729.4     4.7   729.3     9.4   729.4      40   720.5    73.9   704.6
      88     703    98.9   700.6   108.4   698.8   123.3   698.4   163.4   698.3
   205.7   698.5   227.5   698.5   263.3   696.9   305.5   693.8   356.1   693.8
   405.6   695.8   472.6   695.3   584.2     693   611.7   694.3   654.2   699.5
   671.5   702.9   674.1   703.8     720   719.7     731   725.4   944.5   725.3
   954.6   727.3   999.2   727.2  2203.5   727.6  2602.4   727.5  2999.1   727.3
#Mann= 3 , 0 , 0
   -1600    .058       0    73.9    .035       0   674.1    .054       0
Levee=0,,,-1,1959.06,730.39,,
#Block Obstruct= 2 , 0
                            1000
Bank Sta=73.9,674.1
XS Rating Curve= 0 ,0
Exp/Cntr=0.3,0.1

Type RM Length L Ch R = 1 ,253.5   ,36.96,36.96,36.96
XS GIS Cut Line= 2
   1824567.08247  716093.3367067 1824864.5402091  715385.6389751
#Sta/Elev= 30
    1500   778.3  1782.1   778.2  1793.9   724.5  2428.7   724.4  2440.4   738.4
    2511   738.3  2528.6   724.5  2628.5   724.5  2628.5   731.4  2646.2   731.4
    2652   724.5  2716.7   731.4  2834.2   729.4  2851.9   724.5  3074.9   727.3
    3115   704.4  3126.2   703.2  3143.8   698.9  3303.8     694  3532.1   693.1
  3603.2     703  3656.4   725.5  3780.6   721.4  4344.8   721.4  4415.4   725.6
  5114.8   730.5  5261.8   729.4  5332.3   719.4  8829.5   721.4  8829.5   729.4
#Mann= 3 , 0 , 0
    1500    .058       0  3126.2    .035       0  3603.2    .054       0
#Block Obstruct= 2 , 0
                            3728
Bank Sta=3126.2,3603.2
XS Rating Curve= 0 ,0
Exp/Cntr=0.3,0.1

Type RM Length L Ch R = 1 ,253.4   ,24.5,24.5,24.5
BEGIN DESCRIPTION:
REPEATED section.  C & O Railroad Bridge - Upstream Section
END DESCRIPTION:
XS GIS Cut Line= 2
   1824524.65014  716298.2805226 1824906.6562666  715397.0267476
#Sta/Elev= 30
   610.1   744.4   668.8   744.4   684.7   724.5   743.3   724.4   756.9   746.5
   996.9   742.6  1007.1   724.4  2467.1   726.3  2508.8   706.6  2544.1   698.7
  2740.2   698.8  2782.1   691.4  2859.2   698.3    2922   692.1    2965   701.7
  3015.7     696  3061.9   701.7  3093.9   716.2    3095   724.3  3176.4   725.4
  4037.7   720.4  4841.8   730.3  4988.3   729.4  5051.9   720.4  5556.1   720.4
  5563.2   733.4  5598.3   733.2    5603   720.4  5743.7   720.4    5757   738.4
#Mann= 3 , 0 , 0
   610.1    .056       0  2467.1    .035       0  3176.4    .054       0
#Block Obstruct= 2 , 0
                            3716
Bank Sta=2467.1,3176.4
XS Rating Curve= 0 ,0
Exp/Cntr=0.3,0.1

Type RM Length L Ch R = 3 ,253.3   ,,,
BEGIN DESCRIPTION:
Structure #12 C & O Railroad Bridge
END DESCRIPTION:
Bridge Culvert--1,0,-1,-1, 0
Deck Dist Width WeirC Skew NumUp NumDn MinLoCord MaxHiCord MaxSubmerge Is_Ogee
1,23,2.6,0, 80, 80, 724.4, , 0.95, 0, 0,0,,
   610.1   668.8   684.7   743.3   756.9   996.9  1007.1  1728.2    2420    2426
  2467.1  2498.9    2500  2503.3  2506.6  2508.8  2525.3  2544.1  2568.3  2592.6
  2610.2  2612.4  2621.2  2622.3  2639.9  2687.3  2710.5    2727  2728.1  2739.1
  2740.2  2782.1  2798.6    2828  2849.3  2850.4  2858.1  2859.2  2873.5  2901.1
    2922  2945.1    2965  2967.2    2976  2977.1  2993.6  3015.7  3036.6  3061.9
  3080.7  3086.2    3093    3095    3095  3176.4  3211.6  3252.7  3334.2  3375.7
  3399.2  3445.6  4037.7  4137.9  4313.7  4436.9  4595.2    4701  4841.8  4988.3
  5051.9  5268.9  5292.4    5433  5556.1  5563.2  5598.3    5603  5743.7    5757
   744.4   744.4   724.5   724.4   746.5   742.6   724.4   724.5   724.4   725.3
   726.3   726.7   726.8   726.8   726.8   726.6   726.7   726.5   726.4   726.6
   726.5   726.2   726.4   726.4   726.1   725.9   726.1     726   726.1   725.8
   725.9   725.8   725.9   725.8   725.5   725.5   725.5   725.4   725.3   725.3
   725.1   725.2     725   725.1     725     725     725   724.8   724.7   724.6
   724.5   724.4   724.4   724.4   724.3   725.4   725.5   727.1   720.4   725.4
   725.3   720.4   720.4   725.3   725.4   726.5   726.4   729.5   730.3   729.4
   720.4   719.4   720.4   720.4   720.4   733.4   733.2   720.4   720.4   738.4
   744.4   744.4   724.5   724.4   746.5   742.6   724.4   724.5   724.4   725.3
   726.3   717.4   717.4     722   722.1     722     722     722   721.9   721.8
   721.6   721.8   721.6   721.6   721.4   721.3   721.6   721.3   721.4   721.3
   721.3   721.1     721     721     721     721   720.7   720.4   720.6   720.4
   720.5   720.4   720.3   720.4   720.4   720.3   720.1   719.9   719.9   719.8
   719.6   719.6   719.4   719.3   724.3   725.4   725.5   727.1   719.6   725.4
   725.3   720.4   720.4   725.3   725.4   726.5   726.4   729.5   730.3   729.4
   720.4   719.4   720.4   720.4   720.4   733.4   733.2   720.4   720.4   738.4
   610.1   668.8   684.7   743.3   756.9   996.9  1007.1  1728.2    2420    2426
  2467.1  2498.9    2500  2503.3  2506.6  2508.8  2525.3  2544.1  2568.3  2592.6
  2610.2  2612.4  2621.2  2622.3  2639.9  2687.3  2710.5    2727  2728.1  2739.1
  2740.2  2782.1  2798.6    2828  2849.3  2850.4  2858.1  2859.2  2873.5  2901.1
    2922  2945.1    2965  2967.2    2976  2977.1  2993.6  3015.7  3036.6  3061.9
  3080.7  3086.2    3093    3095    3095  3176.4  3211.6  3252.7  3334.2  3375.7
  3399.2  3445.6  4037.7  4137.9  4313.7  4436.9  4595.2    4701  4841.8  4988.3
  5051.9  5268.9  5292.4    5433  5556.1  5563.2  5598.3    5603  5743.7    5757
   744.4   744.4   724.5   724.4   746.5   742.6   724.4   724.5   724.4   725.3
   726.3   726.7   726.8   726.8   726.8   726.6   726.7   726.5   726.4   726.6
   726.5   726.2   726.4   726.4   726.1   725.9   726.1     726   726.1   725.8
   725.9   725.8   725.9   725.8   725.5   725.5   725.5   725.4   725.3   725.3
   725.1   725.2     725   725.1     725     725     725   724.8   724.7   724.6
   724.5   724.4   724.4   724.4   724.3   725.4   725.5   727.1   720.4   725.4
   725.3   720.4   720.4   725.3   725.4   726.5   726.4   729.5   730.3   729.4
   720.4   719.4   720.4   720.4   720.4   733.4   733.2   720.4   720.4   738.4
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Pier Skew, UpSta & Num, DnSta & Num=  ,2616.8, 2 ,2616.8, 2 , 0 , 0 , 0 ,,
    12.1     8.8
   700.1   721.8
    12.1     8.8
   700.1   721.8
Pier Skew, UpSta & Num, DnSta & Num=  ,2732.6, 2 ,2732.6, 2 , 0 , 0 , 0 ,,
    13.2      11
   698.5   721.4
    13.2      11
   698.5   721.4
Pier Skew, UpSta & Num, DnSta & Num=  ,2854.3, 2 ,2854.3, 2 , 0 , 0 , 0 ,,
     9.9     7.7
   698.2     721
     9.9     7.7
   698.2     721
Pier Skew, UpSta & Num, DnSta & Num=  ,2971.6, 2 ,2971.6, 2 , 0 , 0 , 0 ,,
    12.1     8.8
   701.5   720.4
    12.1     8.8
   701.5   720.4
BR Coef=-1 , 0 , 0 ,, 0 ,,,0.8,-1,,0,
WSPro=,,,, 1 ,,,, 0 ,,,, 0 ,,,,-1 ,-1 ,-1 , 0 , 0 , 0 , 0 , 0
BC Design=,, 0 ,, 0 ,,,,,,
BC HTab HWMax=746.5
BC Use User HTab Curves=0
BC User HTab FreeFlow(D)= 0

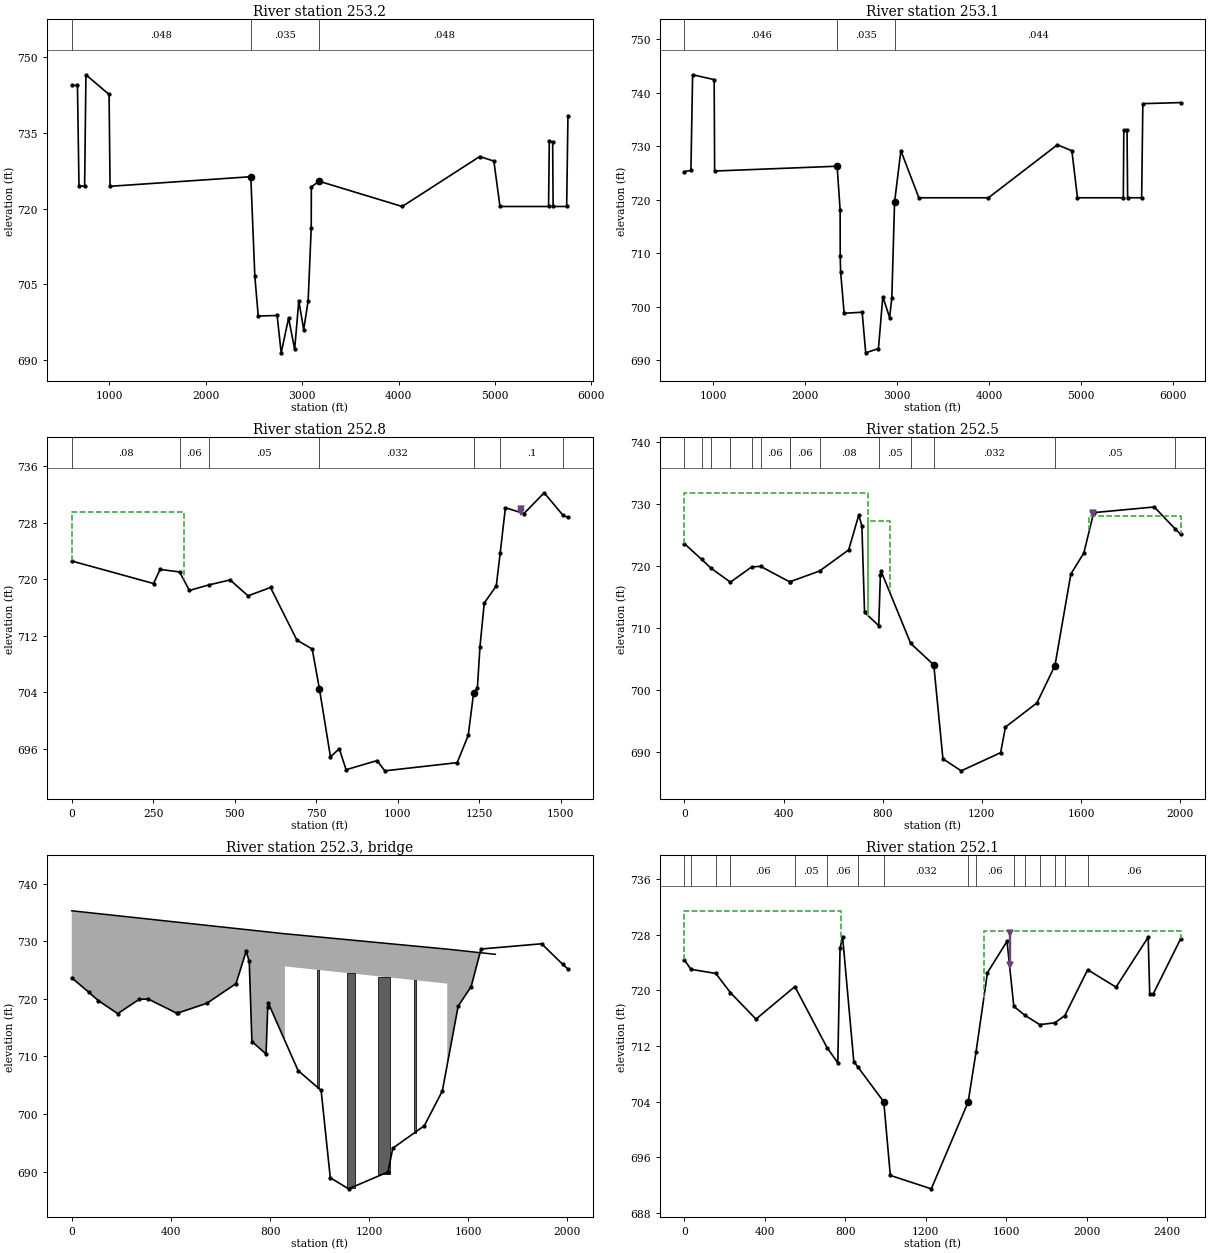
Type RM Length L Ch R = 1 ,253.2   ,52,52,52
BEGIN DESCRIPTION:
C & O Railroad Bridge - Downstream Section
END DESCRIPTION:
XS GIS Cut Line= 2
  1824570.961399  716283.8300921 1824940.7224714  715411.4660232
#Sta/Elev= 30
   610.1   744.4   668.8   744.4   684.7   724.5   743.3   724.4   756.9   746.5
   996.9   742.6  1007.1   724.4  2467.1   726.3  2508.8   706.6  2544.1   698.7
  2740.2   698.8  2782.1   691.4  2859.2   698.3    2922   692.1    2965   701.7
  3015.7     696  3061.9   701.7  3093.9   716.2    3095   724.3  3176.4   725.4
  4037.7   720.4  4841.8   730.3  4988.3   729.4  5051.9   720.4  5556.1   720.4
  5563.2   733.4  5598.3   733.2    5603   720.4  5743.7   720.4    5757   738.4
#Mann= 3 , 0 , 0
   610.1    .048       0  2467.1    .035       0  3176.4    .048       0
#Block Obstruct= 2 , 0
                            3170
Bank Sta=2467.1,3176.4
XS Rating Curve= 0 ,0
Exp/Cntr=0.3,0.1

Type RM Length L Ch R = 1 ,253.1   ,383.49,286.82,110
XS GIS Cut Line= 2
  1824648.878238  716188.6724741 1824975.3290295  715418.4889751
#Sta/Elev= 30
   683.9   725.3   754.5   725.5     773   743.4  1007.5   742.5  1012.8   725.4
  2346.2   726.3  2378.9   718.1  2379.9   709.5  2384.3   706.5  2422.7   698.8
  2618.8     699  2657.3   691.4  2796.1   692.2  2843.6   701.9  2917.4     698
  2941.7   701.7  2971.7   719.6  3040.2   729.2  3236.2   720.4  3993.7   720.4
  4743.7   730.3  4901.8   729.2  4962.7   720.4  5461.8   720.4  5467.1   733.1
  5502.3   733.1  5508.9   720.4  5661.5   720.4  5674.5     738  6085.6   738.2
#Mann= 3 , 0 , 0
   683.9    .046       0  2346.2    .035       0  2971.7    .044       0
#Block Obstruct= 2 , 0
                            3075
Bank Sta=2346.2,2971.7
XS Rating Curve= 0 ,0
Exp/Cntr=0.3,0.1

Type RM Length L Ch R = 1 ,252.8   ,816.3,590.47,312.21
BEGIN DESCRIPTION:
Overbank geometry from 2011 City of Columbus LiDAR data.  Channel geometry from proposed design plans.
END DESCRIPTION:
XS GIS Cut Line= 3
1825059.28161752716827.0005937671825102.24511428715305.381917849
 1825102.2453968715305.371912071
#Sta/Elev= 30
       0  722.55  250.87  719.36  270.86  721.36  330.83     721  360.82  718.38
  420.79  719.17  485.75  719.87  540.72  717.62  609.69   718.8  690.65  711.35
  737.62  710.09  759.86  704.41  793.59  694.82  820.58  695.96  841.57     693
  936.52  694.29  960.51  692.84 1182.39     694 1216.37  697.88 1232.68  703.86
 1244.36   704.6 1252.35  710.44 1265.35  716.59 1302.33  719.03 1314.32723.6766
 1330.31  730.09 1387.28  729.27 1449.25  732.21 1507.23  729.01 1522.23  728.73
#Mann= 7 ,-1 , 0
       0     .08       0  330.83     .06       0  420.79     .05       0
  759.86    .032       0 1232.68     .04       0 1314.32      .1       0
 1507.23     .05       0
Levee=0,,,-1,1377,729.9,,
#XS Ineff= 2 , 0
       0   344.3   729.5               0
Permanent Ineff=
       F       F
Bank Sta=759.86,1232.68
XS Rating Curve= 0 ,0
Exp/Cntr=0.5,0.3

Type RM Length L Ch R = 1 ,252.5   ,194.58,195.03,226.52
BEGIN DESCRIPTION:
Overbank geometry from 2011 City of Columbus LiDAR data.  Channel geometry from proposed design plans.
END DESCRIPTION:
Node Name=AK
XS GIS Cut Line= 3
   1826550.36066   716753.121805   1825271.62404   715427.642828
   1825112.98591   715273.159541
#Sta/Elev= 30
       0  723.64  68.881  721.13 106.723   719.7 185.297  717.43 271.644   719.9
 307.545  719.98 423.961  717.49 427.842  717.53 545.238  719.23 662.625  722.64
 703.377  728.25 715.991   726.5 726.664  712.58 783.902  710.41 790.694  718.63
 793.605  719.19 912.932  707.551006.022  704.091042.932  688.931116.665     687
1275.764  689.93 1295.17  694.06 1422.25  697.951494.983  703.991559.042  718.74
1611.428  722.131651.201  728.651895.705  729.56 1980.19  726.012001.924  725.17
#Mann= 14 ,-1 , 0
       0     .08       0  68.881     .06       0 106.723     .08       0
 185.297     .06       0 271.644     .05       0 307.545     .06       0
 423.961     .05       0 427.842     .06       0 545.238     .08       0
 783.902     .05       0 912.932     .04       01006.022    .032       0
1494.983     .05       0 1980.19     .06       0
Levee=0,,,-1,1650.25,728.6,,
#XS Ineff= 3 ,-1
       0  741.41  731.85  741.41 828.637  727.371633.2652132.122  728.08
Permanent Ineff=
       F       F       F
Bank Sta=1006.022,1494.983
XS Rating Curve= 0 ,0
Skew Angle= 14
Exp/Cntr=0.5,0.3

Type RM Length L Ch R = 3 ,252.3   ,,,
BEGIN DESCRIPTION:
Norfolk Southern Railroad Bridge
Geometry from plans provided by Norfolk Southern.  Top chord elevations adjusted using 2011 City of Columbus LiDAR data.
END DESCRIPTION:
Bridge Culvert--1,0,-1,-1, 0
Deck Dist Width WeirC Skew NumUp NumDn MinLoCord MaxHiCord MaxSubmerge Is_Ogee
118,29.5,2.6,14, 6, 8, , , 0.98, 0, 0,0,,
       0 859.866 859.8661514.8161514.8161708.876
  735.29   731.3   731.3  728.63  728.63  727.73
             680  725.63  722.64     680
-196.762  57.429 810.789 810.7891457.6351457.6352084.1262321.029
  736.03  734.84   731.3   731.3  728.63  728.63  725.69  724.58
                     680  725.63  722.64     680
Pier Skew, UpSta & Num, DnSta & Num=  ,993.282, 2 ,953.644, 2 , 0 , 0 , 0 ,,
       8    4.99
     690   725.2
       8    4.99
     690   725.2
Pier Skew, UpSta & Num, DnSta & Num=  ,1126.696, 4 ,1087.057, 4 , 0 , 0 , 0 ,,
    32.3   11.69    7.57    4.99
     690  694.95  694.95  724.55
    32.3   11.69    7.57    4.99
     690  694.95  694.95  724.55
Pier Skew, UpSta & Num, DnSta & Num=  ,1260.113, 7 ,1220.474, 7 , 0 , 0 , 0 ,,
   46.53   26.12      22      22      10    9.26       6
     690  694.95  694.95  704.84  706.67  721.32  724.02
   46.53   26.12      22      22      10    9.26       6
     690  694.95  694.95  704.84  706.67  721.32  724.02
Pier Skew, UpSta & Num, DnSta & Num=  ,1383.825, 2 ,1344.185, 2 , 0 , 0 , 0 ,,
       8    4.99
     690  723.26
       8    4.99
     690  723.26
BR Coef=-1 , 0 , 0 ,1.25, 0 ,,,0.8,-1,2,1,
WSPro=,,,, 1 ,,,, 0 ,,,, 0 ,,,,-1 ,-1 ,-1 , 0 , 0 , 0 , 0 , 0
BR U #Sta/Elev= 495
       0  723.64   3.639  723.48   7.277  723.51  13.332  723.62  15.758  723.83
  23.034  723.42  33.951  723.09  42.431  722.82  53.347  722.42  64.253  721.87
  75.169  721.33  78.808     721  84.862  720.77  89.713  720.47  93.352   720.3
 101.842  719.96 106.693  719.72 113.961  719.34 132.144  718.25  134.57  718.16
 140.634  717.99 144.273  717.83 147.912  717.78  151.55  717.68 153.977  717.52
 157.605  717.15 161.243  717.21 164.882   717.2 169.734  717.31  172.16  717.22
 175.798   717.2 178.224   717.1 183.065   717.1 184.279  717.24 186.704  717.58
 187.918  717.62 191.555  717.58 198.833  717.62 201.259  717.75 202.471  717.95
 203.674  718.35 206.101  719.29 208.527  719.41 213.378  719.33 217.017  719.36
 220.655  719.15 226.719  719.21 230.349  719.32   235.2  719.33 241.264  719.28
  243.69  719.29 247.329  719.38 250.967  719.38 253.383  719.51 257.022  719.49
  260.66   719.4 264.299  719.42 270.363  719.41 274.002  719.34 276.418  719.38
 284.908  719.34  289.76  719.37 292.185  719.45 293.398  719.41 300.665  719.54
 304.304  719.52  306.73  719.45 309.155  719.47 314.007  719.45 317.645  719.37
 321.284   719.4 328.552  719.39 329.764  719.36 334.616  719.38 335.829  719.35
 345.532  719.35 346.744  719.27 350.374  718.71   352.8  718.59 356.438  718.66
 360.077  718.64 362.503  718.59 366.141  718.58 368.567  718.41  369.78  718.26
  378.26  718.25 383.112  718.11 387.963  717.63 391.602  717.46  395.24  717.47
 400.082  717.32 404.933  717.32 408.572  717.27 410.998  717.29 413.423  717.23
  415.85  717.26 419.488  717.16 423.116  717.16  424.33  717.16 427.969  717.14
  432.82  717.19 438.884  717.17 443.735  717.19 447.364  717.12 452.216  716.96
 455.854  717.02 459.493  717.31 465.558  717.53 469.197  717.62 472.825  717.94
 476.464  718.02  478.89  718.12 489.805  718.31 493.444   718.3 501.924  718.22
 505.563  718.07 511.628  717.94 516.479   717.6 517.692  717.67 521.321  718.16
 522.533  718.21 526.172   718.2 528.598  718.32 532.236  718.38 535.875  718.39
 539.513  718.52 543.142  718.59 545.569  718.71 547.994  718.74  550.42  718.88
 556.484  718.99 557.697  719.04 560.123  719.03 562.549  718.96 566.177  719.08
 573.454  719.19 577.093  719.21 579.519  719.29 581.944  719.28 586.796   719.4
 589.212  719.42 592.851  719.56  596.49  719.96 598.915  720.12 603.766  720.09
 608.618  720.21 615.885  720.24 618.311  720.37 620.737  720.43 628.014  720.75
 634.079  720.93 637.706  721.07 640.133  721.26 642.559  721.35 646.198  721.63
 649.836   721.8 654.688  722.09 663.167  722.57 668.021     723 671.659  723.42
  676.51   724.1 680.149  724.75  684.99  725.49 691.054  726.23 695.906  726.72
 698.332  727.03  701.97  727.37 704.396  727.37   705.6  727.31 709.237  726.97
 710.451  726.78 712.876  726.19  714.09  725.47 715.302  723.77 716.515  721.24
 718.941  715.13 720.154  712.99 721.366   712.5 725.005  712.02 726.218  711.94
  731.06  711.79 735.911  711.52 738.336  711.32 741.975  711.19 745.614  710.95
 750.466  710.78 754.094  710.54 758.946  710.37 762.584  710.13 765.011  710.05
 768.649  709.79 773.501  709.51 774.713  709.52  777.13  709.85 778.342  709.94
 781.981  709.97 783.194  710.44  785.62  713.32 789.257  717.44 790.471  718.43
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BR U #Mann= 14
       0     .08  64.253     .06 106.693     .08 184.279     .06 264.299     .05
 304.304     .06 423.116     .05  424.33     .06 543.142     .08 783.194     .05
 912.427     .041006.041    .0321495.012     .05 1980.19     .06
BR U Banks=1006.041,1495.012
BR D #Sta/Elev= 495
       0  724.35    4.99  724.12    7.49   724.1   11.24  724.51   12.48  724.53
   17.48  724.19   27.46  723.29   32.46  723.02    41.2   722.2   44.94  721.96
   57.42   721.9   66.16  721.81   67.41  721.84   86.14  723.06   92.38  723.02
  101.12   723.1  107.36  723.09  117.34   723.3   147.3  722.83  156.04  722.43
  162.28  722.08  169.77  721.84  177.26  721.44     186  721.23  189.75  721.08
  199.73  720.89  205.98  720.56  209.72  720.44  213.47  720.17  223.45  719.73
  228.45  719.68  239.68   719.2  244.67  718.82  249.67  718.12  252.16  717.92
  255.91  717.43   260.9  717.26  269.64  717.26  272.14  717.18  277.13  717.18
  283.37   716.9  287.12  716.67  290.86  716.82   302.1  716.91  308.34  717.08
  314.58  717.12  323.32  717.08  329.56  716.97  333.31  716.82  339.55  716.72
  342.04  716.54  349.53  716.28  355.78  715.87  360.77  716.14  367.01   716.4
  369.51  716.61  378.25  717.93  383.24  718.76  386.98  719.12  390.73  719.24
  395.72   719.7  400.72  719.99  406.96   720.6 415.699   721.1  419.44  721.18
  425.68  721.18  428.18  721.12  435.67  721.72  439.41  721.86   446.9  721.78
   449.4  721.92   451.9   721.9  458.14   722.1  464.38  722.18  466.88  722.15
  473.12  722.25  476.86  722.18  484.35  722.24   490.6  722.15  494.34  721.93
  496.84  721.92  503.08  721.72  511.82  721.62  523.05   721.3  525.55   721.3
  530.54  721.14  535.54  721.09  546.77   720.7  549.27  720.54  551.76  720.54
  559.25   720.3     563  720.02  566.74  719.99  572.99  719.75 576.729  719.48
  580.48  719.42  591.71  719.56  595.46  719.43  604.19  719.25  607.94  718.95
  611.68  718.79  621.67  718.13  625.42  717.98  631.66  717.48  634.15  717.45
   637.9  716.94  649.13  716.34  652.87  715.94  660.35  715.56  666.59  715.43
  674.07  714.83  677.81   714.4  685.29  713.98  690.28  713.56  696.52  712.95
  705.25  712.45  708.99  711.78  710.23  711.64  720.21  710.99   725.2  710.76
  728.94  710.43  732.68  710.27 740.159   709.8  747.65  709.41  751.39  709.14
  756.37  709.46  761.36  709.46  762.61  709.59  763.86  710.35 765.099  712.42
  766.35   714.8 767.599  716.56  768.85  719.05  770.09  720.65  771.34  722.85
  772.59  724.59  773.83  726.03  775.08  726.25  778.82  727.36  781.32   727.8
  786.39  727.73  787.38  727.64 789.371  727.08  794.35  725.32  816.23  718.77
  829.23   714.5  838.22  711.23  842.22  709.77  844.22  709.35 863.777  708.94
 866.202  708.87 869.598  708.79 872.014  708.72 879.292  708.54 885.113  708.53
 895.787  708.18 901.114     708 907.422  707.64 909.361  707.54 916.153  707.15
 920.521  706.94  922.46  706.86 924.886  706.74 926.826  706.66 929.242  706.54
 931.183  706.46 933.609  706.34 939.431  706.08 942.827  705.94 947.678  705.77
 952.044   705.6 961.738  705.26 967.074  705.06 969.015     705 972.411  704.84
 977.748  704.61 983.569  704.35 986.956  704.19 989.381  704.09 991.322  703.99
 993.748  703.231007.817  698.591008.302  698.421022.362  692.991023.332  692.69
1023.817  692.631032.065  692.751042.253  692.911046.609  692.86 1047.58  692.86
1052.916   692.81053.887   692.81059.223  692.741062.134  692.721066.986  692.59
1076.679  692.32 1079.59  692.231085.412  692.231085.897  692.221106.263  692.22
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BR D #Mann= 16
       0     .08   32.46     .06  156.04     .05  228.45     .06  549.27     .05
  708.99     .06 863.777     .04 991.322    .0321410.849     .04 1450.02     .06
 1637.95     .08 1694.17     .06 1766.63     .08 1841.59     .06 1891.57     .08
 2005.26     .06
BC Design=,, 0 ,, 0 ,,,,,,
BC Use User HTab Curves=0
BC User HTab FreeFlow(D)= 0

Type RM Length L Ch R = 1 ,252.1   ,224.67,252.61,290.84
BEGIN DESCRIPTION:
Overbank geometry from 2011 City of Columbus LiDAR data.  Channel geometry from proposed design plans.
END DESCRIPTION:
XS GIS Cut Line= 6
   1826762.92421   716582.237304   1826292.09083   716142.654193
   1826143.30143   716056.178645   1825606.04922   715544.772187
   1824970.63252   714894.0428461824903.85249717714825.653519359
#Sta/Elev= 30
       0  724.35   32.46  723.02  156.04  722.43  228.45  719.68  355.78  715.87
  549.27  720.54  708.99  711.78  762.61  709.59  773.83  726.03  786.39  727.73
  842.22  709.77 863.777  708.94 991.322  703.991023.817  693.421227.511  691.49
1410.849  703.96 1450.02  711.13    1507  722.55 1604.21  727.05 1637.95   717.7
 1694.17   716.4 1766.63  715.08 1841.59  715.33 1891.57  716.37 2005.26  722.96
 2146.43  720.46 2306.33  727.642313.822  719.49 2331.31  719.49 2467.48  727.39
#Mann= 16 ,-1 , 0
       0     .08       0   32.46     .06       0  156.04     .05       0
  228.45     .06       0  549.27     .05       0  708.99     .06       0
 863.777     .04       0 991.322    .032       01410.849     .04       0
 1450.02     .06       0 1637.95     .08       0 1694.17     .06       0
 1766.63     .08       0 1841.59     .06       0 1891.57     .08       0
 2005.26     .06       0
Levee=0,,,-1,1616.71,728.3,,
#XS Ineff= 2 , 0
       0  779.29  731.43 1489.13       0  728.47
Permanent Ineff=
       F       F
Bank Sta=991.322,1410.849
XS Rating Curve= 0 ,0
Skew Angle= 14
Exp/Cntr=0.5,0.3

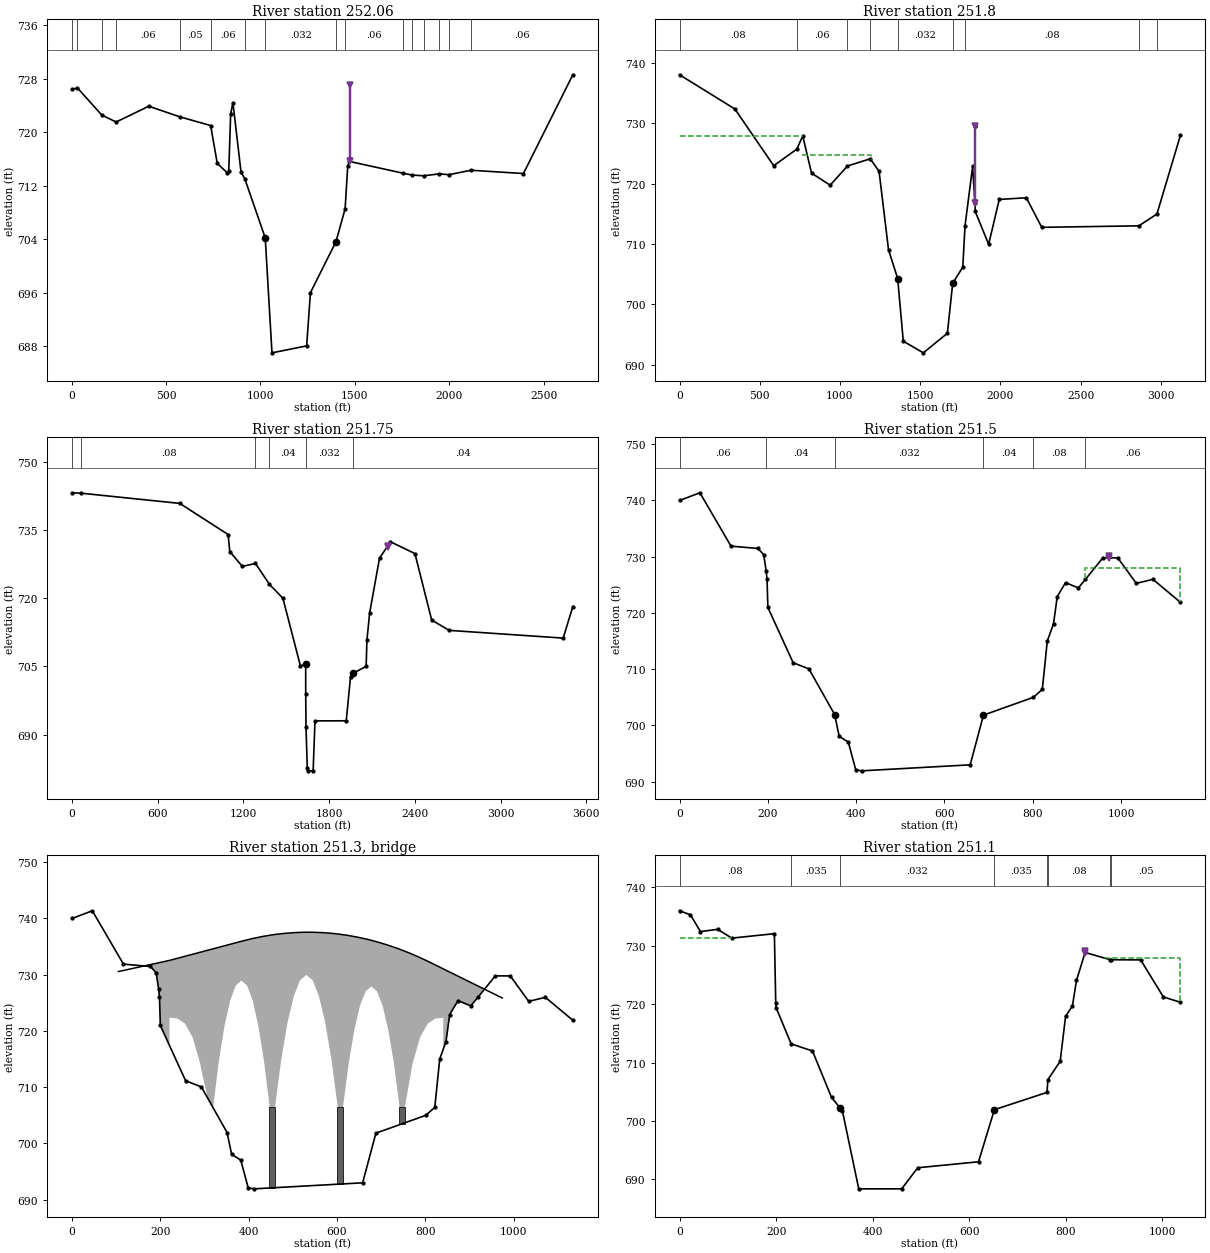
Type RM Length L Ch R = 1 ,252.06  ,371.37,352.86,335.57
BEGIN DESCRIPTION:
Overbank geometry from 2011 City of Columbus LiDAR data.  Channel geometry from proposed design plans.
END DESCRIPTION:
XS GIS Cut Line= 5
   1826944.72995   716557.711762   1826205.14645   715813.961937
   1825680.14652   715222.295142   1825513.47986   715024.378543
    1825000.9799   714807.711981
#Sta/Elev= 30
    1.25  726.39   29.97  726.59  158.98  722.54  234.97   721.5  407.95  723.86
  570.93  722.29  735.91  720.97  770.91  715.31   823.9   713.9   831.9  714.19
   841.9   722.7   853.9  724.38   896.9  714.01  916.89  713.01 1025.13  704.18
 1060.86     687 1244.64  688.04 1264.61  695.99 1400.05  703.62 1448.39  708.52
 1462.37  714.96 1471.36  715.61 1755.01  713.85 1800.95  713.58 1864.88  713.46
  1946.8  713.75 1998.75  713.63 2115.63  714.29 2393.35   713.8 2655.07  728.56
#Mann= 16 ,-1 , 0
    1.25     .08       0   29.97     .06       0  158.98     .05       0
  234.97     .06       0  570.93     .05       0  735.91     .06       0
  916.89     .04       0 1025.13    .032       0 1400.05     .04       0
 1448.39     .06       0 1755.01     .08       0 1800.95     .06       0
 1864.88     .08       0  1946.8     .06       0 1998.75     .08       0
 2115.63     .06       0
Levee=0,,,-1,1472.36,727,,
#XS Ineff= 2 , 0
       0   850.9  723.79               0
Permanent Ineff=
       F       F
Bank Sta=1025.13,1400.05
XS Rating Curve= 0 ,0
Exp/Cntr=0.3,0.1

Type RM Length L Ch R = 1 ,251.8   ,433.64,366.02,306.26
BEGIN DESCRIPTION:
Overbank geometry from 2011 City of Columbus LiDAR data.    Channel geometry from proposed design plans.
END DESCRIPTION:
XS GIS Cut Line= 4
1827472.38998027716511.9359351841825733.71924503714878.126866847
1825008.25645711714749.1487783491825008.19732577714749.138265546
#Sta/Elev= 30
       0  738.01  344.94  732.34  586.97  722.95  730.95  725.69  767.95  727.87
  822.95  721.72  938.94  719.72 1046.93   722.9 1188.92  724.09 1243.92  722.02
 1302.91  709.02 1359.95  704.26  1394.9  693.88 1519.89  691.95 1669.88  695.19
 1702.95  703.46 1765.88  706.15 1779.87  712.98 1827.47  722.84    1841  716.85
    1841  729.55    1843  729.55    1843  715.41 1927.19  709.93 1993.43  717.36
 2162.15  717.64 2258.38  712.74  2864.2  712.99  2976.6  714.95 3122.73  727.96
#Mann= 9 ,-1 , 0
       0     .08       0  730.95     .06       0 1046.93     .08       0
 1188.92     .04       0 1359.95    .032       0 1702.95     .04       0
 1779.87     .08       0  2864.2     .06       0  2976.6     .08       0
Levee=0,,,-1,1841,729.55,,
#XS Ineff= 2 ,-1
       0  765.67   727.9  765.67 1195.56  724.69
Permanent Ineff=
       F       F
Bank Sta=1359.95,1702.95
XS Rating Curve= 0 ,0
Exp/Cntr=0.3,0.1

Type RM Length L Ch R = 1 ,251.75  ,405.37,275.3,167.66
BEGIN DESCRIPTION:
Overbank geometry from 2011 City of Columbus LiDAR data.  Channel geometry from proposed design plans.
END DESCRIPTION:
XS GIS Cut Line= 5
1828117.20168278716194.0865052641827214.42396078715564.746228516
1826348.89649236 715055.628480361825800.97993727714822.295285597
 1825011.3965427714661.878611684
#Sta/Elev= 30
       0  743.23    66.2  743.13  754.48  740.89 1092.49  734.04 1104.48  730.28
 1192.41  727.02 1284.33  727.67 1382.25  723.06 1476.17  720.02 1599.06  705.08
 1635.84   705.5 1636.03  698.95 1638.03  691.58 1647.02   682.6 1651.28     682
 1687.99     682 1700.98     693 1919.79  693.02 1949.77  702.73 1966.67  703.48
 2059.03     705 2064.67  710.83 2083.66  716.78  2152.6  728.82 2229.53  732.44
 2400.57  729.84 2517.94   715.2  2640.3  712.93 3438.48  711.23 3505.94  718.18
#Mann= 6 ,-1 , 0
       0     .06       0    66.2     .08       0 1284.33     .05       0
 1382.25     .04       0 1635.84    .032       0 1966.67     .04       0
Levee=0,,,-1,2210,731.4,,
Bank Sta=1635.84,1966.67
XS Rating Curve= 0 ,0
Exp/Cntr=0.5,0.3

Type RM Length L Ch R = 1 ,251.5   ,243.88,274.25,267.45
BEGIN DESCRIPTION:
Overbank geometry from 2011 City of Columbus LiDAR data.  Channel geometry from proposed design plans.
END DESCRIPTION:
Node Name=AJ
XS GIS Cut Line= 2
1827350.66056494 715094.145463691826160.55402127714892.372245193
#Sta/Elev= 30
       0  739.99  46.007  741.36 116.437  731.88  177.47  731.46 190.617  730.36
 196.245  727.38 198.125  725.98 200.004  720.98 257.278  711.15 292.959  710.06
 351.182  701.95 361.509  698.08 382.164  697.05 399.069  692.12 412.215  691.94
 658.226  693.01 688.278  701.84  801.17     705 821.611  706.41 832.878  715.02
 846.964  718.08 855.412  722.92 874.187  725.38 903.298  724.46 919.264  725.97
 958.693  729.79 992.503  729.791034.489  725.261072.067  725.981134.294   721.9
#Mann= 6 ,-1 , 0
       0     .06       0 196.245     .04       0 351.182    .032       0
 688.278     .04       0  801.17     .08       0 919.264     .06       0
Levee=0,,,-1,972.22,730.08,,
#XS Ineff= 2 , 0
       0 142.242  731.57 919.311       0     728
Permanent Ineff=
       F       F
Bank Sta=351.182,688.278
XS Rating Curve= 0 ,0
Skew Angle= 20
Exp/Cntr=0.5,0.3

Type RM Length L Ch R = 3 ,251.3   ,,,
BEGIN DESCRIPTION:
Broad Street Bridge
Geometry from plans provided by the Franklin County Engineer's Office.
END DESCRIPTION:
Bridge Culvert--1,0,-1,-1, 0
Deck Dist Width WeirC Skew NumUp NumDn MinLoCord MaxHiCord MaxSubmerge Is_Ogee
70,98,2.6,20, 80, 79, , , 0.98, 0, 0,0,,
 105.226 199.196 220.677 220.677 222.688 238.109 246.181  255.54 269.673 272.971
 290.403 293.165 307.834 316.657  319.58 332.406  340.15 345.233  358.06 363.643
 370.887 383.714 387.135 396.541 409.367 410.627 422.194 434.119 435.021 447.848
 457.612 459.594  473.83 481.104 488.067 502.303 504.596  516.54 528.088 530.776
 545.013 551.581 559.248 573.485 575.074 587.721 598.565 601.958 613.703 622.058
  626.53 639.357  645.55 652.184 665.011 669.043 677.838 690.664 692.534 703.492
 716.027 716.318 729.145 739.519 741.972 753.718 763.012  771.15 786.503 788.581
 806.012 809.996 823.444 833.489 840.875 840.875 853.354 856.981 880.474 974.443
  730.56  732.17  732.54  732.54  732.58   732.9  733.07  733.27  733.56  733.63
  733.99  734.05  734.36  734.54   734.6  734.87  735.03  735.14   735.4  735.52
  735.67  735.94  736.01  736.19  736.44  736.46  736.64  736.83  736.84  737.01
  737.13  737.15  737.28  737.34  737.38  737.47  737.48  737.52  737.55  737.55
  737.54  737.53   737.5  737.45  737.44  737.35  737.27  737.23  737.11  737.02
  736.96  736.78  736.69  736.58  736.36  736.29  736.11  735.84   735.8  735.54
  735.24  735.23  734.89  734.61  734.53  734.17  733.89  733.62   733.1  733.02
  732.38  732.23  731.71  731.32  731.03  731.03  730.55  730.41   729.5  725.86
                     690  722.36  722.35  722.23  721.82  721.34  719.37  718.91
  714.19  712.96   706.4   706.4   706.4  714.53  718.34  720.84  725.35  726.53
  728.06  728.96  728.72  728.06  725.35  724.91  720.84  714.97  714.53   706.4
   706.4   706.4  714.87  718.24  721.47  726.19  726.65  729.02  729.78  729.96
  729.02  727.71  726.19  721.47  720.73  714.87  708.42   706.4   706.4  711.46
  714.17  720.17  722.25  724.48  727.06  727.33  727.92  727.06  726.68  724.48
  720.27  720.17  714.17  707.89   706.4   706.4  710.55  714.18  718.34   718.9
  721.33  721.53  722.22  722.29  722.35     690
 168.571 183.682 183.682 185.693 201.113 209.184 218.545 232.677 235.976 253.407
  256.17 270.839 279.662 282.584 295.411 303.155 308.238 321.065 326.646 333.891
 346.718 350.139 359.545 372.372 373.631 385.199 397.124 398.026 410.853 420.615
 422.599 436.835 444.108 451.072 465.308 467.601 479.544 491.093  493.78 508.017
 514.585 522.253  536.49 538.077 550.726  561.57 564.961 576.708 585.062 589.535
 602.362 608.554 615.188 628.015 632.046 640.842 653.669 655.539 666.496 679.032
 679.323  692.15 702.523 704.976 716.723 726.016 734.154 749.508 751.584 769.016
 773.001 786.447 796.493 803.878 803.878 816.358 819.985 843.477 937.447
  732.28  732.54  732.54  732.58   732.9  733.07  733.27  733.56  733.63  733.99
  734.05  734.36  734.54   734.6  734.87  735.03  735.14   735.4  735.52  735.67
  735.94  736.01  736.19  736.44  736.46  736.64  736.83  736.84  737.01  737.13
  737.15  737.28  737.34  737.38  737.47  737.48  737.52  737.55  737.55  737.54
  737.53   737.5  737.45  737.44  737.35  737.27  737.23  737.11  737.02  736.96
  736.78  736.69  736.58  736.36  736.29  736.11  735.84   735.8  735.54  735.24
  735.23  734.89  734.61  734.53  734.17  733.89  733.62   733.1  733.02  732.38
  732.23  731.71  731.32  731.03  731.03  730.55  730.41   729.5  725.86
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Pier Skew, UpSta & Num, DnSta & Num=  ,313.707, 4 ,276.711, 4 , 3 , 3 , 0 ,,
       7       7      14      14
     690   699.4   699.4   706.4
       7       7      14      14
     690   699.4   699.4   706.4
Pier Skew, UpSta & Num, DnSta & Num=  ,453.722, 4 ,416.725, 4 , 3 , 3 , 0 ,,
       7       7      14      14
     690   699.4   699.4   706.4
       7       7      14      14
     690   699.4   699.4   706.4
Pier Skew, UpSta & Num, DnSta & Num=  ,607.831, 4 ,570.835, 4 , 3 , 3 , 0 ,,
       7       7      14      14
     690   699.4   699.4   706.4
       7       7      14      14
     690   699.4   699.4   706.4
Pier Skew, UpSta & Num, DnSta & Num=  ,747.845, 4 ,710.849, 4 , 3 , 3 , 0 ,,
       7       7      14      14
     690   699.4   699.4   706.4
       7       7      14      14
     690   699.4   699.4   706.4
BR Coef=-1 , 1 , 1 ,0.9, 0 ,,,0.8,-1,1.33,1,
WSPro=,,,, 1 ,,,, 0 ,,,, 0 ,,,,-1 ,-1 ,-1 , 0 , 0 , 0 , 0 , 0
BR U #Sta/Elev= 488
       0  739.99   2.349     740   3.524  739.96   4.698  739.84   9.397  739.28
  10.572  739.43  11.746  739.67  14.095  739.91  16.435  740.09  23.483  740.39
  24.658  740.46  27.007  740.68  31.705  741.17   32.88  741.18  34.054  741.07
  35.229  741.01  36.404  740.99  39.928  741.08  42.267  741.06  44.617  740.94
  46.966  740.72   48.14  740.55   50.49  740.11  52.839  739.81  55.188  739.43
  57.537  739.14  59.887  738.83  62.236  738.42  64.585  738.08  66.934  737.67
  68.109  737.49  70.449  737.28  72.798  737.05  75.147  736.96  76.322  736.88
  79.846  736.69  82.195   736.5   83.37  736.36  89.243  735.95  92.766  735.65
   96.29  735.28   98.63     735 100.979  734.61 103.329  734.15 105.678  733.64
 108.027   733.2 110.376  732.83 111.551  732.56 112.726  732.25 115.075  731.74
 116.249  731.56 119.773  731.53 123.297  731.44 125.637  731.32 126.812  731.19
 129.161  731.02 130.335  731.03 133.859  731.17 135.034  731.17 138.558  731.13
 140.907   731.2 142.082  731.21 145.605  731.14 147.955  731.13 150.304   731.1
 153.818  731.12 157.342  731.05 158.517  731.11 160.866  731.39 162.041  731.46
 165.564  731.49 167.914  731.37 169.088  731.34 172.612  731.34 173.787  731.32
 176.136  731.21 178.485  731.16  179.66  731.09 180.825  730.98     182   730.9
 184.349  730.83 191.397  730.35 192.571  730.25 193.746  729.55  194.92  727.75
  195.39  727.63  195.86   727.6 198.209  727.52 201.028  727.44 202.438  727.39
 203.378  727.37 204.787  727.32 207.127  727.27 207.597  727.25 210.886  727.18
 211.356  727.16 211.826  726.79 212.295  724.69 212.765   721.6 213.705  715.85
 214.175  713.25 214.645  712.65 215.114  712.58 217.464  712.27 219.813  712.01
 222.162  711.65 226.861  710.95 234.369  709.99 235.308  709.86 240.947  709.18
 242.826  708.94 243.296  708.87 246.585  708.48 247.524  708.38 249.874   708.1
 250.813     708 252.693  707.94 256.452  707.84 256.921  707.82 258.801  707.78
 259.271  707.76  261.15  707.72  263.96  707.64 270.538  707.48 278.055  707.28
 280.404  707.23 282.754  707.17 283.223  707.15 285.103  707.11 287.452  707.05
 289.331  706.99 290.741   706.9 293.081  706.72  295.43  706.55  296.37  706.49
 297.779  706.38 298.719  706.32 301.068  706.14 302.008  706.08 306.236  705.76
 307.176   705.7 309.525  705.52 313.754  705.21 316.103     705 317.983  704.88
 318.452  704.84 322.672  704.57 323.142  704.53 325.961  704.35 330.189  704.02
 331.129  703.96 332.069  703.92 333.478  703.84 336.297  703.72 336.767  703.69
 341.466  703.49 341.935  703.46 347.104  703.24 347.574  703.21 351.802  703.03
 353.672  702.91 356.021  702.73 358.371  702.56  359.31  702.44 362.129  702.04
 362.599  701.94 368.707  700.12 369.177  699.97 377.164  697.59 377.634  697.44
 385.142   695.2 385.612  695.05   393.6  692.67 395.479   692.1 395.949 691.128
 397.358 691.108 399.238 691.098 401.117 691.098 401.587 691.088 405.816 691.078
 408.165 691.058 410.984 691.058 411.444 691.068 415.203 691.068 415.673 691.078
 419.432 691.078 419.902 691.088  423.66 691.088  424.13 691.098 427.889 691.098
 428.359 691.108 432.118 691.108 432.587 691.118 434.467 691.118 452.781 691.218
 454.661 691.218 455.131 691.228  457.01 691.228 459.359 691.248 460.769 691.248
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BR U #Mann= 6
       0     .06  195.39     .04 362.129    .032 684.331     .04 800.017     .08
 918.737     .06
BR U Banks=362.129,684.331
BR D #Sta/Elev= 495
       0     736   2.349  735.94   3.524   735.9   4.698  735.81   8.222  735.51
  11.746   735.2  12.921  735.08  14.095  734.94   15.27  734.84  16.445  734.79
  17.619  734.76  18.794  734.77  19.968  734.72  21.143  734.62  23.492  734.36
  24.667  734.22  25.842   734.1  27.016     734  28.191  733.97  29.365  733.92
  31.715  733.79  32.889  733.68  34.064  733.65  35.238  733.65  36.413   733.6
  37.588  733.38  38.753  733.05  39.928  732.77  41.102   732.6  43.451  732.39
  44.626  732.36  46.975  732.37  50.499  732.43  52.848   732.5  54.023  732.45
  55.198  732.33  56.372  732.25  57.547  732.22  61.071  732.16  62.245  732.15
  64.594  732.07  65.769  732.05  66.944  732.07  70.468   732.1  72.817   732.1
  73.991  732.11  76.341  732.17  79.864  732.24  81.039  732.27  83.388  732.26
  85.738  732.26  86.912  732.22  88.087   732.2  89.261  732.23  91.611  732.21
  92.785  732.25   93.96  732.26  96.309  732.17  98.658  732.09 101.008   732.1
 102.182  732.09 103.357  732.03 104.531     732 105.706  731.88 106.881   731.7
 108.055   731.6 110.404  731.49 111.579  731.48 112.754  731.49 113.928  731.52
 116.268   731.5 117.443  731.52 118.617  731.56 119.792  731.58 123.316  731.67
  124.49  731.72 125.665  731.73  126.84   731.7 129.189  731.62 130.364  731.59
 132.713  731.61 135.062  731.54 136.237  731.53 138.586  731.58 140.935  731.69
  142.11  731.72 144.459   731.8 145.634  731.79 146.808  731.73 150.332  731.73
 153.856  731.79  155.03  731.79 156.205  731.77 158.554   731.7 160.904  731.74
 163.253  731.72 165.602   731.8 167.951   731.8   170.3  731.87 171.475  731.48
 176.127  730.69 182.704   730.8 184.584  730.82 188.343  730.88 188.812  729.62
 189.282  726.25 190.222   718.4 190.692  714.82 191.162  713.03 191.632   712.9
 192.571  712.77  197.27  712.15 198.679  711.99 200.549  711.91 202.898  711.86
 203.368  711.84 207.127  711.76 207.597  711.74 211.356  711.66 211.826  711.64
 215.114  711.57 215.584  711.55 218.403  711.49 218.873  711.47 221.222  711.42
 224.042  711.35 226.851  711.28  229.67   711.2  232.02  711.15 232.489  711.13
 234.839  711.08 236.248  711.04 237.658  711.02 240.947  711.01 243.296  710.98
 249.874  710.86 250.344  710.86 254.093  710.79 256.912  710.78  263.02  710.74
 265.839  710.71 269.598  710.54 270.068  710.48 272.417  710.01 274.296  709.75
 278.995  709.13 280.404  708.89 281.804  708.68 283.684  708.38 285.093  708.17
 288.382  707.58 290.732  707.18 292.141  706.91 293.551  706.56  295.43  706.06
   295.9  705.95 299.659  705.21 300.598  704.97 302.948  704.54 305.767  704.01
 306.236  703.94 309.046  703.75 311.395   703.6 311.865  703.56 314.214  703.41
 317.034  703.21 319.383  703.06 320.322  702.99 325.491  702.44 325.961   702.4
  328.31  702.25  328.78  702.23 331.129  702.08 332.069  702.03 332.538  701.97
 333.008  701.81 334.408  701.24 345.215  696.87 345.685  696.67 352.263  694.01
 355.551  692.62 356.021  692.43  358.84  691.23  359.31  691.04 363.529689.8477
 363.999689.8477 364.469689.8477 367.758689.8477 371.987689.8477 375.745689.8477
 380.444689.8477 381.384689.8477 383.733689.8477 384.673689.8477 387.022689.8477
 389.831689.8477 390.771689.8477  394.06689.8477 398.759689.8477 399.228689.8477
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BR D #Mann= 8
       0     .08  229.67    .035 332.538    .032 648.162    .035 758.708    .035
 762.297     .08 891.571     .06 892.699     .05
BR D Banks=,648.162
BC Design=,, 0 ,, 0 ,,,,,,
BC Use User HTab Curves=0
BC User HTab FreeFlow(D)= 0

Type RM Length L Ch R = 1 ,251.1   ,179.49,235.17,283.09
BEGIN DESCRIPTION:
Overbank geometry from 2011 City of Columbus LiDAR data.  Channel geometry from proposed design plans.
END DESCRIPTION:
XS GIS Cut Line= 3
1827493.87156461 714879.32863611 1826405.4665892714696.734513104
1826405.45671739714696.732856979
#Sta/Elev= 30
       0     736  22.543  735.31  43.207  732.44  78.906  732.82 108.027  731.32
  196.33  732.08 199.149  720.21 200.089  719.37  231.08713.2117 275.236     712
 314.684  704.05 332.538  702.24 337.237  701.72  371.02   688.4  459.99   688.4
 493.169  692.01 619.041  693.03 651.912  701.95 760.879  704.91 762.758   707.1
  788.12  710.23 799.397  717.95 813.482  719.69  821.94  724.08 839.784  728.86
 891.571727.6287 892.699727.6191  954.85  727.591001.825  721.251037.064  720.34
#Mann= 8 ,-1 , 0
       0     .08       0  231.08    .035       0 332.538    .032       0
 651.912    .035       0 760.879    .035       0 762.758     .08       0
 891.571     .06       0 892.699     .05       0
Levee=0,,,-1,839.74,729.04,,
#XS Ineff= 2 , 0
       0  107.95  731.34  879.61       0  727.86
Permanent Ineff=
       F       F
Bank Sta=332.538,651.912
XS Rating Curve= 0 ,0
Skew Angle= 20
Exp/Cntr=0.5,0.3