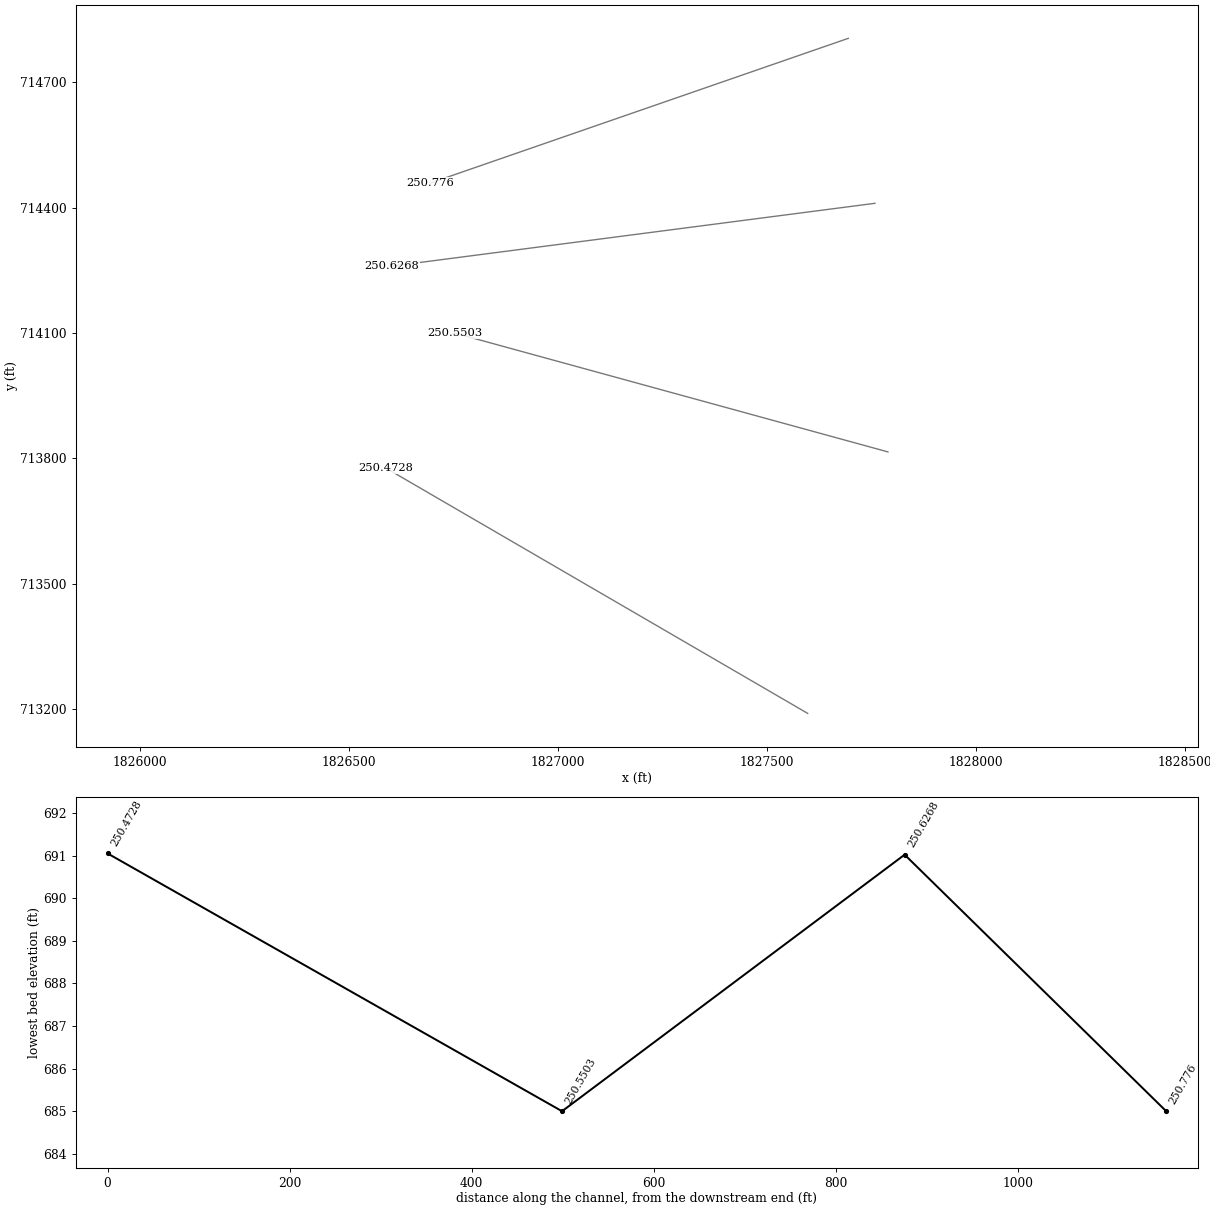
HEC-RAS study FRA-70-1321R.prj: FRA-70-1321R

--- FRA-70-1321R.g06 (geometry) --- (continued)

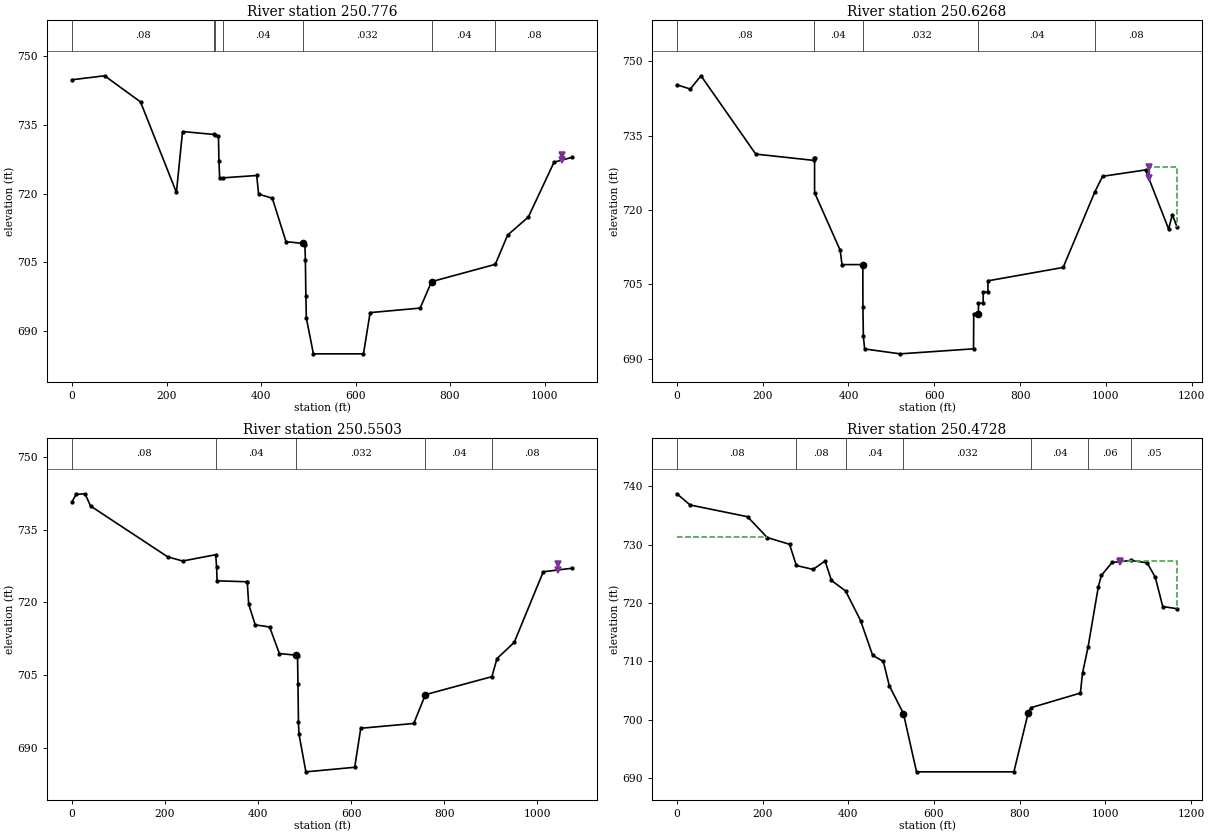
Type RM Length L Ch R = 1 ,250.776 ,322.81,287.31,216.99
BEGIN DESCRIPTION:
Overbank geometry from 2011 City of Columbus LiDAR data.  Channel geometry from proposed design plans.
END DESCRIPTION:
XS GIS Cut Line= 2
1827694.99091302714805.1440731881826694.41936781714458.718250939
#Sta/Elev= 30
       0  744.84   68.99  745.71  144.98  740.01  220.97  720.25  233.97  733.54
  300.96  732.89  302.96   732.8  309.96  732.54  310.95  727.11  312.51   723.4
  319.95  723.43  390.94  723.94  394.94  719.86  423.94  718.98  452.93  709.49
  489.43   709.1  492.93  708.72  493.93   705.5  494.93  697.73  495.93  692.83
  510.93     685  616.88     685  630.91     694  736.89  694.99  760.89  700.76
  895.86  704.54  921.86  710.92  965.85  714.88 1020.14  726.84 1058.85  727.92
#Mann= 7 ,-1 , 0
       0     .08       0  300.96    .035       0  302.96     .08       0
  319.95     .04       0  489.43    .032       0  760.89     .04       0
  895.86     .08       0
Levee=0,,,-1,1036.68,728.31,,
#XS Ineff= 2 , 0
          307.43  732.45
Permanent Ineff=
       F       F
Bank Sta=489.43,760.89
XS Rating Curve= 0 ,0
Exp/Cntr=0.3,0.1

Type RM Length L Ch R = 1 ,250.6268,445.39,376.26,241.66
BEGIN DESCRIPTION:
Overbank geometry from 2011 City of Columbus LiDAR data.  Channel geometry from proposed design plans.
END DESCRIPTION:
XS GIS Cut Line= 2
1827758.81230769 714410.312185691826602.38220586 714259.94043918
#Sta/Elev= 30
       0  745.24   31.25  744.38   56.25  747.05  183.87  731.27  318.98     730
  318.98   730.5  320.98   730.5  321.01   723.5  380.73  711.88  384.91     709
  433.43     709  433.69  700.51  434.69  694.55  437.69     692  520.63  691.02
  691.51  692.03  691.94  698.98  702.98  698.98  702.98  701.23  714.02  701.23
  714.02  703.48  725.06  703.48  725.06  705.73  900.36  708.43   974.3  723.67
  992.29  726.79 1092.42  728.08 1146.16  716.17 1154.91  719.05 1166.16  716.49
#Mann= 5 ,-1 , 0
       0     .08       0  318.98     .04       0  433.43    .032       0
  702.98     .04       0   974.3     .08       0
Levee=0,,,-1,1099.68,728.71,,
#XS Ineff= 2 , 0
       0                 1099.68       0  728.71
Permanent Ineff=
       F       F
Bank Sta=433.43,702.98
XS Rating Curve= 0 ,0
Exp/Cntr=0.3,0.1

Type RM Length L Ch R = 1 ,250.5503,536.12,499.14,418.07
BEGIN DESCRIPTION:
Overbank geometry from 2011 City of Columbus LiDAR data.  Channel geometry from proposed design plans.
END DESCRIPTION:
Node Name=AI
XS GIS Cut Line= 2
   1827789.82406   713815.278271   1826752.47114   714099.776389
#Sta/Elev= 30
       0  740.77    8.75   742.3   27.99  742.43   39.99   739.9  205.93  729.39
  237.92  728.55   308.9  729.84   310.9  727.34   311.9  724.45  375.88  724.26
  376.88  724.13  379.88  719.62  393.87  715.36  424.86  714.92  445.86  709.43
  481.34   709.1  484.85  709.01  485.85   703.2  486.84  695.37  487.84  692.87
  502.84     685   607.8  685.94   620.8     694  734.76  694.99  759.75  700.94
  902.71  704.66   913.7  708.39  950.73  711.74 1013.19  726.32 1075.66  727.06
#Mann= 5 ,-1 , 0
       0     .08       0   308.9     .04       0  481.34    .032       0
  759.75     .04       0  902.71     .08       0
Levee=0,,,-1,1045.87,728,,
Bank Sta=481.34,759.75
XS Rating Curve= 0 ,0
Exp/Cntr=0.5,0.3

Type RM Length L Ch R = 1 ,250.4728,263.74,261.23,259.9
BEGIN DESCRIPTION:
Overbank geometry from 2011 City of Columbus LiDAR data.  Channel geometry from proposed design plans.
END DESCRIPTION:
XS GIS Cut Line= 2
1827597.69976902713189.4370027631826588.06104028713776.602823183
#Sta/Elev= 30
       0   738.7      31  736.78  164.99  734.77  210.99   731.2  262.99  730.05
  278.99  726.41  317.99  725.74  345.99  727.18  360.99  723.84  393.99  722.04
  428.99  716.95  456.99  711.03  481.99  709.96  495.98  705.79  528.98  701.03
  559.49  691.05  786.74  691.05  819.98  701.11  826.99  702.05  941.97  704.55
  946.97  707.95  959.97  712.46  983.97  722.81  990.97  724.71 1015.97  726.93
 1060.97  727.28 1097.97  726.86 1116.97  724.36 1134.23  719.38 1167.96     719
#Mann= 7 ,-1 , 0
       0     .08       0  278.99     .08       0  393.99     .04       0
  528.98    .032       0  826.99     .04       0  959.97     .06       0
 1060.97     .05       0
Levee=0,,,-1,1033.78,727.2,,
#XS Ineff= 2 , 0
       0  210.89  731.25 1033.78       0   727.2
Permanent Ineff=
       F       F
Bank Sta=528.98,819.98
XS Rating Curve= 0 ,0
Exp/Cntr=0.5,0.3