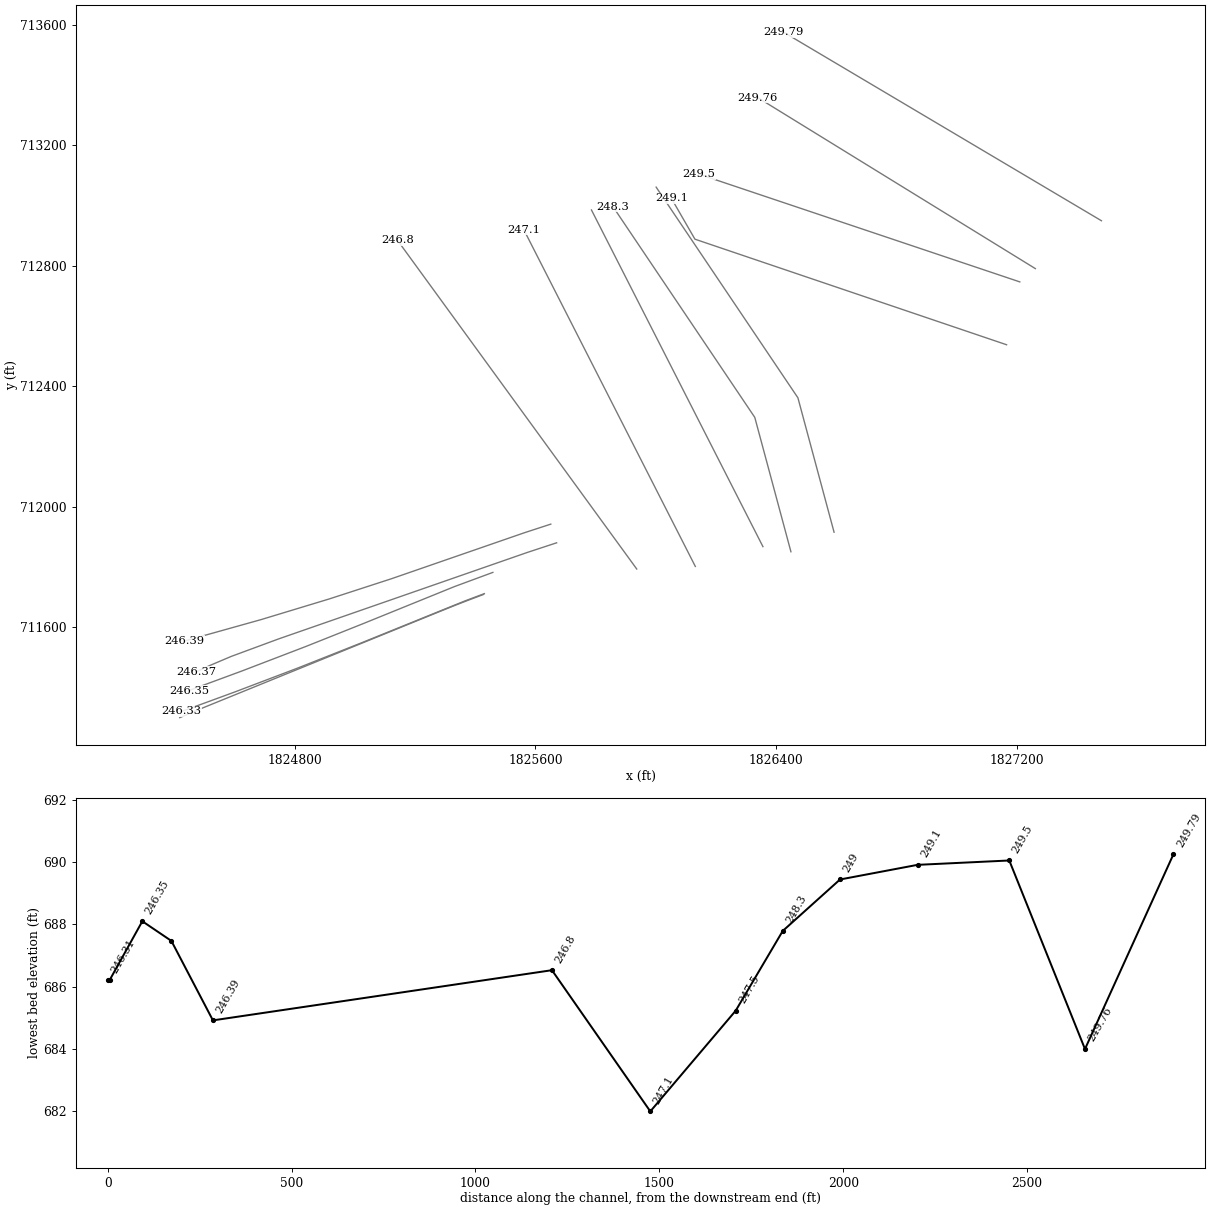
HEC-RAS study FRA-70-1321R.prj: FRA-70-1321R

--- FRA-70-1321R.g06 (geometry) --- (continued)

Type RM Length L Ch R = 3 ,250.4469,,,
BEGIN DESCRIPTION:
Rich Street Bridge
Geometry from HEC-RAS model prepared by DLZ and provided by the City of Columbus and from construction plans provided by the City of Columbus, Transportation Division.
END DESCRIPTION:
Bridge Culvert--1,0,-1,-1, 0
Deck Dist Width WeirC Skew NumUp NumDn MinLoCord MaxHiCord MaxSubmerge Is_Ogee
179,60,2.6,0, 52, 53, , , 0.98, 0, 0,0,,
     250   305.4   330.4 355.401   380.4  389.89  389.89  401.64  422.95  423.64
 443.139  462.89  481.64  500.39  501.36 516.139  530.89 543.891  557.01  557.89
  578.39 598.889  619.39  639.64 640.581  654.64  668.89  683.14   697.2 698.139
 718.391  738.89  759.39  779.89  780.77  793.89  806.89  821.64  836.42  837.39
 856.139 874.891  894.64  914.14  914.83  936.14 947.889 947.889  956.52  981.52
 1006.52 1026.52
  728.85  728.63  728.53  728.68  729.06   729.2   729.2  729.55  730.23  730.25
  730.91  731.51  732.04  732.52  732.54  732.88  733.19  733.43  733.65  733.67
  733.96   734.2  734.37  734.48  734.49  734.53  734.55  734.53  734.49  734.48
  734.37   734.2  733.96  733.67  733.65  733.43  733.19  732.88  732.54  732.52
  732.04  731.51  730.91  730.25  730.23  729.48     729     729  728.79  727.91
  726.95  726.18
                                             690  722.75  722.75  720.78  724.46
   726.1  727.09   727.2  726.82  723.12     726  726.94  726.21  723.96  727.76
  729.09  729.78  729.49  728.52  724.79  727.42   728.3  727.42  724.79  728.52
  729.49  729.78  729.09  727.76  723.96  726.21  726.94     726  723.12  726.82
   727.2  727.09   726.1  724.46  720.78  722.75  722.75     690
  275.11 330.509  355.51  380.51  405.51     415     415  426.75  448.06  448.75
  468.25     488  506.75   525.5  526.47  541.25     556     569  582.12     583
   603.5     624   644.5  664.75  665.69  679.75     694  708.25  722.31  723.25
   743.5     764 784.501     805  805.88     819     832  846.75  861.53   862.5
  881.25     900  919.75  939.25 939.939  961.25     973     973  981.63 1006.63
 1031.63 1056.63  1073.9
  728.85  728.63  728.53  728.68  729.06   729.2   729.2  729.55  730.23  730.25
  730.91  731.51  732.04  732.52  732.54  732.88  733.19  733.43  733.65  733.67
  733.96   734.2  734.37  734.48  734.49  734.53  734.55  734.53  734.49  734.48
  734.37   734.2  733.96  733.67  733.65  733.43  733.19  732.88  732.54  732.52
  732.04  731.51  730.91  730.25  730.23  729.48     729     729  728.79  727.91
  726.95  725.99  724.47
                                             690  722.75  722.75  720.78  724.46
   726.1  727.09   727.2  726.82  723.12     726  726.94  726.21  723.96  727.76
  729.09  729.78  729.49  728.52  724.79  727.42   728.3  727.42  724.79  728.52
  729.49  729.78  729.09  727.76  723.96  726.21  726.94     726  723.12  726.82
   727.2  727.09   726.1  724.46  720.78  722.75  722.75     690
Pier Skew, UpSta & Num, DnSta & Num=  ,462.89, 6 ,488, 6 , 3 , 3 , 0 ,,
     6.5     6.5       9       9      13      13
       0   700.9   700.9   705.9   705.9   729.4
     6.5     6.5       9       9      13      13
       0   700.9   700.9   705.9   705.9   729.4
Pier Skew, UpSta & Num, DnSta & Num=  ,598.889, 6 ,624, 6 , 3 , 3 , 0 ,,
     6.5     6.5       9       9      13      13
       0   700.9   700.9   705.9   705.9   729.4
     6.5     6.5       9       9      13      13
       0   700.9   700.9   705.9   705.9   729.4
Pier Skew, UpSta & Num, DnSta & Num=  ,738.89, 6 ,764, 6 , 3 , 3 , 0 ,,
     6.5     6.5       9       9      13      13
       0   700.9   700.9   705.9   705.9   729.4
     6.5     6.5       9       9      13      13
       0   700.9   700.9   705.9   705.9   729.4
Pier Skew, UpSta & Num, DnSta & Num=  ,874.891, 6 ,900, 6 , 3 , 3 , 0 ,,
     6.5     6.5       9       9      13      13
       0   700.9   700.9   705.9   705.9   729.4
     6.5     6.5       9       9      13      13
       0   700.9   700.9   705.9   705.9   729.4
BR Coef=-1 , 1 , 1 ,0.9, 0 ,,,0.8,-1,1.33,1,
WSPro=,,,, 1 ,,,, 0 ,,,, 0 ,,,,-1 ,-1 ,-1 , 0 , 0 , 0 , 0 , 0
BR U #Sta/Elev= 410
       0   738.7     2.5  738.48       5  738.24    6.25  738.17    8.74  738.16
    9.99  738.08   11.24  737.96   12.49  737.71   13.74   737.4   14.99     737
   16.24  736.65   17.49  736.56   19.99  736.57   21.24  736.52   22.48  736.42
   23.73  736.37   24.98   736.4   28.73  736.33   32.48  736.21   34.98   736.2
   37.47   736.3   39.97  736.24   43.72  736.18   47.47  736.25   49.97  736.24
   53.71  736.07   56.21  735.94   57.46   735.9   62.46  735.59   67.45   735.4
   69.95  735.28   72.45  735.12   74.95     735   79.95  734.71   83.69  734.52
   86.19  734.28   88.69  734.16   89.94  734.15   91.19   734.2   92.44   734.4
   93.69  734.68   94.94  735.01   96.19  735.39   97.43  735.68   98.68  735.78
   99.93  735.73  102.43  735.38  103.68   735.4  106.18  735.57  107.43  735.59
  117.42  735.67  124.92  735.62  127.41  735.66  131.16  735.79  133.66  735.89
  137.41  735.99   142.4  735.98   144.9  736.03   149.9  736.08   152.4  735.98
  153.65  735.85   154.9  735.59  157.39  734.96  159.89  734.07  162.39  733.11
  163.64  732.71  164.89  732.42  166.14  732.37  169.89  732.39  172.38  732.34
  174.88  732.21  178.63  732.12  179.88  732.11  182.38  732.04  183.63  732.03
  184.88  732.14  186.12  732.37  188.62   732.8  189.87  732.91  191.12  732.88
  192.37  732.79  196.12  732.59  198.62  732.43  199.87  732.28  202.36  731.84
  203.61  731.64  207.36  731.26  211.11  731.01  212.36  730.99  213.61  730.93
   216.1  730.94  219.85  730.81   221.1  730.82  224.85  730.78   226.1  730.72
  229.84  730.58  232.34  730.54  234.84  730.52  238.59  730.37  241.09  730.35
  242.34  730.42  244.83   730.6  246.08  730.65  247.33  730.63  248.58  730.51
  249.83  730.35  251.08  730.15  252.33  730.03  253.58  729.97  254.83  729.95
  256.08  729.97  259.82  729.82  261.07  729.72  262.32  729.55  264.82  728.96
  267.32   728.3  268.57  727.92  269.82  727.49  271.07  727.13  272.32  727.03
  276.06  726.82  278.56   726.6  281.06  726.34  282.31  726.29  284.81  726.28
  288.56  726.37  291.05  726.37   292.3   726.4   294.8  726.41  298.55  726.48
   302.3   726.6  304.79  726.49  306.04  726.53  307.29  726.52  309.79  726.45
  311.04  726.44  312.29  726.38  314.79  726.34  318.54  726.21  323.53  726.15
  324.78  726.16  327.28  726.24  329.78  726.27  334.77  726.26  336.02  726.28
  338.52  726.41  339.77  726.55  341.02  726.73  342.27  726.77  343.52  726.71
  344.77   726.7  347.27  726.75  349.76  726.51  352.26  726.41  354.76  726.18
  357.26  725.97  358.51   725.8  359.76  725.54  361.99  725.13  362.49  724.97
  363.99  724.58  365.99  724.02  366.49  723.98  368.49  723.94  369.49  723.88
  370.99  723.74  371.49  723.71  372.99  723.67  374.99  723.63  375.49  723.61
  377.49  723.57  377.99  723.55  379.99  723.51  382.49  723.44  385.99  723.36
  387.49  723.32  388.49  723.26  391.49  722.99  391.99  722.93  395.49  722.58
  395.99  722.54  398.99  722.24  399.49   722.2  401.49     722  403.99  721.69
  406.49  721.39  407.49  721.26  409.99  720.98  413.99  720.18  414.99  720.05
  415.99  719.88  419.49  719.18  421.49  718.86  422.99  718.57  425.99  717.97
  426.49  717.88  428.99  717.38  431.49  716.91  433.49  716.52  435.99  716.02
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BR U #Mann= 7
       0     .08  278.56     .08  385.99     .04  535.98    .032  826.98     .04
  959.35     .06 1060.53     .05
BR U Banks=,826.98
BR D #Sta/Elev= 395
       0  737.17     2.5  736.66    6.25  736.46    8.74  736.52    9.99   736.5
   12.49  736.29   14.99  736.12   21.24  736.05   22.49     736   24.99  735.83
   26.23  735.85   28.73     736   31.23  736.19   32.48  736.17   34.98  736.36
   36.23  736.53   38.73  736.94   39.98  737.09   44.97  737.26   47.47   737.3
   49.97  737.25   51.22  737.17   54.97  736.87   57.47  736.56   63.71  735.51
   66.21  734.88   68.71  734.29   71.21  733.75   72.46  733.54   73.71  733.39
   76.21  733.01    78.7   732.7    81.2   732.5    83.7  732.48    86.2  732.42
    88.7  732.43   96.19  732.29   97.44   732.1   98.69  731.85  101.19  731.56
  103.69  731.51  108.69  731.51  121.18  731.65  127.43  731.69  128.68  731.63
  131.17   731.3  134.92  730.71  136.17  730.53  137.42  730.63  139.92  731.51
  141.17  731.71  142.42  731.78  144.92  731.82  147.42  731.89  148.66  732.01
  151.16  732.43  152.41  732.58  157.41  732.66  159.91  732.62  163.66  732.43
   164.9  732.41   167.4  732.42  171.15  732.32   174.9  732.44   177.4  732.45
   179.9  732.43  182.39  732.46  184.89  732.52  189.89  732.57  193.64  732.55
  197.39  732.62  199.88  732.65  203.63  732.63  206.13   732.6  222.37  732.55
  227.37  732.65  233.62  732.61  239.86  732.48  242.36  732.37  249.86  732.48
  251.11  732.52  254.85   732.7   256.1  732.72   258.6  732.63  259.85  732.67
   263.6  732.88  264.85  732.62  271.09  730.65  272.83 730.564  273.25 730.506
  274.04 730.128  275.85 729.288  276.81 728.862  276.97 728.613  278.21   728.6
  285.45 728.499   285.8 728.549  286.61 728.488  298.23  728.76  298.53 728.775
  300.81 728.761  303.34 728.746  314.95  728.57  319.57 728.445  325.52 728.329
  326.57 728.329  330.09 728.274  336.75 728.215  338.09 728.186  338.34 728.075
  342.78 728.108  350.37  727.79  350.87  727.66  352.87  727.18  353.37  727.05
  355.37  726.57  355.87  726.44  357.87  725.96  359.87  725.46  361.37   725.1
  361.87  724.97  363.37  724.61  363.86  724.48  365.36  724.12  365.86  723.99
  367.36  723.63  367.86   723.5  369.36  723.14  369.86  723.01  371.36  722.65
  373.36  722.15  374.86  721.79  375.36  721.66  376.86   721.3  377.36  721.17
  378.86  720.81  379.36  720.68  380.86  720.32  381.36  720.19  382.86  719.83
  383.36   719.7  384.86  719.34  385.36  719.21  386.86  718.85  387.36  718.72
  390.35     718  391.35  717.83  392.35  717.71  393.85  717.51  396.35   717.2
  397.85     717  398.35  716.91  401.85  716.21  402.35  716.12  406.35  715.32
  406.85  715.23  411.35  714.33  411.85  714.24  416.35  713.34  417.34  713.15
  421.84  712.25  422.34  712.16  427.34  711.16  428.34     711  429.34  710.94
  431.34  710.85  433.84  710.72  434.84  710.68  438.34   710.5  443.84  710.24
  446.33  710.11  448.33  710.02  448.83  709.95  449.33   709.8  450.33  709.46
  451.83  708.97  455.33   707.8  456.83  707.32  457.83  707.02  459.33  706.55
  461.83  705.75  462.33   705.6  464.33  704.96  466.83  704.11  467.33  704.01
  467.83  703.98  468.83  703.96  470.33  703.91  476.32  703.75  480.32  703.65
  480.82  703.63  483.32  703.57  486.32  703.49  487.82  703.44  491.82  703.34
  495.32  703.17  498.81  703.01  500.31  702.93  502.31  702.81  502.81  702.79
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BR D #Mann= 8
       0     .06    83.7     .05   174.9     .06  193.64     .05  342.78     .04
   532.3    .032  826.19     .04  909.66     .06
BR D Banks=,826.19
BC Design=,, 0 ,, 0 ,,,,,,
BC Use User HTab Curves=0
BC User HTab FreeFlow(D)= 0

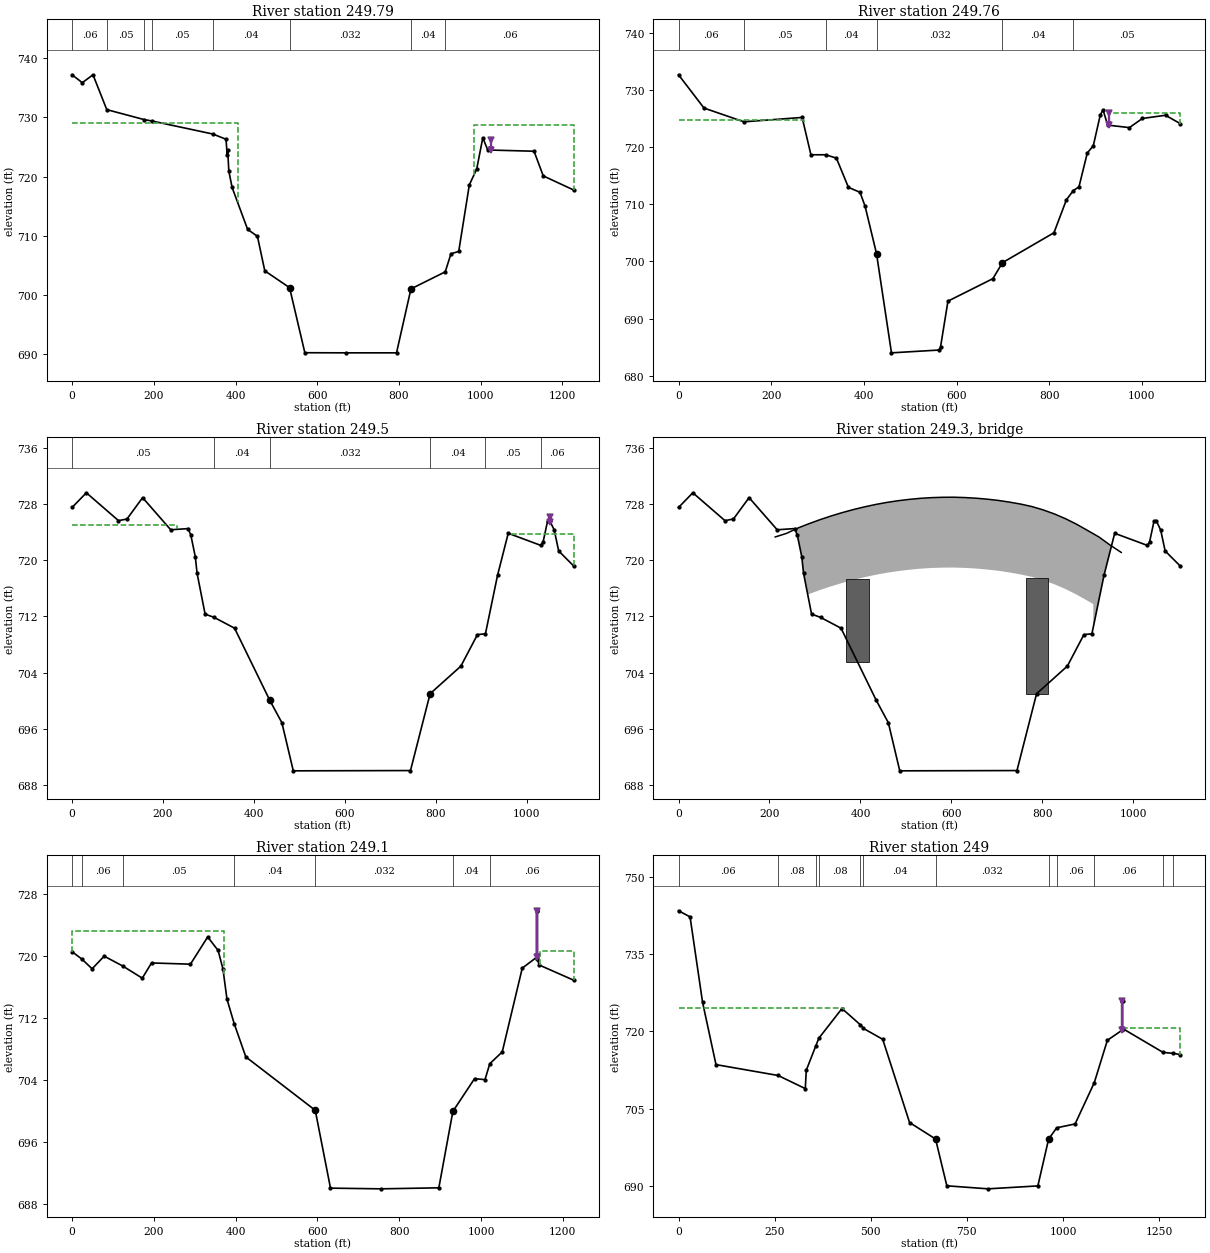
Type RM Length L Ch R = 1 ,249.79  ,243.01,240.57,234.78
BEGIN DESCRIPTION:
Overbank geometry from 2011 City of Columbus LiDAR data.  Channel geometry from proposed design plans.
END DESCRIPTION:
XS GIS Cut Line= 2
1827479.55039902712949.558217436 1826423.3681282713576.107161194
#Sta/Elev= 30
       0  737.17   24.99  735.83   51.22  737.17   84.93  731.29  176.86   729.6
  194.85  729.38  344.73  727.17  376.71  726.29   379.7  723.62   380.7  724.54
   383.7  720.89  391.69  718.15  429.66  711.08  453.65  709.91  471.63  704.09
   532.3  701.25  569.66  690.27  669.48  690.25  794.04  690.25  829.35  701.04
  913.29  703.92  927.28  706.97  946.26  707.36  972.24   718.6  990.23  721.25
 1005.22  726.55 1017.21  724.48 1130.59  724.27 1153.08  720.11 1228.04  717.71
#Mann= 8 ,-1 , 0
       0     .06       0   84.93     .05       0  176.86     .06       0
  194.85     .05       0  344.73     .04       0   532.3    .032       0
  829.35     .04       0  913.29     .06       0
Levee=0,,,-1,1024.4,726.13,,
#XS Ineff= 2 , 0
       0     405  729.05     983       0  728.74
Permanent Ineff=
       F       F
Bank Sta=532.3,829.35
XS Rating Curve= 0 ,0
Exp/Cntr=0.5,0.3

Type RM Length L Ch R = 1 ,249.76  ,150.75,205.87,256.95
BEGIN DESCRIPTION:
Overbank geometry from 2011 City of Columbus LiDAR data.  Channel geometry from proposed design plans.
END DESCRIPTION:
XS GIS Cut Line= 2
   1827260.08299   712790.621527   1826337.86075    713358.67715
#Sta/Elev= 30
       0  732.63   54.96  726.81  141.17 724.402  266.79  725.17  285.77  718.64
  317.39  718.64  340.73  718.06  366.71  712.94  391.69  712.08  402.68  709.64
  427.35  701.35  459.63     684  562.55  684.49  565.55  685.03  581.54  693.04
  678.46  696.97  699.27  699.77  810.35     705  837.33  710.78  852.32  712.39
  864.31  713.02   882.3  718.95  895.29  720.22  910.27  725.57  916.27   726.5
  926.26  723.83  973.22  723.39  1001.2  724.99 1051.16  725.55 1083.14  724.08
#Mann= 6 ,-1 , 0
       0     .06       0  141.17     .05       0  317.39     .04       0
  427.35    .032       0  699.27     .04       0  852.32     .05       0
Levee=0,,,-1,929.12,726,,
#XS Ineff= 2 , 0
       0  269.97  724.73  929.12       0     726
Permanent Ineff=
       F       F
Bank Sta=427.35,699.27
XS Rating Curve= 0 ,0
Exp/Cntr=0.5,0.3

Type RM Length L Ch R = 1 ,249.5   ,235.08,249.49,252.77
BEGIN DESCRIPTION:
Overbank geometry from 2011 City of Columbus LiDAR data.   Channel geometry from proposed design plans..
END DESCRIPTION:
Node Name=AH
XS GIS Cut Line= 3
1827208.42298852712746.5258150991826142.91453844713104.247001041
1826142.90609069 713104.24983719
#Sta/Elev= 30
       0  727.49  31.412  729.58 102.089  725.62  120.73  725.85 155.087  728.89
  216.93  724.32 255.213  724.49 261.103  723.57 270.919   720.5 274.846  718.15
 292.515  712.33 312.148  711.87 357.293  710.33 434.841  700.06 461.345  696.89
  486.42  690.05   744.1  690.09 787.226  701.01 854.958  704.94 891.268  709.41
 908.938  709.54 935.442  717.83 959.001  723.821030.659   722.11035.568  722.55
1045.384  725.521050.292  725.611060.108  724.291069.924  721.311103.318  719.15
#Mann= 6 ,-1 , 0
       0     .05       0 312.148     .04       0 434.841    .032       0
 787.226     .04       0 908.938     .05       01030.659     .06       0
Levee=0,,,-1,1051.32,726.08,,
#XS Ineff= 2 , 0
       0 229.639  725.01 966.929       0  723.66
Permanent Ineff=
       F       F
Bank Sta=434.841,787.226
XS Rating Curve= 0 ,0
Skew Angle= 11
Exp/Cntr=0.5,0.3

Type RM Length L Ch R = 3 ,249.3   ,,,
BEGIN DESCRIPTION:
Main Street Bridge.
Geometry from construction plans provided by the City of Columbus, Transportation Division.
END DESCRIPTION:
Bridge Culvert--1,0,-1,-1, 0
Deck Dist Width WeirC Skew NumUp NumDn MinLoCord MaxHiCord MaxSubmerge Is_Ogee
55,105,2.6,11, 36, 39, , , 0.98, 0, 0,0,,
 212.618 237.159   261.7 284.639 284.639 286.239  310.78 335.321 359.862 384.207
 408.943 433.484 458.025 482.565 507.106 531.647 556.188 580.727 605.268 629.809
  654.35  678.89 703.431 727.972 752.513 777.054 801.594 826.135 850.675 875.216
 899.756 911.929 911.929 924.297 948.838 973.379
   723.3   723.8  724.55  725.13  725.13  725.17  725.75  726.28  726.76  727.19
  727.58  727.92  728.21  728.45  728.64  728.79  728.89  728.94  728.95   728.9
  728.81  728.67  728.49  728.25  727.97  727.62  727.15  726.58   725.9  725.11
  724.21  723.76  723.76   723.3  722.15   721.1
                             680  715.13  715.17  715.75  716.28  716.76  717.19
  717.58  717.92  718.21  718.45  718.64  718.79  718.89  718.94  718.95   718.9
  718.81  718.67  718.49  718.25  717.97  717.62  717.15  716.58   715.9  715.11
  714.21  713.76     680
 332.762 371.918 396.459     421 443.941 443.941 445.541 470.082 494.622 519.163
 543.507 568.245 592.785 617.326 641.866 666.407 690.947 715.488 740.029  764.57
  789.11 813.651 838.192 862.732 887.274 911.813 936.354 960.895 985.4361009.976
1034.5171059.058 1071.23 1071.231083.5991108.139 1132.681181.7621224.178
   722.5   723.3   723.8  724.55  725.13  725.13  725.17  725.75  726.28  726.76
  727.19  727.58  727.92  728.21  728.45  728.64  728.79  728.89  728.94  728.95
   728.9  728.81  728.67  728.49  728.25  727.97  727.62  727.15  726.58   725.9
  725.11  724.21  723.76  723.76   723.3  722.15   721.1     719  717.19
                                     680  715.13  715.17  715.75  716.28  716.76
  717.19  717.58  717.92  718.21  718.45  718.64  718.79  718.89  718.94  718.95
   718.9  718.81  718.67  718.49  718.25  717.97  717.62  717.15  716.58   715.9
  715.11  714.21  713.76     680
Pier Skew, UpSta & Num, DnSta & Num=  ,393.574, 2 ,562.875, 2 , 0 , 0 , 0 ,,
   48.74   28.24
     680     718
   48.74   28.24
     680     718
Pier Skew, UpSta & Num, DnSta & Num=  ,787.324, 2 ,956.626, 2 , 0 , 0 , 0 ,,
   48.74   28.24
     680     718
   48.74   28.24
     680     718
BR Coef=-1 , 0 , 0 ,1.25, 0 ,,,0.8,-1,2,1,
WSPro=,,,, 1 ,,,, 0 ,,,, 0 ,,,,-1 ,-1 ,-1 , 0 , 0 , 0 , 0 , 0
BC Design=,, 0 ,, 0 ,,,,,,
BC Use User HTab Curves=0
BC User HTab FreeFlow(D)= 0

Type RM Length L Ch R = 1 ,249.1   ,377.23,210.84,63.5
BEGIN DESCRIPTION:
Overbank geometry from 2011 City of Columbus LiDAR data.  Channel geometry from proposed design plans.
END DESCRIPTION:
XS GIS Cut Line= 3
1827164.48606853712537.8261012731826129.67448986712888.366082609
1826051.02407532713024.735525452
#Sta/Elev= 30
       0  720.56  24.531  719.57  49.062  718.34  78.501  719.98 124.618  718.68
 171.716  717.13 194.284   719.1 289.462  718.94 331.662  722.46 357.175  720.71
 368.945  718.32 378.761  714.43  396.42  711.26 424.878  706.96  594.64  700.06
 631.922     690 755.558  689.91 896.864  690.04   931.2  699.92 984.189  704.15
1009.702  704.021021.481  706.081051.892   707.61100.864  718.431135.743  719.82
1135.743  725.841137.706  725.841137.706  719.561142.408  718.831227.034  716.86
#Mann= 7 ,-1 , 0
       0     .08       0  24.531     .06       0 124.618     .05       0
  396.42     .04       0  594.64    .032       0   931.2     .04       0
1021.481     .06       0
Levee=0,,,-1,1135.74,725.84,,
#XS Ineff= 2 , 0
       0 371.174  723.281143.997       0  720.62
Permanent Ineff=
       F       F
Bank Sta=594.64,931.2
XS Rating Curve= 0 ,0
Skew Angle= 11
Exp/Cntr=0.5,0.3

Type RM Length L Ch R = 1 ,249     ,156.71,155.69,155.43
BEGIN DESCRIPTION:
Overbank geometry from 2011 City of Columbus LiDAR data.  Channel geometry from proposed design plans.
END DESCRIPTION:
XS GIS Cut Line= 4
1826591.64108561 711915.406414361826471.59965903712361.660115018
1826000.89521986713061.0957240161826000.89521986713061.095724017
#Sta/Elev= 30
       0  743.43   29.98  742.25   62.45  725.68   97.42  713.56  258.88711.4537
  329.73   708.9  332.22  712.46  356.89717.1614  364.93718.6832  425.19  724.45
   473.1  721.28   481.1  720.58  531.04  718.48  600.97  702.31  668.51  699.12
  697.86  690.03  804.75  689.44  934.61  690.01  962.57  699.09  983.55  701.29
  1031.5  702.04 1081.44 710.065 1115.41  718.28    1153  720.21    1153  725.82
    1155  725.82    1155  720.57 1260.24715.9334 1286.31715.7479 1305.19  715.51
#Mann= 12 ,-1 , 0
       0     .06       0  258.88     .08       0  356.89     .06       0
  364.93     .08       0   473.1     .05       0   481.1     .04       0
  668.51    .032       0  962.57     .04       0  983.55     .06       0
 1081.44     .06       0 1260.24     .08       0 1286.31     .06       0
Levee=0,,,-1,1153,725.82,,
#XS Ineff= 2 , 0
       0   430.3  724.51 1156.65       0  720.58
Permanent Ineff=
       F       F
Bank Sta=668.51,962.57
XS Rating Curve= 0 ,0
Exp/Cntr=0.3,0.1

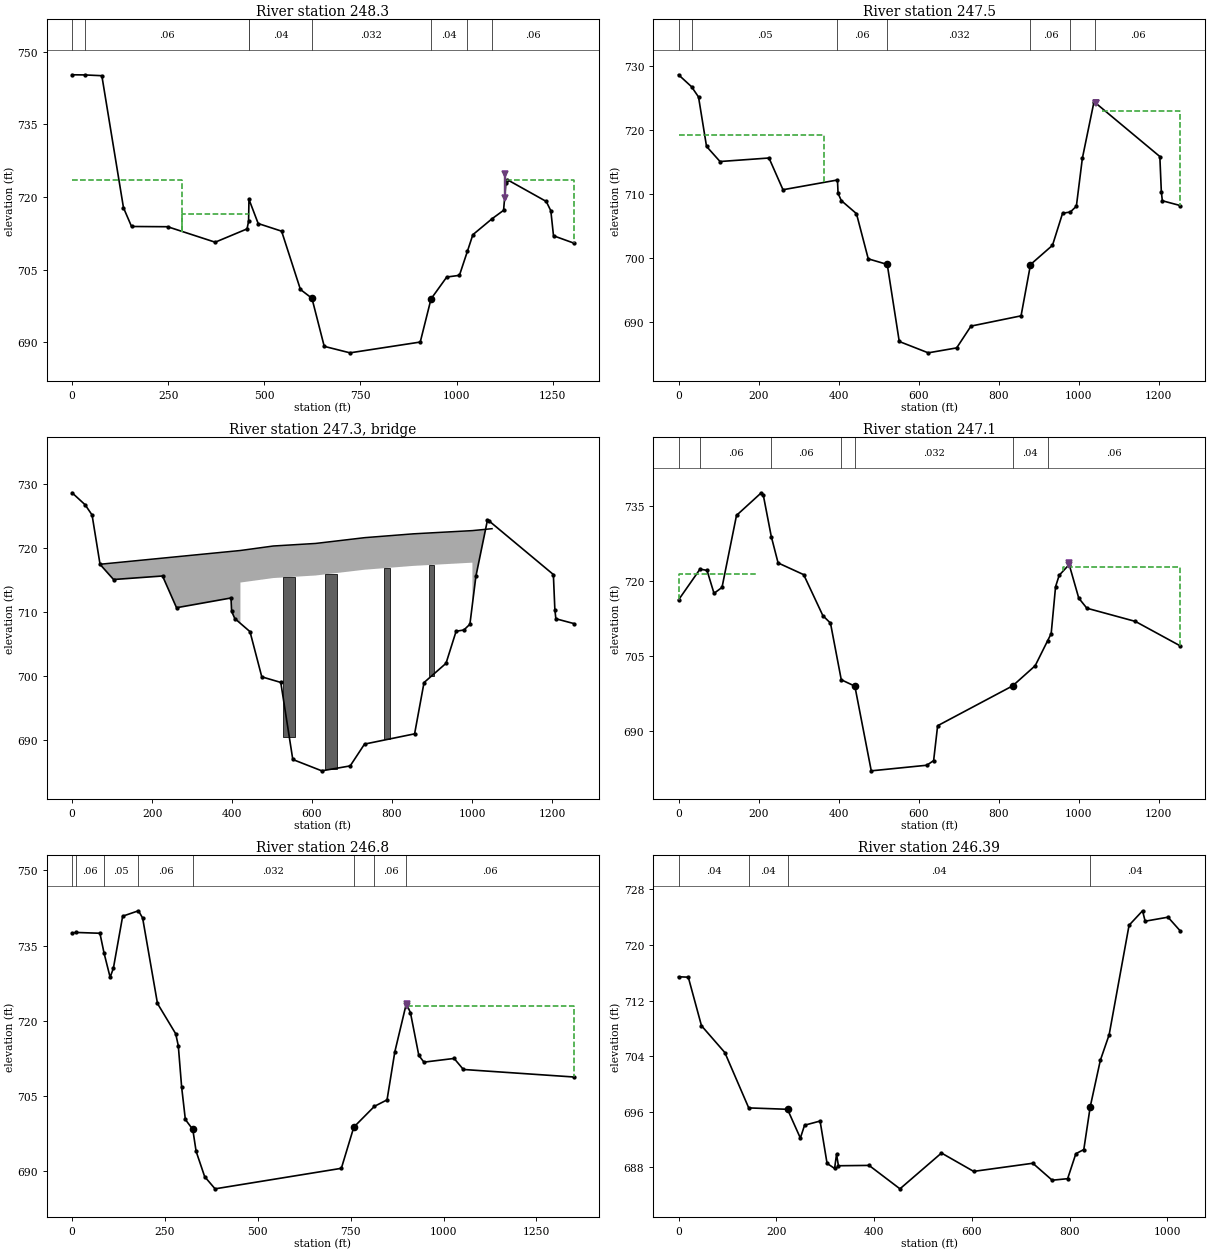
Type RM Length L Ch R = 1 ,248.3   ,156.94,128.05,104.7
BEGIN DESCRIPTION:
Overbank geometry from 2011 City of Columbus LiDAR data.  Channel geometry from proposed design plans.
END DESCRIPTION:
XS GIS Cut Line= 4
1826448.43008594711850.4124498521826328.38865936712296.666150525
1825857.68389212712996.1017595231825857.67830347712996.110063883
#Sta/Elev= 30
       0  745.27   32.47  745.24   77.44  745.08  133.74  717.78   154.7  713.91
  248.53  713.86  372.29  710.66  455.13  713.41  459.12  714.99  460.12  719.53
  484.09  714.52  545.03  712.94  593.97  700.89  623.91  699.07  655.91  689.13
  722.83  687.79  905.64  690.02  933.71  698.94  974.56  703.46 1007.53  703.81
  1028.5  708.83 1042.49  712.21 1092.43  715.51  1122.4  717.25 1128.39  722.92
 1132.39  723.57 1233.27  719.09 1245.26  717.17 1252.25  711.99  1305.2  710.47
#Mann= 8 ,-1 , 0
       0     .08       0   32.47     .06       0  459.12     .05       0
  460.12     .04       0  623.91    .032       0  933.71     .04       0
  1028.5     .04       0 1092.43     .06       0
Levee=0,,,-1,1125,724.68,,
#XS Ineff= 3 ,-1
       0  286.74   723.6  286.74  463.47  716.52 1131.04    1400   723.6
Permanent Ineff=
       F       F       F
Bank Sta=623.91,933.71
XS Rating Curve= 0 ,0
Exp/Cntr=0.5,0.3

Type RM Length L Ch R = 1 ,247.5   ,235.21,232.14,230.24
BEGIN DESCRIPTION:
Overbank geometry from 2011 City of Columbus LiDAR data.   Channel geometry from proposed design plans.
END DESCRIPTION:
Node Name=AG
XS GIS Cut Line= 2
1826355.46078369711867.4403029381825786.08287978 712985.35215663
#Sta/Elev= 30
       0   728.6   32.49  726.74   49.98  725.14   69.98  717.43  103.71  715.07
  226.17  715.62  261.16  710.67  397.36  712.19  398.86  710.11  406.86  708.98
  444.84  706.94  474.33  699.89  521.82  699.02  551.85     687  624.29  685.23
  695.35     686  731.14   689.4  856.38     691  879.96     699  934.93     702
  960.17     707  979.66   707.2  994.66   708.1 1009.65  715.58 1038.39  724.29
 1042.14  724.23 1203.33  715.85 1207.08  710.37 1209.58  708.95 1254.56   708.2
#Mann= 7 ,-1 , 0
       0     .08       0   32.49     .05       0  397.36     .06       0
  521.82    .032       0  879.96     .06       0  979.66     .05       0
 1042.14     .06       0
Levee=0,,,-1,1042.49,724.2,,
#XS Ineff= 2 , 0
       0  362.95  719.22 1058.93       0  722.94
Permanent Ineff=
       F       F
Bank Sta=521.82,879.96
XS Rating Curve= 0 ,0
Exp/Cntr=0.5,0.3

Type RM Length L Ch R = 3 ,247.3   ,,,
BEGIN DESCRIPTION:
Norfolk Southern / CSX Shared Railroad Bridge
Geometry from plans provided by Norfolk Southern.  Top chord elevations adjusted using 2009 City of Columbus LiDAR data.
END DESCRIPTION:
Bridge Culvert--1,0,-1,-1, 0
Deck Dist Width WeirC Skew NumUp NumDn MinLoCord MaxHiCord MaxSubmerge Is_Ogee
58,70,2.6,0, 10, 10, , , 0.98, 0, 0,0,,
   74.32  420.95  420.95  503.09  609.09  731.42  853.75 1000.93 1000.93    1050
  717.48   719.6   719.6   720.3   720.7   721.6   722.2   722.7   722.7     723
             680   714.6   715.3   715.7   716.6   717.2   717.7     680
     300  377.68  377.68   457.3   563.3  685.63  807.96  959.11  959.11  976.83
   718.9   719.6   719.6   720.3   720.7   721.6   722.2   722.7   722.7  722.89
             680   714.6   715.3   715.7   716.6   717.2   717.7     680
Pier Skew, UpSta & Num, DnSta & Num=  ,543, 4 ,499.73, 4 , 0 , 0 , 0 ,,
   29.16   13.16    9.16    8.17
     683     687     687   715.5
   29.16   13.16    9.16    8.17
     683     687     687   715.5
Pier Skew, UpSta & Num, DnSta & Num=  ,647.12, 4 ,603.85, 4 , 0 , 0 , 0 ,,
   29.16   13.16    9.16    8.17
     683     687     687   715.9
   29.16   13.16    9.16    8.17
     683     687     687   715.9
Pier Skew, UpSta & Num, DnSta & Num=  ,787.58, 6 ,744.31, 6 , 0 , 0 , 0 ,,
   12.92   12.92   10.92   10.92    8.92    8.17
     683     688     688     694     694   716.9
   12.92   12.92   10.92   10.92    8.92    8.17
     683     688     688     694     694   716.9
Pier Skew, UpSta & Num, DnSta & Num=  ,899.28, 6 ,856.01, 6 , 0 , 0 , 0 ,,
   12.92   12.92   10.92   10.92    8.92    8.17
     683     688     688     694     694   717.4
   12.92   12.92   10.92   10.92    8.92    8.17
     683     688     688     694     694   717.4
BR Coef=-1 , 1 , 1 ,1.25, 0 ,,,0.8,-1,2,1,
WSPro=,,,, 1 ,,,, 0 ,,,, 0 ,,,,-1 ,-1 ,-1 , 0 , 0 , 0 , 0 , 0
BR U #Sta/Elev= 432
       0   728.6       5  728.32    6.25  728.24   11.25  727.96    12.5  727.88
   18.74  727.53   19.99  727.45   26.24  727.09   32.49  726.74   33.74  726.66
   43.74   726.1   46.23  725.91   47.48  725.74   49.98  725.14   51.23   724.8
   52.48  724.22   53.73  723.43   54.98  722.79   57.48  722.48   58.73  722.02
   61.23  720.93   63.73  719.56   64.98  718.82   66.23  718.22   68.73  717.64
   69.98  717.43   72.48  717.15   76.22  716.94   79.97  716.76   83.72  716.37
   86.22  716.19   89.97  716.06   91.22  715.98   93.72  715.74   96.22   715.6
  102.46  715.18  103.71  715.07  106.21  715.05  108.71  714.97  109.96  714.96
  112.46  714.88  113.71  714.81  116.21  714.82  117.46  714.86  121.21  714.87
  123.71  714.83  124.96  714.85  126.21   714.8  129.96  714.83  132.45  714.82
  134.95  714.84  137.45  714.79  139.95  714.85   143.7  714.69   146.2  714.71
   148.7  714.62  149.95  714.61   153.7  714.63  154.95   714.6   158.7  714.46
  163.69  714.42  164.94  714.45  167.44  714.64  171.19  714.79  172.44  714.79
  174.94  714.84  177.44  714.85  182.44  714.81  184.94  714.83  187.44  714.81
  189.93  714.82  192.43  714.78  193.68  714.81  196.18  714.92  198.68  715.09
  202.43  715.27  207.43  715.42  209.93  715.34  211.18  715.36  213.68  715.31
  216.18  715.52  218.67  715.58  221.17  715.52  222.42  715.52  226.17  715.62
  227.42  715.57  228.67   715.4  234.92  714.06  236.17  713.74  237.42  713.53
  238.67  713.38  239.92   713.1  241.17  712.74  242.42  712.47  244.92  712.02
  249.91  711.25  251.16  711.13  254.91  710.97  258.66  710.71  261.16  710.67
  266.16  710.71  269.91  710.66  272.41  710.67  273.66  710.72  274.91  710.63
  278.65   710.7  281.15  710.88  283.65  711.23   284.9  711.26   289.9   711.8
   292.4  711.94  293.65  711.92  296.15  711.81   297.4  711.67  298.65   711.6
   302.4  711.54  303.65  711.57  306.14  711.72  308.64  711.69  311.14  711.58
  312.39   711.6  316.14  711.77  317.39  711.85  322.39  711.95  329.89  711.94
  334.89  711.99  337.38  712.11  338.63  712.13  342.38  712.13  344.88  712.16
  347.38  712.24  348.63  712.31  352.38  712.43  356.13  712.33  358.63  712.32
  359.88  712.35  362.38   712.5  363.62  712.52  364.87  712.49  366.12  712.35
  367.37  712.33  371.12  712.38  372.37  712.38  376.12  712.33  381.12  712.13
  383.62  712.07  384.87  712.08  387.37  712.19  392.37  712.09  394.86  712.02
  396.11  712.07  397.36  712.19  398.86  710.11  403.36  709.48  403.86   709.4
  406.86  708.98  410.86  708.55  411.36  708.51  416.35  708.01  419.85  707.59
  422.35  707.28  422.85  707.25  426.85  707.18  427.35  707.18  430.35  707.13
  435.35  707.13  437.85  707.14  443.35  707.03  444.34     707  444.84  706.94
  447.34  706.39  449.34  705.96  450.84   705.6  452.84  705.01  453.34  704.88
  456.84  704.04  457.34  703.91  461.34  702.95  464.84  702.29  466.34  699.89
  468.84  699.86  473.34  699.83  473.83   699.7  476.33  699.73  480.83  699.73
  481.33  699.73  484.33  699.78  484.83  699.78  490.83  699.78  491.33  699.78
  497.33  699.78  499.33  699.78  502.33  699.86  502.83  699.83  505.82  699.71
  506.32  699.68  509.82  699.54  510.32  699.51  513.32  699.39  513.82  699.36
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BR U #Mann= 7
       0     .08   32.49     .05  397.36     .06  521.82    .032  879.96     .06
  979.66     .05 1042.14     .06
BR U Banks=,879.96
BR D #Sta/Elev= 413
       0  716.18       5  716.24     7.5  716.33   13.75  717.14   14.99  717.31
   19.99  717.95   24.99   718.6   29.99  719.26   33.74  719.74   38.74   720.4
   43.74  721.04   44.98  721.21   53.73  722.34   59.98  723.15   61.23  723.17
   62.48  722.97   66.23  722.15   67.48  721.93   68.73  721.93   71.23  722.08
   72.48   721.9   74.97  720.89   76.22   720.4   77.47  720.01   81.22  718.92
   82.47   718.6   83.72  718.36   84.97  717.95   86.22  717.74   88.72  717.49
   89.97  717.45   91.22  717.52   92.47  717.65   97.47  718.25   98.72  718.42
   99.97  718.69  101.22  718.92  102.46  719.05  103.71  719.05  104.96   718.9
  107.46  718.64  108.71  718.68  109.96  718.85  111.21  719.16  112.46  719.54
  113.71  720.01  114.96  720.58  117.46  721.59  121.21  723.19  123.71  724.21
  124.96  724.65  126.21  725.04  127.46  725.34  128.71  725.72  129.96  726.27
  131.21  726.76   136.2  728.59  137.45  729.13   138.7  729.79  139.95  730.31
  142.45  731.23   143.7  731.63  147.45  732.63  149.95  733.31   151.2  733.57
   153.7  733.93   156.2  734.23   158.7  734.51  163.69  735.09  164.94  735.37
  166.19  735.56  167.44  735.66  171.19  735.87  173.69  735.92  174.94  735.88
  176.19  735.74  177.44  735.79  179.94  735.99  183.69  736.09  191.18  736.24
  193.68   736.3  194.93  736.27  197.43   736.1  198.68  736.07  201.18  736.21
  202.43  736.35  204.93  736.93  206.18  737.01  209.93  736.87  211.18  736.78
  212.43  736.63  213.68   736.3  217.43  734.89  222.42  732.93  224.92  731.88
  226.17  731.41  229.92  730.06  231.17  729.56  232.42  728.99  234.92  727.79
  238.67  726.01  239.92  725.49  241.17  725.05  242.42  724.73  244.92  724.23
  246.17  724.01  247.41  723.76  248.66  723.58  249.91  723.48  251.16  723.42
  254.91  723.08  256.16     723  258.66  722.91  261.16  722.68  264.91  722.55
  271.16  722.05  273.66   721.9  274.91   721.8  278.65  721.39  281.15  721.18
   282.4   721.1   287.4  721.15  293.65  721.09   297.4  721.07   299.9  721.16
  301.15  721.18  306.14  721.04  308.64  720.83  313.64  720.78  317.39  720.56
  318.64  720.41  321.14  719.99  323.64  719.66  326.14  719.27  327.39  719.13
  328.64  718.95  333.64  718.11  334.89  717.91  336.13  717.81  337.38  717.61
  341.13  716.71  342.38  716.43  346.13  715.75  348.63  715.34  351.13  714.86
  353.63  714.28  356.13  713.58  357.38  713.26  359.88  712.71  362.38  712.22
  363.62  712.15  366.12  712.14  369.87     712  372.37  711.85  376.12  711.72
  378.62  711.54  379.87   711.4  381.12  711.07  382.37  710.57  386.12   708.6
  387.37  708.05  389.87  707.17  391.12  706.76  392.37   706.3  396.11  705.03
  398.61   704.1  399.86  703.46  402.36  702.04  403.61  701.41  404.86  700.72
  406.11  699.98  424.85  699.64  425.85  699.59  427.85  699.51  428.35  699.48
  430.35   699.4  430.85  699.37  432.85  699.29  433.35  699.26  435.85  699.16
  436.35  699.13  438.35  699.05  439.35  698.98  439.85  698.77  441.85  697.78
  443.35  697.05  444.35  696.55  445.85  695.82  446.85  695.32  449.35   694.1
  449.85  693.91  454.85  692.39  455.34  692.23  458.84  691.18  459.34  691.04
  460.84  690.51  461.84  690.14  462.84  689.73  464.84  688.98  465.84  688.62
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BR D #Mann= 7
       0     .08   53.73     .06  231.17     .06  406.11     .04  435.85    .032
  815.25     .04  922.68     .06
BR D Banks=435.85,815.25
BC Design=,, 0 ,, 0 ,,,,,,
BC Use User HTab Curves=0
BC User HTab FreeFlow(D)= 0

Type RM Length L Ch R = 1 ,247.1   ,230.39,267.48,301.97
BEGIN DESCRIPTION:
Overbank geometry from 2011 City of Columbus LiDAR data.  Channel geometry from proposed design plans.
END DESCRIPTION:
XS GIS Cut Line= 2
   1826130.98354   711801.668453   1825561.60115   712919.589117
#Sta/Elev= 30
       0  716.18   53.73  722.34   71.23  722.08   88.72  717.49  108.71  718.68
  144.95  733.08  206.93   737.6  211.93  737.13  231.92  728.84  248.91  723.57
  312.89  721.23  360.88  713.03  379.87  711.54  406.86  700.21  440.85  698.93
  481.84     682  620.79  683.12  637.78  684.05  647.78  691.02  835.49     699
  891.69  703.02  922.68     708  931.68  709.44  942.67  718.83  951.67   721.1
  976.66  723.25 1000.65  716.53  1020.9  714.52  1142.1  711.88 1254.56  706.98
#Mann= 7 ,-1 , 0
       0     .08       0   53.73     .06       0  231.92     .06       0
  406.86     .04       0  440.85    .032       0  835.49     .04       0
  922.68     .06       0
Levee=0,,,-1,976.83,723.55,,
#XS Ineff= 3 ,-1
       0  196.12  721.42  196.12  320.32  719.21  961.02    1253  722.83
Permanent Ineff=
       F       F       F
Bank Sta=440.85,835.49
XS Rating Curve= 0 ,0
Exp/Cntr=0.5,0.3

Type RM Length L Ch R = 1 ,246.8   ,390.62,921.98,1377.54
BEGIN DESCRIPTION:
Overbank geometry from 2011 City of Columbus LiDAR data.  Channel geometry from proposed design plans.
END DESCRIPTION:
XS GIS Cut Line= 2
1825936.45013878711793.1277875161825141.63412822712885.105043387
#Sta/Elev= 30
       0  737.51   11.24  737.63   74.97  737.47   86.21  733.48  102.45  728.69
   111.2   730.5  136.19  740.87  178.67  741.95  189.91  740.51  229.89  723.47
  278.92  717.44  285.92  715.06  294.91  706.82  304.91  700.35  324.91  698.37
   333.9     694   356.9  688.96  384.89  686.53  724.79  690.62  758.34  698.83
  813.76  702.97  847.75  704.26  868.75  713.85  899.74  723.46  910.82  721.62
  933.31  713.12  947.05  711.78 1028.26  712.52 1053.25  710.32 1350.61  708.82
#Mann= 8 ,-1 , 0
       0     .08       0   11.24     .06       0   86.21     .05       0
  178.67     .06       0  324.91    .032       0  758.34     .04       0
  813.76     .06       0  899.74     .06       0
Levee=0,,,-1,900.46,723.02,,
#XS Ineff= 2 , 0
       0                  900.46       0  723.04
Permanent Ineff=
       F       F
Bank Sta=324.91,758.34
XS Rating Curve= 0 ,0
Exp/Cntr=0.5,0.3

Type RM Length L Ch R = 1 ,246.39  ,65,113,110
XS GIS Cut Line= 6
      1825651.07       711942.18      1825563.07       711913.46
      1825121.78       711760.79      1824915.38       711693.74
       1824688.8       711625.07      1824434.68       711553.99
#Sta/Elev= 30
       0  715.42   19.96  715.36  46.921  708.38  94.743  704.52 143.617  696.56
  222.95  696.36 249.252  692.22 257.877  694.07  289.63  694.67 303.898  688.58
   319.3  687.85 323.279   689.9 327.138  688.24 389.854  688.29 453.046  684.92
 537.965  690.07 603.801  687.43 724.854   688.6 764.524  686.16   796.1  686.38
 812.908  689.97 829.194  690.57 842.289  696.71 862.964  703.39 881.027  707.08
 921.815  722.83 949.411  724.91 954.668  723.411001.477  723.991026.678     722
#Mann= 4 ,-1 , 0
       0     .04       0 143.617     .04       0  222.95     .04       0
 842.289     .04       0
#XS Ineff= 2 , 0
       0     7.5                       0
Permanent Ineff=
       T       F
Bank Sta=222.95,842.289
XS Rating Curve= 0 ,0
Skew Angle= 36.5
Exp/Cntr=0.3,0.1

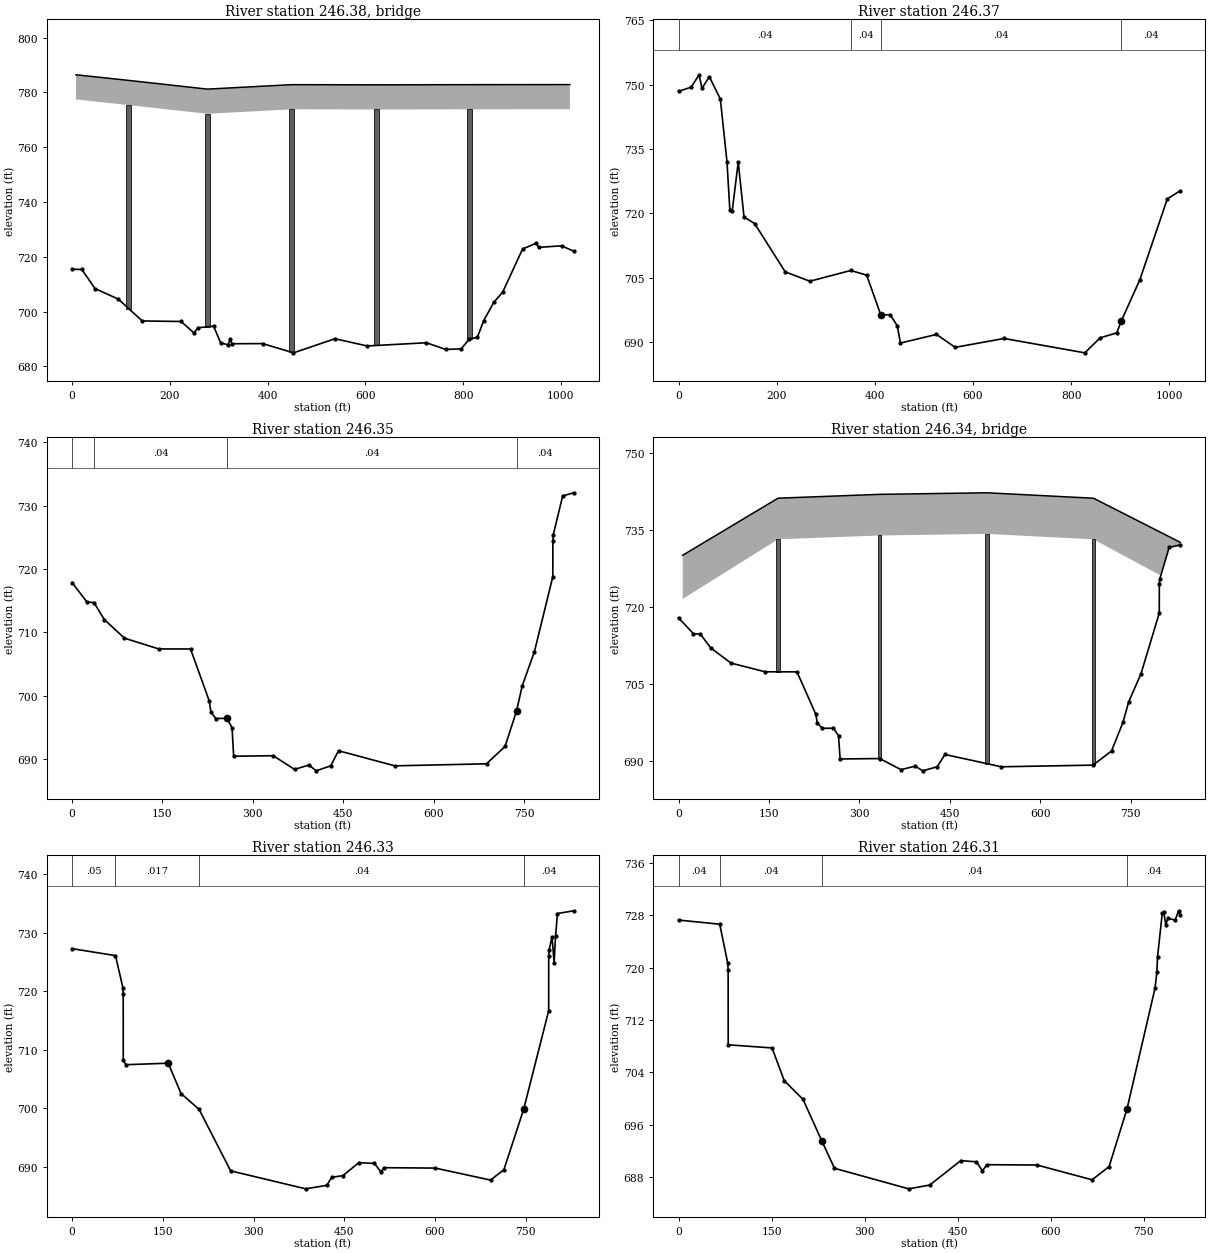
Type RM Length L Ch R = 3 ,246.38  ,,,
BEGIN DESCRIPTION:
FRA-71-1503L I-71-SB
END DESCRIPTION:
Bridge Culvert--1,0,-1,-1, 0
Deck Dist Width WeirC Skew NumUp NumDn MinLoCord MaxHiCord MaxSubmerge Is_Ogee
1,109.5,2.6,36.5, 7, 7, , , 0.98, 0, 0,0,,
   8.033 116.043 276.814 448.985 623.473  813.821018.628
  786.41 784.353781.1778 782.801 782.738 782.801 782.829
  777.41 775.353772.1778 773.801 773.738 773.801 773.829
   8.045   166.6 327.372 500.092 678.103 877.1071014.403
  783.71 782.498 780.225 777.985 777.566779.2638781.5989
  774.71 773.498 771.225 768.985 768.566770.2639772.5989
Pier Skew, UpSta & Num, DnSta & Num=  ,116.043, 6 ,166.6, 6 , 0 , 0 , 0 ,,
      10      10      10      10       8       8
     650     693   695.2   700.2   700.2 775.353
      10      10      10      10       8       8
     680     693   695.2   700.2   700.2 773.498
Pier Skew, UpSta & Num, DnSta & Num=  ,276.814, 6 ,327.372, 6 , 0 , 0 , 0 ,,
      10      10      10      10       8       8
     650     693   695.2   700.2   700.2 772.178
      10      10      10      10       8       8
     650     693   695.2   700.2   700.2 771.225
Pier Skew, UpSta & Num, DnSta & Num=  ,448.985, 6 ,500.092, 6 , 0 , 0 , 0 ,,
      10      10      10      10       8       8
     650     693   695.2   700.2   700.2 773.801
      10      10      10      10       8       8
     650     693   695.2   700.2   700.2 768.985
Pier Skew, UpSta & Num, DnSta & Num=  ,623.473, 6 ,678.103, 6 , 0 , 0 , 0 ,,
      10      10      10      10       8       8
     650     693   695.2   700.2   700.2 773.738
      10      10      10      10       8       8
     650     693   695.2   700.2   700.2 768.566
Pier Skew, UpSta & Num, DnSta & Num=  ,813.82, 6 ,877.107, 6 , 0 , 0 , 0 ,,
      10      10      10      10       8       8
     680     693     693     698     698 773.801
      10      10      10      10       8       8
     680     693     693     698     698 770.264
BR Coef=-1 , 0 , 0 ,, 0 ,,,0.8,-1,,0,
WSPro=,,,, 1 ,,,, 0 ,,,, 0 ,,,,-1 ,-1 ,-1 , 0 , 0 , 0 , 0 , 0
BC Design=,, 0 ,, 0 ,,,,,,
BC Use User HTab Curves=0
BC User HTab FreeFlow(D)= 0

Type RM Length L Ch R = 1 ,246.37  ,25,79,66
XS GIS Cut Line= 6
      1825670.41       711880.14       1825573.3       711848.23
       1824747.1       711560.98      1824589.71       711502.83
       1824517.5       711472.18      1824473.41       711451.37
#Sta/Elev= 30
       0  748.46  25.699  749.43  41.961  752.32  47.717  749.15  62.741  751.88
  85.185  746.65  98.681  732.08 104.542  720.79 109.389  720.57  121.64  731.96
   133.4  719.15 155.152  717.61 217.339  706.36 267.564  704.17  351.02  706.68
 383.391  705.58 412.186  696.29 431.277  696.37 445.634  693.79 452.202  689.75
 525.626  691.77 563.648  688.75 663.286  690.82 827.948  687.47 858.977  690.96
 892.924  692.13 902.249  694.92 940.038  704.53 995.898  723.371022.458  725.29
#Mann= 4 ,-1 , 0
       0     .04       0  351.02     .04       0 412.186     .04       0
 902.249     .04       0
Bank Sta=412.186,902.249
XS Rating Curve= 0 ,0
Skew Angle= 36.5
Exp/Cntr=0.3,0.1

Type RM Length L Ch R = 1 ,246.35  ,76,89,68
XS GIS Cut Line= 6
      1825458.76       711781.91      1825331.26        711734.8
      1825027.19       711611.44      1824839.22       711536.51
      1824624.49       711454.18      1824449.47       711389.63
#Sta/Elev= 30
       0  717.86  24.534   714.8   36.42  714.68  53.519  712.01  86.895  709.07
 143.781  707.37 196.562  707.36 227.816   699.1 230.337  697.38 238.495  696.37
 256.947   696.4  265.45  694.93 268.126  690.41 333.808  690.49 369.106  688.33
 393.001  689.02 404.995   688.1 429.183  688.89 442.092  691.28 535.521  688.89
 687.698  689.21 718.498  691.97 737.465  697.54 746.891  701.51  767.22  706.95
 797.689  718.79 797.789  724.38 798.458  725.42 814.065  731.56 832.617  732.05
#Mann= 4 ,-1 , 0
       0     .04       0   36.42     .04       0 256.947     .04       0
 737.465     .04       0
#XS Ineff= 2 , 0
       0       0                       0
Permanent Ineff=
       T       F
Bank Sta=256.947,737.465
XS Rating Curve= 0 ,0
Skew Angle= 39.75
Exp/Cntr=0.3,0.1

Type RM Length L Ch R = 3 ,246.34  ,,,
BEGIN DESCRIPTION:
FRA-70-1323C Ramp D3
END DESCRIPTION:
Bridge Culvert--1,0,-1,-1, 0
Deck Dist Width WeirC Skew NumUp NumDn MinLoCord MaxHiCord MaxSubmerge Is_Ogee
1,86,2.6,39.75, 6, 6, , , 0.98, 0, 0,0,,
   6.995 165.108 333.036 511.631 688.573 832.614
  730.05  741.15  741.89   742.2  741.14 732.552
  721.55  733.15  733.89   734.2  733.14 724.052
   8.417 168.227 336.115 514.121 684.263  822.43
  729.98  741.15  741.89   742.2  741.14 734.306
  721.48  733.15  733.89   734.2  733.14 725.806
Pier Skew, UpSta & Num, DnSta & Num=  ,165.108, 4 ,168.227, 4 , 0 , 0 , 0 ,,
     5.5     5.5       5       5
     648   697.2   697.2  733.15
     5.5     5.5       5       5
     648   697.2   697.2  733.15
Pier Skew, UpSta & Num, DnSta & Num=  ,333.036, 4 ,336.115, 4 , 0 , 0 , 0 ,,
     5.5     5.5       5       5
   648.5   697.2   697.2  733.89
     5.5     5.5       5       5
   648.5   697.2   697.2  733.89
Pier Skew, UpSta & Num, DnSta & Num=  ,511.631, 4 ,514.121, 4 , 0 , 0 , 0 ,,
     5.5     5.5       5       5
     645   697.2   697.2   734.2
     5.5     5.5       5       5
     645   697.2   697.2   734.2
Pier Skew, UpSta & Num, DnSta & Num=  ,688.573, 4 ,684.263, 4 , 0 , 0 , 0 ,,
     5.5     5.5       5       5
   645.5   697.2   697.2  733.14
     5.5     5.5       5       5
   645.5   697.2   697.2  733.14
BR Coef=-1 , 0 , 0 ,, 0 ,,,0.8,-1,,0,
WSPro=,,,, 1 ,,,, 0 ,,,, 0 ,,,,-1 ,-1 ,-1 , 0 , 0 , 0 , 0 , 0
BC Design=,, 0 ,, 0 ,,,,,,
BC Use User HTab Curves=0
BC User HTab FreeFlow(D)= 0

Type RM Length L Ch R = 1 ,246.33  ,1.5,5,21.5
XS GIS Cut Line= 6
      1825430.43       711711.43      1825366.18       711687.23
      1825025.53       711549.27      1824810.24       711464.05
      1824603.22       711385.38        1824425.       711320.09
#Sta/Elev= 30
       0  727.31  71.764  726.12  83.958  720.65  84.542  719.57  84.642   708.2
   89.04  707.45 158.981  707.71 180.117  702.52 210.071   699.8 262.106  689.29
 386.243  686.21 421.302  686.82 429.229  688.19 447.581  688.46 474.145  690.69
 499.924  690.56 510.511   689.1 516.123  689.83 600.542  689.76 691.819  687.71
 713.946  689.49 746.715  699.87 787.948  716.68 788.009  726.03 788.593  727.02
 793.506  729.35 796.935  724.92 799.311  729.45 802.471  733.32  829.58  733.79
#Mann= 4 ,-1 , 0
       0     .05       0  71.764    .017       0 210.071     .04       0
 746.715     .04       0
Bank Sta=158.981,746.715
XS Rating Curve= 0 ,0
Skew Angle= 39.75
Exp/Cntr=0.3,0.1

Type RM Length L Ch R = 1 ,246.31  ,53,79.5,66
XS GIS Cut Line= 6
      1825427.66       711708.66      1825378.97       711690.29
      1825334.47       711673.05      1825289.29       711654.89
      1824490.33       711329.84      1824418.97       711299.53
#Sta/Elev= 30
       0  727.27  66.385  726.64  79.427  720.64  79.962  719.57  80.081  708.21
 150.762  707.73 170.448  702.72 200.575  699.89  230.91  693.53 251.428  689.34
 371.008   686.2  404.94  686.78 454.998  690.51  480.28  690.33 489.933  688.94
 496.986  689.89 577.996  689.84 666.705  687.58  694.12   689.6 723.058  698.44
 768.181  716.87 771.042  719.27 772.254   721.7 779.901  728.37 782.271  728.49
 785.534  726.55 789.004  727.56 800.538  727.25 806.223  728.69 808.943  727.99
#Mann= 4 ,-1 , 0
       0     .04       0  66.385     .04       0  230.91     .04       0
 723.058     .04       0
Bank Sta=230.91,723.058
XS Rating Curve= 0 ,0
Skew Angle= 42
Exp/Cntr=0.3,0.1