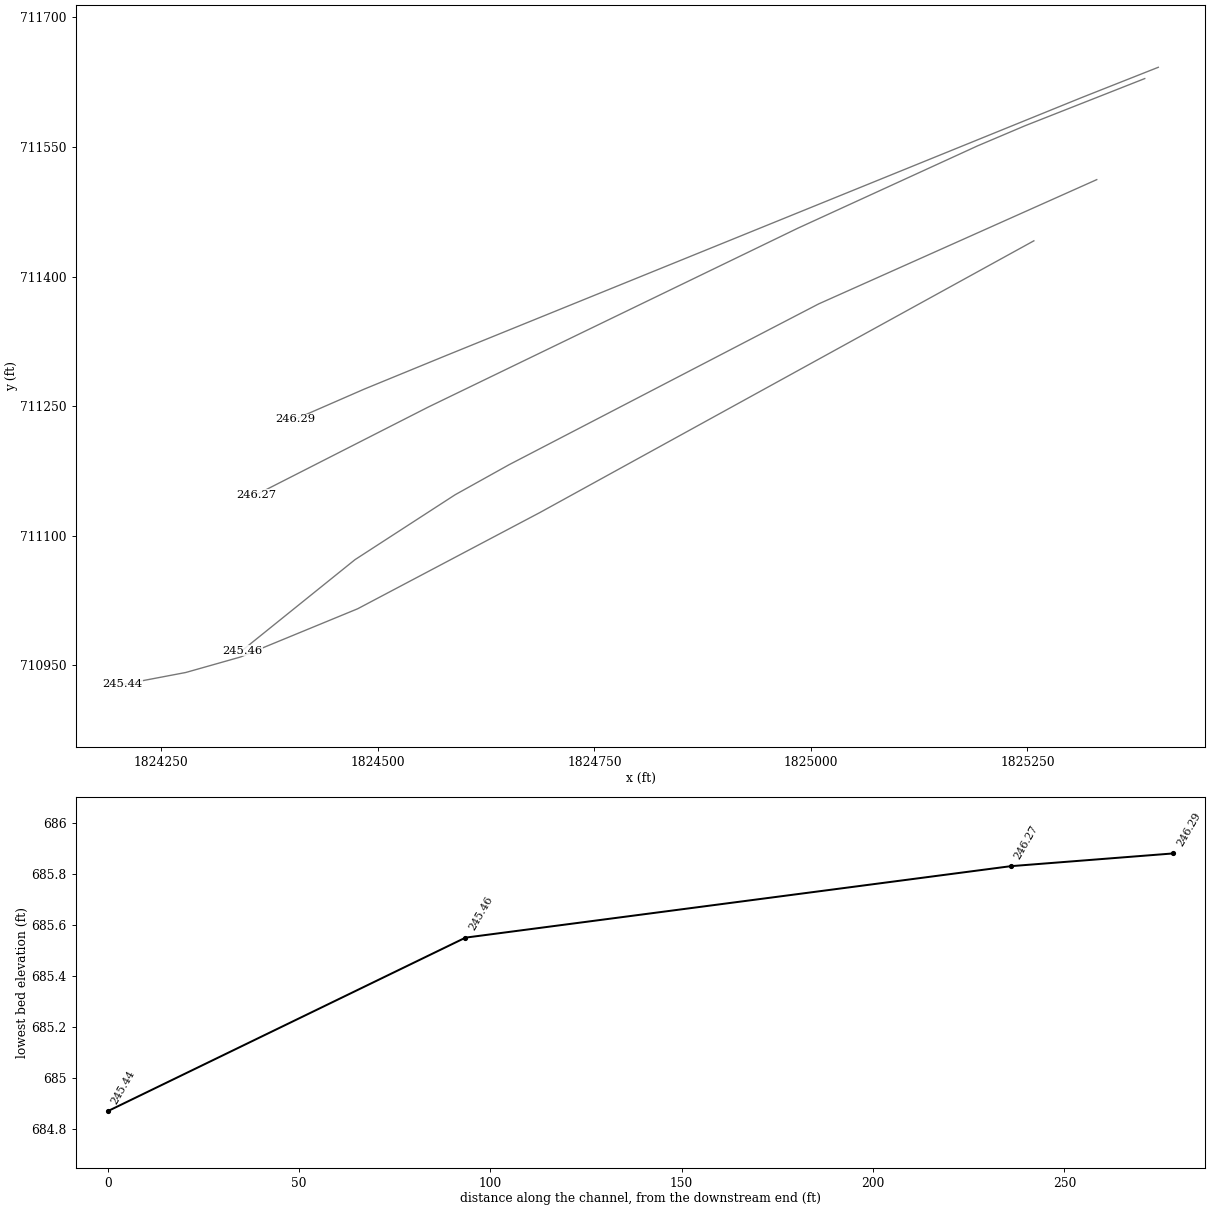
HEC-RAS study FRA-70-1321R.prj: FRA-70-1321R

--- FRA-70-1321R.g06 (geometry) --- (continued)

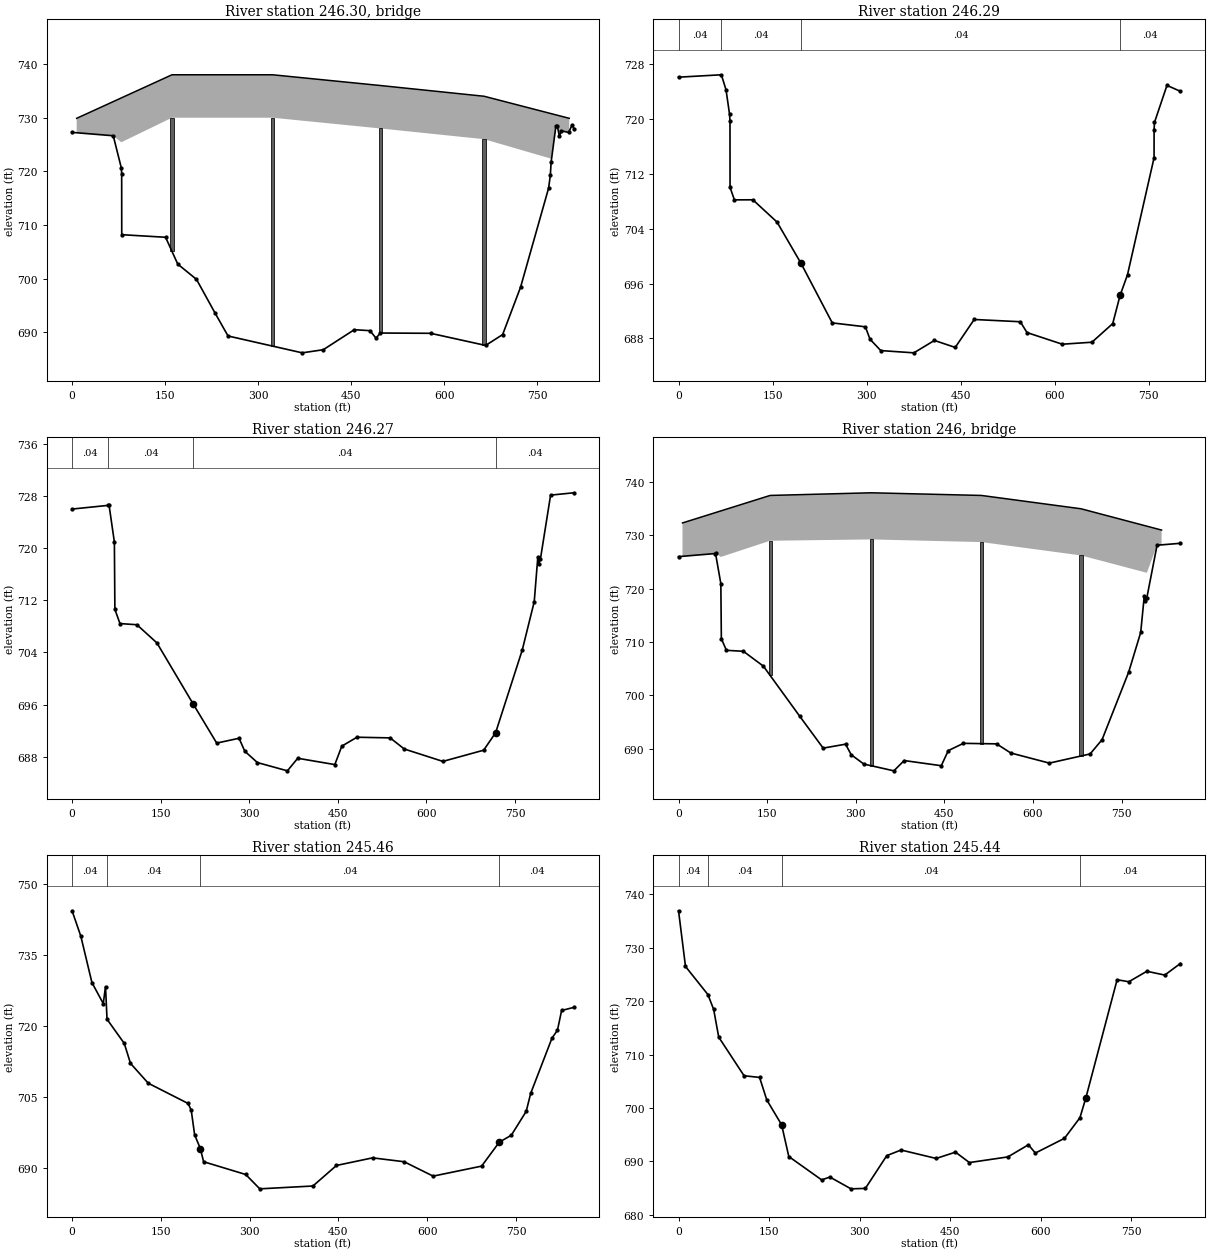
Type RM Length L Ch R = 3 ,246.30  ,,,
BEGIN DESCRIPTION:
FRA-70-1322L I-70-WB
END DESCRIPTION:
Bridge Culvert--1,0,-1,-1, 0
Deck Dist Width WeirC Skew NumUp NumDn MinLoCord MaxHiCord MaxSubmerge Is_Ogee
1,76.5,2.6,42, 6, 6, , , 0.98, 0, 0,0,,
   7.423 161.032 323.348 497.012 664.248 801.518
  729.89     738     738     736     734  729.89
  721.39     730     730     728     726  721.39
    7.44 163.496 325.811 499.475 660.804 792.804
  729.82     738     738     736     734  729.82
  721.32     730     730     728     726  721.32
Pier Skew, UpSta & Num, DnSta & Num=  ,161.032, 4 ,163.496, 4 , 0 , 0 , 0 ,,
     5.5     5.5       5       5
   649.5   697.2   697.2     730
     5.5     5.5       5       5
   649.5   697.2   697.2     730
Pier Skew, UpSta & Num, DnSta & Num=  ,323.348, 4 ,325.811, 4 , 0 , 0 , 0 ,,
     5.5     5.5       5       5
   648.5   697.2   697.2     730
     5.5     5.5       5       5
   648.5   697.2   697.2     730
Pier Skew, UpSta & Num, DnSta & Num=  ,497.012, 4 ,499.475, 4 , 0 , 0 , 0 ,,
     5.5     5.5       5       5
   645.5   697.2   697.2     728
     5.5     5.5       5       5
   645.5   697.2   697.2     728
Pier Skew, UpSta & Num, DnSta & Num=  ,664.248, 4 ,660.804, 4 , 0 , 0 , 0 ,,
     5.5     5.5       5       5
     645   697.2   697.2     726
     5.5     5.5       5       5
     645   697.2   697.2     726
BR Coef=-1 , 0 , 0 ,, 0 ,,,0.8,-1,,0,
WSPro=,,,, 1 ,,,, 0 ,,,, 0 ,,,,-1 ,-1 ,-1 , 0 , 0 , 0 , 0 , 0
BC Design=,, 0 ,, 0 ,,,,,,
BC Use User HTab Curves=0
BC User HTab FreeFlow(D)= 0

Type RM Length L Ch R = 1 ,246.29  ,6.5,42.5,56.5
XS GIS Cut Line= 6
      1825401.16       711642.22      1825312.85       711607.25
      1825197.97       711560.53      1824577.95       711308.34
      1824484.59       711269.97      1824404.37       711234.92
#Sta/Elev= 30
       0  726.12  68.288  726.47  75.726  724.28    81.3  720.75  82.043  719.78
  82.155  710.03  89.096  708.21 118.539  708.22 157.086  704.97 195.365  698.94
 245.163  690.25 297.964  689.68 305.351  687.87 322.495  686.21  375.31  685.88
 408.053  687.69  441.25  686.67 471.488  690.75 545.045  690.42 555.716  688.84
 611.957  687.14 659.273  687.43 692.455  690.15 704.145  694.26 716.013  697.29
 758.379  714.37 758.394  718.43 759.004  719.51 778.935  724.92 800.241  724.06
#Mann= 4 ,-1 , 0
       0     .04       0  68.288     .04       0 195.365     .04       0
 704.145     .04       0
Bank Sta=195.365,704.145
XS Rating Curve= 0 ,0
Skew Angle= 42
Exp/Cntr=0.3,0.1

Type RM Length L Ch R = 1 ,246.27  ,88.5,142.5,181
XS GIS Cut Line= 6
       1825385.5       711629.15      1825247.29       711574.58
      1825192.54       711551.32      1824984.67        711455.9
      1824558.31       711249.13      1824359.14       711147.47
#Sta/Elev= 30
       0  726.02  61.377  726.59  62.613  726.63  71.638  720.95  72.491  710.62
  81.067  708.44 109.789  708.26  143.68  705.47 204.997   696.1 244.856  690.09
 282.731  690.83 292.422  688.84  313.76   687.1 364.569  685.83  382.02  687.76
 444.842  686.79 456.668  689.62 482.268  690.99 538.507  690.89 562.466  689.18
 627.775  687.28 696.813     689 717.065  691.68 762.152  704.37 782.456   711.8
 788.538  718.66 790.096  717.65 792.927  718.34 810.145  728.16 849.541  728.52
#Mann= 4 ,-1 , 0
       0     .04       0  61.377     .04       0 204.997     .04       0
 717.065     .04       0
Bank Sta=204.997,717.065
XS Rating Curve= 0 ,0
Skew Angle= 41.5
Exp/Cntr=0.3,0.1

Type RM Length L Ch R = 3 ,246     ,,,
BEGIN DESCRIPTION:
FRA-70-1321R RC4
END DESCRIPTION:
Bridge Culvert--1,0,-1,-1, 0
Deck Dist Width WeirC Skew NumUp NumDn MinLoCord MaxHiCord MaxSubmerge Is_Ogee
1,139.5,2.6,41.5, 6, 6, , , 0.98, 0, 0,0,,
   6.704 155.066 326.324 512.877 681.391 817.808
 732.342   737.5     738   737.5     735 731.005
 723.592     729  729.25  728.75  726.25 722.255
    .757  152.64  327.74 508.595 680.981 836.084
 728.656   738.5  737.75   737.5   731.5 728.259
 719.906  727.75     729  727.75  723.25 719.509
Pier Skew, UpSta & Num, DnSta & Num=  ,155.066, 4 ,152.64, 4 , 0 , 0 , 0 ,,
     5.5     5.5       5       5
   652.5   697.2   697.2     729
     5.5     5.5       5       5
   652.5   697.2   697.2  727.75
Pier Skew, UpSta & Num, DnSta & Num=  ,326.324, 4 ,327.74, 4 , 0 , 0 , 0 ,,
     5.5     5.5       5       5
     649   697.2   697.2  729.25
     5.5     5.5       5       5
     649   697.2   697.2     729
Pier Skew, UpSta & Num, DnSta & Num=  ,512.877, 4 ,508.596, 4 , 0 , 0 , 0 ,,
     5.5     5.5       5       5
   647.5   697.2   697.2  728.75
     5.5     5.5       5       5
   647.5   697.2   697.2  727.75
Pier Skew, UpSta & Num, DnSta & Num=  ,681.39, 4 ,680.981, 4 , 0 , 0 , 0 ,,
     5.5     5.5       5       5
     644   697.2   697.2  726.25
     5.5     5.5       5       5
     644   697.2   697.2  723.25
BR Coef=-1 , 0 , 0 ,, 0 ,,,0.8,-1,,0,
WSPro=,,,, 1 ,,,, 0 ,,,, 0 ,,,,-1 ,-1 ,-1 , 0 , 0 , 0 , 0 , 0
BC Design=,, 0 ,, 0 ,,,,,,
BC Use User HTab Curves=0
BC User HTab FreeFlow(D)= 0

Type RM Length L Ch R = 1 ,245.46  ,37.5,93.5,6.5
XS GIS Cut Line= 6
      1825330.07       711512.21      1825008.91       711368.39
      1824651.57        711182.4      1824589.22       711147.61
      1824473.59       711072.51      1824342.96       710967.15
#Sta/Elev= 30
       0  744.42  14.777  739.05  33.546  729.22  52.719  724.77  56.509  728.37
  59.078  721.45  88.212  716.34   98.72  712.11  128.76  707.91 196.122  703.62
 201.334   702.2 207.109  696.98 216.755  694.07 222.245  691.29 293.366  688.59
 317.175  685.55 406.983  686.15 446.767   690.5 507.807  692.11  560.96  691.29
 610.092  688.24 691.983  690.36 721.881  695.43 742.118  696.89 767.328  701.95
 774.915  705.76 810.894  717.46 820.151  719.13 827.162  723.31 847.855  723.97
#Mann= 4 ,-1 , 0
       0     .04       0  59.078     .04       0 216.755     .04       0
 721.881     .04       0
Bank Sta=216.755,721.881
XS Rating Curve= 0 ,0
Skew Angle= 41.5
Exp/Cntr=0.3,0.1

Type RM Length L Ch R = 1 ,245.44  ,92.7,87.5,178.2
XS GIS Cut Line= 6
      1825257.45       711441.41       1824686.9       711126.91
      1824476.62       711015.64      1824341.26        710959.8
      1824278.08        710941.9      1824205.35       710928.08
#Sta/Elev= 30
       0  736.94  11.533  726.51  48.642  721.25  58.195  718.47  66.574  713.28
 108.541  706.05 134.273  705.73 146.187  701.52 170.759  696.87 182.667  690.92
 237.157  686.54 250.676  687.08 285.706  684.87 309.536  684.95 345.012  691.09
 368.636  692.14 426.852  690.56 458.799  691.74 481.893  689.79 545.632  690.85
 579.637  693.12 591.155  691.57 639.387  694.33 664.999  698.19 674.891  701.94
 726.588  724.03 745.962  723.65 775.845  725.61 805.515   724.9  831.31  727.06
#Mann= 4 ,-1 , 0
       0     .04       0  48.642     .04       0 170.759     .04       0
 664.999     .04       0
Bank Sta=170.759,674.891
XS Rating Curve= 0 ,0
Skew Angle= 45
Exp/Cntr=0.3,0.1