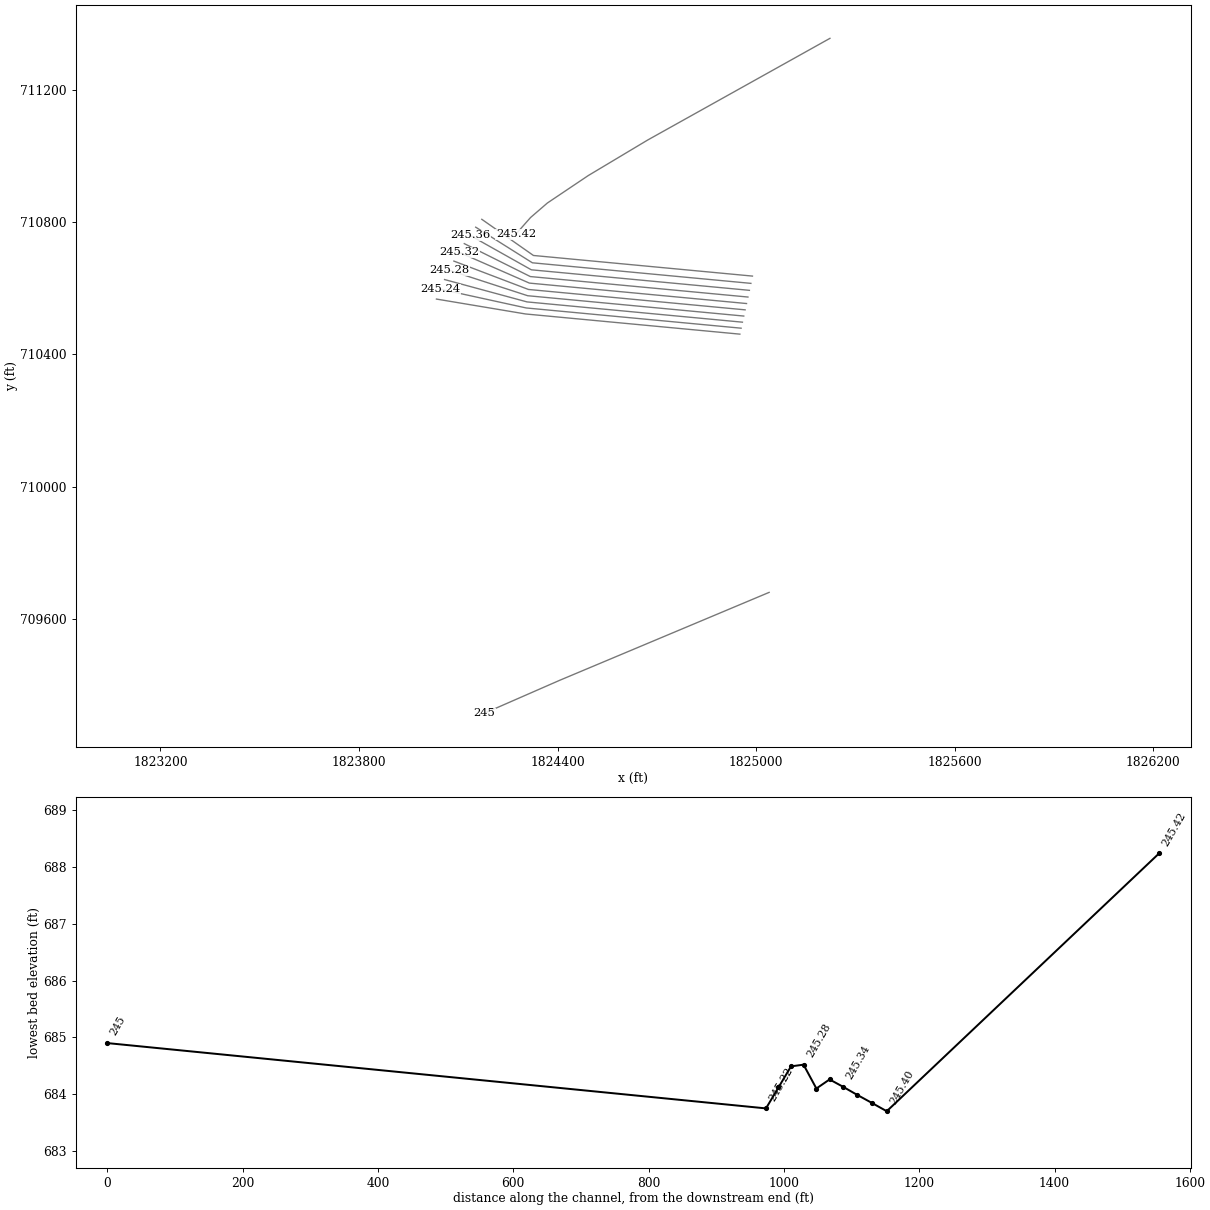
HEC-RAS study FRA-70-1321R.prj: FRA-70-1321R

--- FRA-70-1321R.g06 (geometry) --- (continued)

Type RM Length L Ch R = 3 ,245.43  ,,,
BEGIN DESCRIPTION:
FRA-70-1321A (RC5)
Assumed high water from record plans: 695.9
END DESCRIPTION:
Bridge Culvert--1,0,-1,-1, 0
Deck Dist Width WeirC Skew NumUp NumDn MinLoCord MaxHiCord MaxSubmerge Is_Ogee
1,84,2.6,45, 7, 7, , , 0.98, 0, 0,0,,
       0 126.865 291.613 460.107 612.254   732.3 831.314
 733.902   731.5  732.25  737.25     746   748.5     752
 725.402  722.75   723.5   728.5   737.5  739.75  743.25
       0 131.106 285.748 446.454 597.346 724.847 794.059
 731.593   731.5  733.25  739.25   748.5 753.137     755
 723.093  722.75   724.5   730.5  739.75 744.637  746.25
Pier Skew, UpSta & Num, DnSta & Num=  ,126.865, 4 ,131.106, 4 , 0 , 0 , 0 ,,
     5.5     5.5       5       5
   645.3   697.2   697.2     723
     5.5     5.5       5       5
   645.3   697.2   697.2  722.75
Pier Skew, UpSta & Num, DnSta & Num=  ,291.613, 4 ,285.748, 4 , 0 , 0 , 0 ,,
     5.5     5.5       5       5
   643.8   697.2   697.2   723.5
     5.5     5.5       5       5
   643.8   697.2   697.2   724.5
Pier Skew, UpSta & Num, DnSta & Num=  ,460.107, 4 ,446.454, 4 , 0 , 0 , 0 ,,
     5.5     5.5       5       5
   647.4   697.2   697.2   728.5
     5.5     5.5       5       5
   647.4   697.2   697.2   730.5
Pier Skew, UpSta & Num, DnSta & Num=  ,612.254, 4 ,597.346, 4 , 0 , 0 , 0 ,,
     5.5     5.5       5       5
   652.2   697.2   697.2   737.5
     5.5     5.5       5       5
   652.2   697.2   697.2  739.75
Pier Skew, UpSta & Num, DnSta & Num=  ,732.3, 4 ,724.847, 4 , 0 , 0 , 0 ,,
     5.5     5.5       5       5
   651.3   697.2   697.2  742.05
     5.5     5.5       5       5
   651.3   697.2   697.2 744.637
BR Coef=-1 , 0 , 0 ,, 0 ,,,0.8,-1,,0,
WSPro=,,,, 1 ,,,, 0 ,,,, 0 ,,,,-1 ,-1 ,-1 , 0 , 0 , 0 , 0 , 0
BC Design=,, 0 ,, 0 ,,,,,,
BC Use User HTab Curves=0
BC User HTab FreeFlow(D)= 0

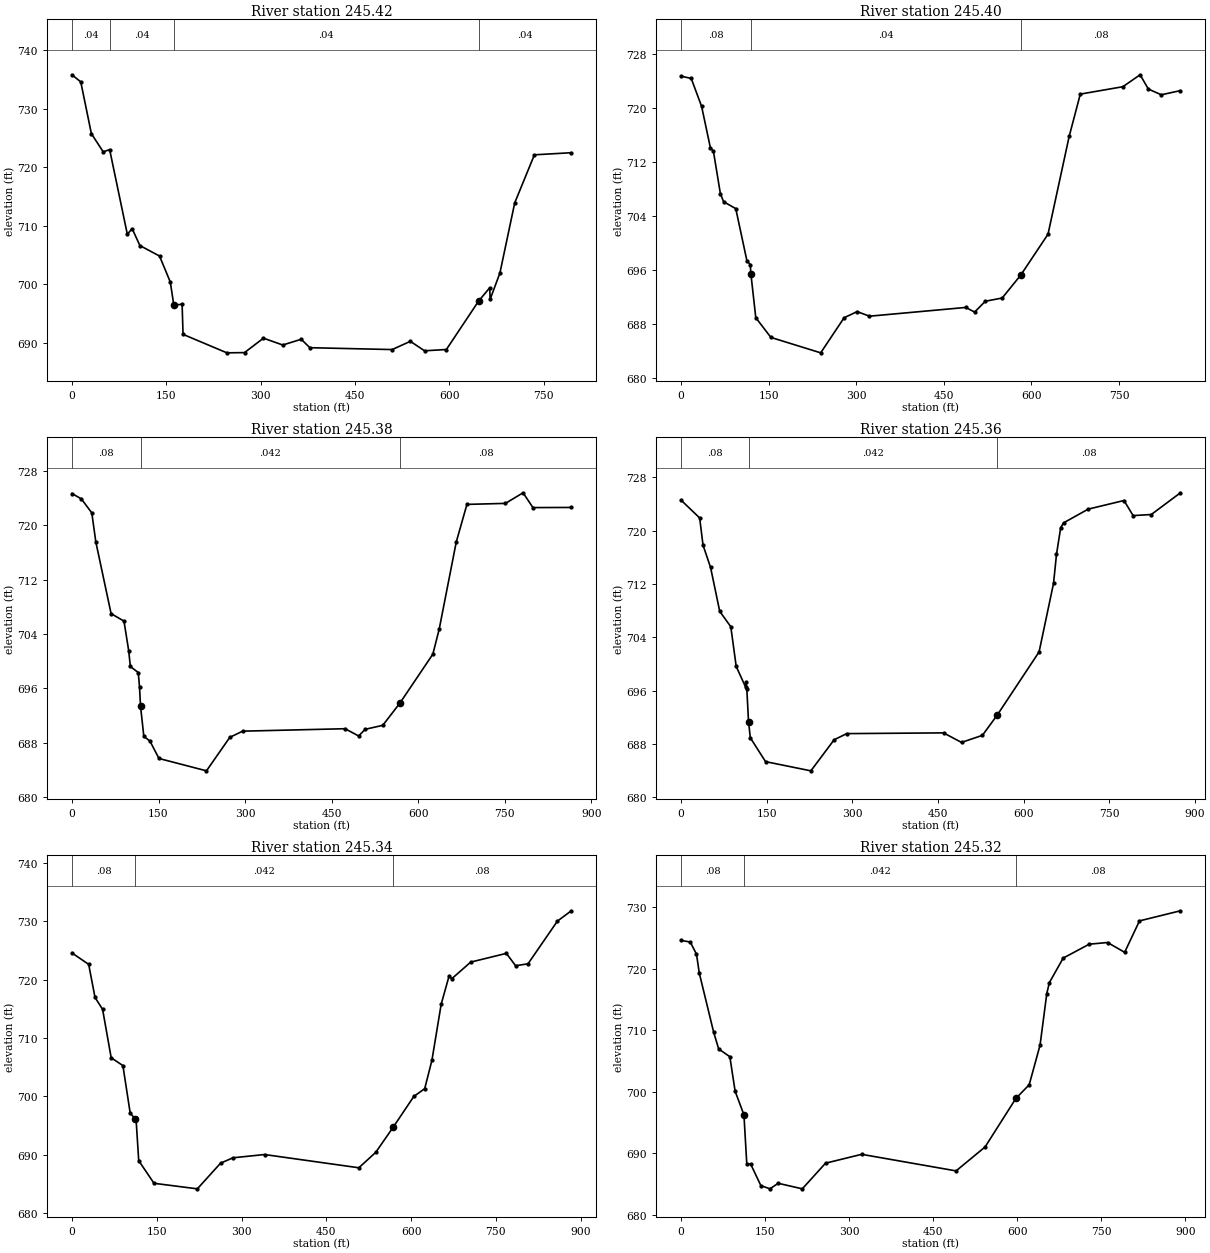
Type RM Length L Ch R = 1 ,245.42  ,755.6,402.5,22.2
XS GIS Cut Line= 6
      1825222.91       711355.31      1824672.33       711048.11
      1824492.65       710940.63       1824369.1       710857.66
      1824318.29       710813.84      1824273.83       710763.52
#Sta/Elev= 30
       0   735.8  14.029  734.58  30.893  725.73  49.717  722.62  59.956     723
  88.063  708.52  95.707  709.49 108.003  706.59 139.251   704.8  156.37  700.36
 162.019  696.38 175.157  696.56 176.692   691.4 246.391  688.24 274.421  688.28
 304.501  690.75 335.204  689.58 364.605  690.56  378.33  689.12 509.188   688.8
 538.094  690.21 560.665  688.59 595.391  688.81 646.515  697.07 664.362  699.38
 664.977   697.4  680.47  701.87 704.102   713.9 735.377  722.11 794.067  722.47
#Mann= 4 ,-1 , 0
       0     .04       0  59.956     .04       0 162.019     .04       0
 646.515     .04       0
Bank Sta=162.019,646.515
XS Rating Curve= 0 ,0
Skew Angle= 45
Exp/Cntr=0.3,0.1

Type RM Length L Ch R = 1 ,245.40  ,22.5,22.5,30
XS GIS Cut Line= 4
      1824988.76       710636.91      1824644.68        710669.3
      1824327.05       710699.19      1824170.98       710808.48
#Sta/Elev= 30
       0  724.77   17.37  724.44   35.18  720.28    50.2  714.14   55.33  713.65
   67.33  707.32   72.88  706.13   93.65  705.11  112.67   697.4  118.45   696.8
  119.51  695.46  127.93  688.92   153.8  685.99  239.07   683.7  279.19  688.91
  301.56  689.82  322.65  689.14  487.57  690.44  502.72  689.75  521.02  691.36
  549.89  691.84  581.67  695.24  628.38  701.31  664.63  715.84  683.67  722.11
   756.6  723.21  786.08  724.98  800.23  722.86  822.41  722.01  855.17  722.63
#Mann= 3 ,-1 , 0
       0     .08       0  119.51     .04       0  581.67     .08       0
Bank Sta=119.51,581.67
XS Rating Curve= 0 ,0
Exp/Cntr=0.3,0.1

Type RM Length L Ch R = 1 ,245.38  ,21.5,21.5,30
XS GIS Cut Line= 4
      1824984.07       710614.93      1824642.58       710647.08
      1824323.76       710677.08      1824152.63       710784.71
#Sta/Elev= 30
       0  724.67    16.3  723.88   34.42  721.82   41.37  717.55   67.84  706.99
   90.17  705.89   98.33  701.54  101.21  699.21  114.91  698.32  117.09  696.23
  118.83  693.38  124.56  688.93  135.17  688.23  150.82  685.67  233.12  683.85
  273.56  688.78  295.81  689.69  473.37  690.05  496.87  688.98  508.03  689.96
  538.66  690.55  568.17   693.8  625.42  701.02  636.44  704.71  666.01  717.54
  684.49  723.07  751.26  723.22   781.8  724.78  798.84   722.6  865.39  722.62
#Mann= 3 ,-1 , 0
       0     .08       0  118.83    .042       0  568.17     .08       0
Bank Sta=118.83,568.17
XS Rating Curve= 0 ,0
Exp/Cntr=0.3,0.1

Type RM Length L Ch R = 1 ,245.36  ,20.5,20.5,30.5
XS GIS Cut Line= 4
      1824979.53       710593.88      1824640.58       710625.78
      1824320.64        710655.9      1824135.01       710760.21
#Sta/Elev= 30
       0  724.56   32.56   721.9   38.44  717.82   51.69  714.47   67.69   707.9
    87.1  705.59   96.56  699.64  113.25   696.5  113.84  697.34  115.17  696.22
  118.14  691.38  121.28  688.95  147.94  685.37  227.36  683.99  268.13  688.65
  290.22  689.57  459.74  689.68  491.21  688.25  527.84  689.31  554.14  692.39
  627.11  701.82  652.42  712.09  657.61  716.44  664.98  720.45  669.96  721.16
  713.18  723.22  775.79  724.51  791.87  722.25  823.61  722.41  874.73  725.67
#Mann= 3 ,-1 , 0
       0     .08       0  118.14    .042       0  554.14     .08       0
Bank Sta=118.14,554.14
XS Rating Curve= 0 ,0
Exp/Cntr=0.3,0.1

Type RM Length L Ch R = 1 ,245.34  ,20,20,30.5
XS GIS Cut Line= 4
      1824975.15       710573.61      1824638.65       710605.28
      1824317.65       710635.49      1824118.14       710734.97
#Sta/Elev= 30
       0  724.56   29.58  722.61   40.83  716.93   54.18  714.91   69.42  706.59
   90.13  705.26  102.99  697.14  111.48  696.14  113.32  696.21  118.11  688.96
  145.15  685.08  221.81  684.13   262.9  688.53  284.81  689.45  340.74  690.01
  507.47  687.74  537.43  690.39  568.41  694.72   604.7  699.96  623.99   701.3
  636.79  706.17  653.14  715.77  667.13  720.62  671.85  720.14  705.32  722.99
  768.43  724.49  784.82  722.37  806.72   722.7  858.75  730.02  883.34  731.79
#Mann= 3 ,-1 , 0
       0     .08       0  111.48    .042       0  568.41     .08       0
Bank Sta=111.48,568.41
XS Rating Curve= 0 ,0
Exp/Cntr=0.3,0.1

Type RM Length L Ch R = 1 ,245.32  ,19.5,19.5,31
XS GIS Cut Line= 4
      1824970.84       710553.99      1824636.78       710585.44
      1824314.73       710615.75      1824102.04       710708.97
#Sta/Elev= 30
       0  724.57   16.36  724.31    27.5  722.34   32.52  719.26   58.13  709.68
   67.09  706.96   87.03   705.7   96.45   700.1  112.18  696.27  117.25  688.34
  124.38  688.24  142.37  684.79  158.56  684.26  173.33  685.16  216.36  684.26
  257.75  688.42  322.29  689.86  490.79  687.17  542.59  691.06  597.53  698.93
  621.29  701.15  640.67  707.58  652.69  715.95  657.28  717.72  681.93   721.7
  728.45  723.96   761.2  724.23  791.65  722.64  818.12  727.74  891.23  729.38
#Mann= 3 ,-1 , 0
       0     .08       0  112.18    .042       0  597.53     .08       0
Bank Sta=112.18,597.53
XS Rating Curve= 0 ,0
Exp/Cntr=0.3,0.1

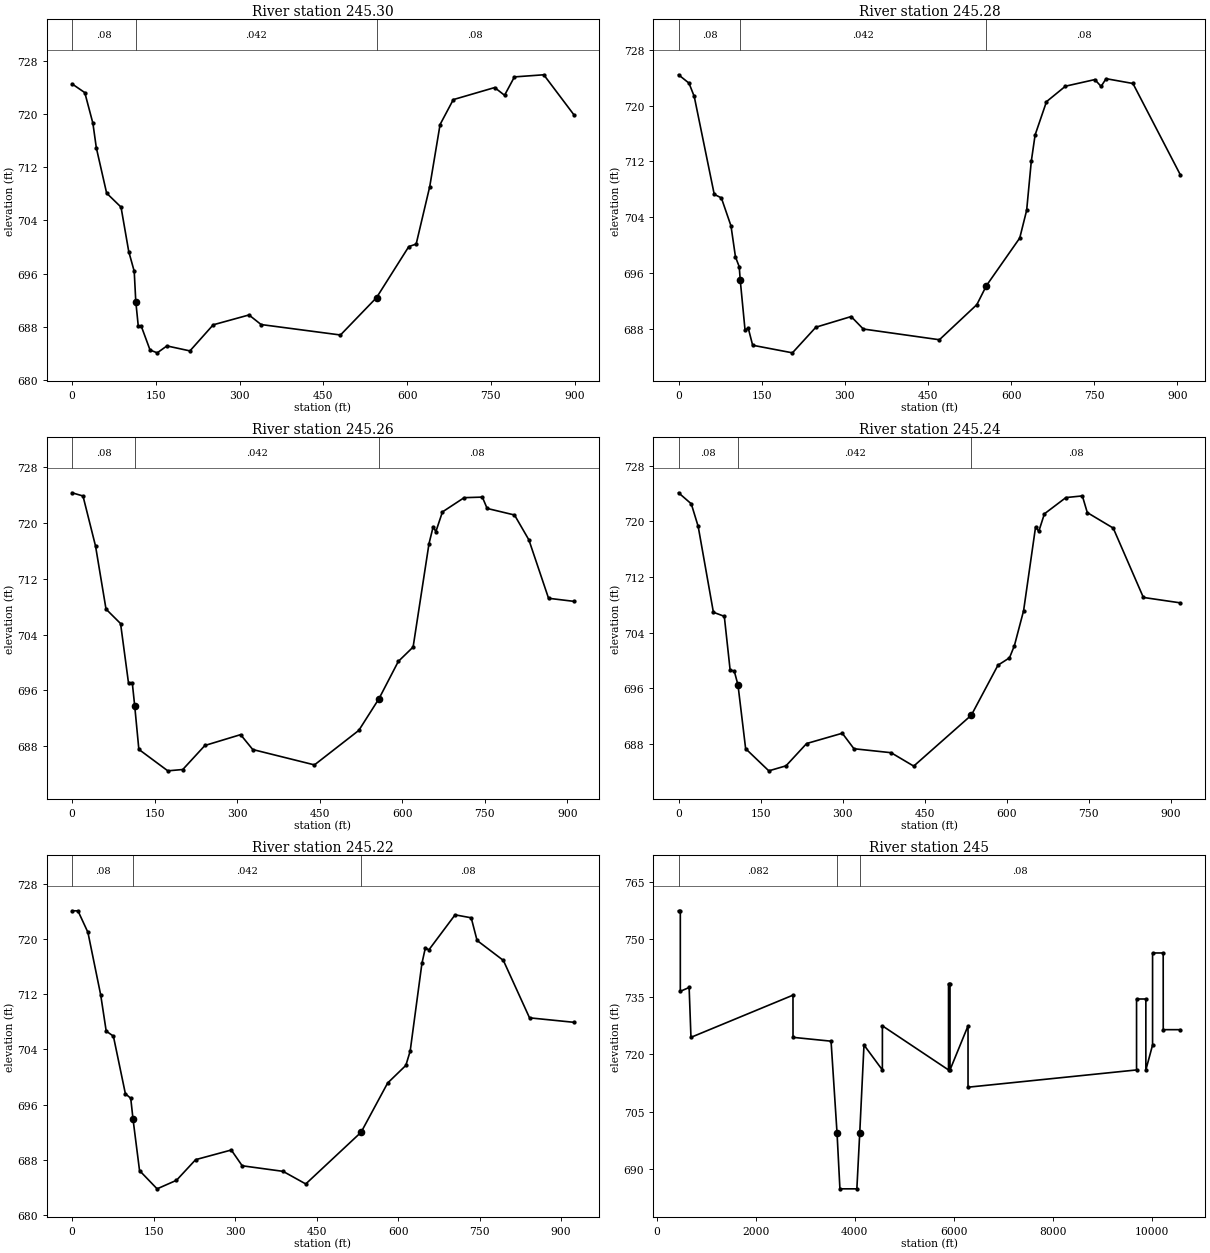
Type RM Length L Ch R = 1 ,245.30  ,19,19,31
XS GIS Cut Line= 4
      1824966.62       710534.91      1824634.96       710566.12
      1824311.89       710596.53      1824086.73       710682.22
#Sta/Elev= 30
       0   724.5   22.79  723.19   37.31  718.58   43.41  714.91   61.89  708.09
   87.66  705.99   101.5  699.31  111.29  696.35  114.09   691.8  118.61  688.07
   123.6  688.18  139.64  684.52  152.52   684.1  169.83  685.14  211.05  684.39
  252.72  688.31  316.81  689.79  338.48  688.35  480.63  686.78  545.26   692.4
  602.95  700.06  616.16  700.44  640.48  709.08  658.98   718.4  682.67  722.14
   756.7  723.95  774.44  722.79   792.1  725.55  844.66  725.87  898.54  719.87
#Mann= 3 ,-1 , 0
       0     .08       0  114.09    .042       0  545.26     .08       0
Bank Sta=114.09,545.26
XS Rating Curve= 0 ,0
Exp/Cntr=0.3,0.1

Type RM Length L Ch R = 1 ,245.28  ,18.5,18.5,31.5
XS GIS Cut Line= 4
      1824962.49       710516.15      1824633.18       710547.14
      1824309.49       710577.61      1824072.24        710654.7
#Sta/Elev= 30
       0  724.44   18.86  723.24   28.31  721.33   64.42  707.28    77.3  706.76
   94.65  702.74  102.72  698.29  109.52  696.88  111.34  694.94  119.97  687.81
  125.84  688.05  133.72  685.61  205.49  684.52   247.8   688.2  311.45  689.73
  333.33  687.94  470.66   686.4  538.22  691.44  555.51  694.17  615.59     701
   628.1  704.99  636.43     712  643.33   715.8  663.87  720.58  698.06   722.8
  751.11  723.75  762.39  722.77  771.42  723.88  819.85  723.19  905.35  710.08
#Mann= 3 ,-1 , 0
       0     .08       0  111.34    .042       0  555.51     .08       0
#XS Ineff= 2 , 0
       0                  717.25       0
Permanent Ineff=
       F       T
Bank Sta=111.34,555.51
XS Rating Curve= 0 ,0
Exp/Cntr=0.3,0.1

Type RM Length L Ch R = 1 ,245.26  ,18.5,18.5,31.5
XS GIS Cut Line= 4
      1824958.46       710497.65      1824631.42       710528.43
      1824307.58       710558.91       1824058.6       710626.41
#Sta/Elev= 30
       0  724.29   19.84  723.83   42.65  716.66   61.69  707.64   88.12  705.57
  102.54  697.06  109.38  697.11  113.82  693.77  121.35  687.56  173.95  684.49
  201.17  684.68  241.33  688.12  306.21  689.67  328.27  687.54  440.42  685.34
  521.02  690.28  557.73  694.83  592.76  700.15  619.66  702.21  648.56  717.02
  656.13  719.44  660.95  718.72  672.95  721.55  712.38  723.59  745.46  723.67
  754.14  722.05  803.87  721.11  830.01  717.55  865.74  709.19  911.73  708.75
#Mann= 3 ,-1 , 0
       0     .08       0  113.82    .042       0  557.73     .08       0
#XS Ineff= 2 , 0
       0                  712.38       0
Permanent Ineff=
       F       T
Bank Sta=113.82,557.73
XS Rating Curve= 0 ,0
Exp/Cntr=0.3,0.1

Type RM Length L Ch R = 1 ,245.24  ,18.5,18.5,23
XS GIS Cut Line= 4
      1824954.51       710479.49      1824629.69       710510.07
       1824305.4       710540.59      1824045.85       710597.34
#Sta/Elev= 30
       0  724.13   23.31  722.54   35.95  719.28   63.74  706.94    83.7  706.35
   94.31  698.66     102  698.45  108.73  696.47  122.71  687.31  165.08  684.12
  196.54  684.84  234.25  688.05  299.47  689.53  320.78   687.3  388.68  686.73
  430.12   684.8  535.48  692.13  584.17  699.32  605.23  700.38  614.25  702.14
  631.03  707.16  652.93  719.21  658.81  718.58  669.09   721.1   708.4  723.44
  738.49  723.68  747.52  721.28  794.95  719.05  850.07  709.07  917.66  708.29
#Mann= 3 ,-1 , 0
       0     .08       0  108.73    .042       0  535.48     .08       0
#XS Ineff= 2 , 0
       0                  706.93       0
Permanent Ineff=
       F       F
Bank Sta=108.73,535.48
XS Rating Curve= 0 ,0
Exp/Cntr=0.3,0.1

Type RM Length L Ch R = 1 ,245.22  ,785,973.5,1273
XS GIS Cut Line= 4
      1824950.77       710461.49      1824627.98       710491.87
      1824303.25       710522.44      1824034.03       710567.49
#Sta/Elev= 30
       0  724.14   10.85  724.13   29.15  721.01   52.74  711.89   62.81  706.66
   76.04  705.93   98.09  697.57  107.96   696.9  112.19  693.85  124.16   686.4
  156.47  683.75  192.13  684.99  227.41  687.99  292.96  689.39  313.07   687.1
  388.24  686.29  430.02  684.46  531.83  691.97  580.69  699.12   614.2  701.68
  622.15  703.76  643.75  716.49  650.14  718.77  656.46  718.45  704.77  723.55
  734.47  723.12  745.24  719.83  793.63  716.93  841.78  708.59  923.35  707.94
#Mann= 3 ,-1 , 0
       0     .08       0  112.19    .042       0  531.83     .08       0
#XS Ineff= 2 , 0
       0                  704.77       0
Permanent Ineff=
       F       T
Bank Sta=112.19,531.83
XS Rating Curve= 0 ,0
Exp/Cntr=0.3,0.1

Type RM Length L Ch R = 1 ,245     ,2333.8,2333.8,2333.8
BEGIN DESCRIPTION:
Geometry from duplicate effective model
END DESCRIPTION:
XS GIS Cut Line= 3
  1825039.114006  709681.1923788 1824406.2707844  709415.4931071
  1824177.840467  709315.5946848
#Sta/Elev= 30
     444   757.4     480   757.4     480   736.4     658   737.4     695   724.4
    2755   735.4    2756   724.4    3524   723.4    3645   699.4    3703   684.9
    4045   684.9    4103   699.4    4189   722.4    4560   715.9    4561   727.4
    5896   715.9    5896   738.4    5926   738.4    5926   715.9    6290   727.4
    6290   711.4    9693   715.9    9693   734.4    9881   734.4    9881   715.9
 10016.5   722.4 10016.5   746.4   10231   746.4   10232   726.4   10577   726.4
#Mann= 3 , 0 , 0
     444    .082       0    3645     .05       0    4103     .08       0
#XS Ineff= 2 , 0
            3645   699.4    4103           699.4
Permanent Ineff=
       F       F
#Block Obstruct= 2 , 0
                            4300
Bank Sta=3645,4103
XS Rating Curve= 0 ,0
Exp/Cntr=0.3,0.1

Chan Stop Cuts=-1
Use User Specified Reach Order=0
Composite Channel Slope=5

--- FRA-70-1321R.g01 (geometry) ---

Geom Title=PostProject_Stantec
Program Version=4.10
BEGIN GEOM DESCRIPTION:
Vertical Datum = NAVD 88
Projection = State Plane Ohio South
END GEOM DESCRIPTION:

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
River Reach=SciotoRiver     ,SciotoRiver

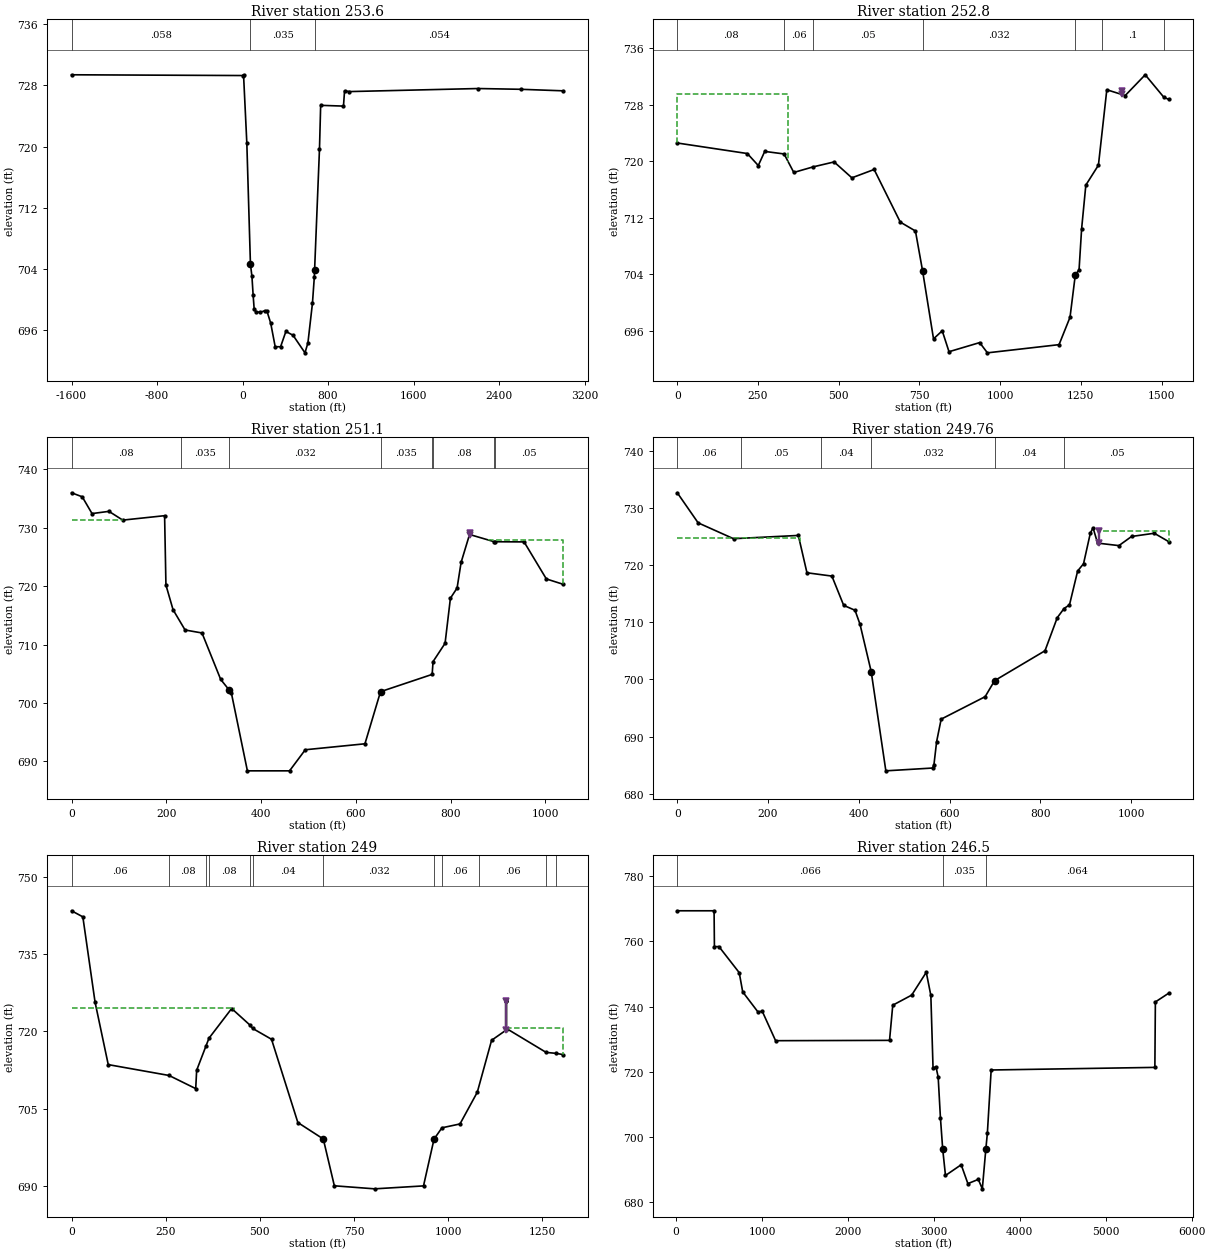
Type RM Length L Ch R = 1 ,253.6   ,610,610,610
BEGIN DESCRIPTION:
AL
END DESCRIPTION:
Node Name=AL
XS GIS Cut Line= 2
   1824073.55393  716248.8665794 1824066.1664777  715533.1869084
#Sta/Elev= 30
   -1600   729.4     4.7   729.3     9.4   729.4      40   720.5    73.9   704.6
      88     703    98.9   700.6   108.4   698.8   123.3   698.4   163.4   698.3
   205.7   698.5   227.5   698.5   263.3   696.9   305.5   693.8   356.1   693.8
   405.6   695.8   472.6   695.3   584.2     693   611.7   694.3   654.2   699.5
   671.5   702.9   674.1   703.8     720   719.7     731   725.4   944.5   725.3
   954.6   727.3   999.2   727.2  2203.5   727.6  2602.4   727.5  2999.1   727.3
#Mann= 3 , 0 , 0
   -1600    .058       0    73.9    .035       0   674.1    .054       0
#Block Obstruct= 2 , 0
                            1000
Bank Sta=73.9,674.1
XS Rating Curve= 0 ,0
Exp/Cntr=0.3,0.1

Type RM Length L Ch R = 1 ,252.8   ,816.3,590.47,312.21
BEGIN DESCRIPTION:
Overbank geometry from 2011 City of Columbus LiDAR data.  Channel geometry from proposed design plans.
END DESCRIPTION:
XS GIS Cut Line= 3
1825059.28161752716827.0005937671825102.24511428715305.381917849
 1825102.2453968715305.371912071
#Sta/Elev= 30
       0  722.55  216.89  721.06  250.87  719.36  270.86  721.36  330.83     721
  360.82  718.38  420.79  719.17  485.75  719.87  540.72  717.62  609.69   718.8
  690.65  711.35  737.62  710.09  759.86  704.41  793.59  694.82  820.58  695.96
  841.57     693  936.52  694.29  960.51  692.84 1182.39     694 1216.37  697.88
 1232.68  703.86 1244.36   704.6 1252.35  710.44 1265.35  716.59 1304.33  719.41
 1330.31  730.09 1387.28  729.27 1449.25  732.21 1507.23  729.01 1522.23  728.73
#Mann= 7 ,-1 , 0
       0     .08       0  330.83     .06       0  420.79     .05       0
  759.86    .032       0 1232.68     .04       0 1314.32      .1       0
 1507.23     .05       0
Levee=0,,,-1,1377,729.9,,
#XS Ineff= 2 , 0
       0   344.3   729.5               0
Permanent Ineff=
       F       F
Bank Sta=759.86,1232.68
XS Rating Curve= 0 ,0
Exp/Cntr=0.5,0.3

Type RM Length L Ch R = 1 ,251.1   ,179.49,235.17,283.09
BEGIN DESCRIPTION:
Overbank geometry from 2011 City of Columbus LiDAR data.  Channel geometry from proposed design plans.
END DESCRIPTION:
XS GIS Cut Line= 3
1827493.87156461 714879.32863611 1826405.4665892714696.734513104
1826405.45671739714696.732856979
#Sta/Elev= 30
       0     736  22.543  735.31  43.207  732.44  78.906  732.82 108.027  731.32
  196.33  732.08 199.149  720.21 214.175  715.98 239.537  712.51 275.236     712
 314.684  704.05 332.538  702.24 337.237  701.72  371.02   688.4  459.99   688.4
 493.169  692.01 619.041  693.03 651.912  701.95 760.879  704.91 762.758   707.1
  788.12  710.23 799.397  717.95 813.482  719.69  821.94  724.08 839.784  728.86
 891.571727.6287 892.699727.6191  954.85  727.591001.825  721.251037.064  720.34
#Mann= 8 ,-1 , 0
       0     .08       0  231.08    .035       0 332.538    .032       0
 651.912    .035       0 760.879    .035       0 762.758     .08       0
 891.571     .06       0 892.699     .05       0
Levee=0,,,-1,839.74,729.04,,
#XS Ineff= 2 , 0
       0  107.95  731.34  879.61       0  727.86
Permanent Ineff=
       F       F
Bank Sta=332.538,651.912
XS Rating Curve= 0 ,0
Skew Angle= 20
Exp/Cntr=0.5,0.3

Type RM Length L Ch R = 1 ,249.76  ,150.75,205.87,256.95
BEGIN DESCRIPTION:
Overbank geometry from 2011 City of Columbus LiDAR data.  Channel geometry from proposed design plans.
END DESCRIPTION:
XS GIS Cut Line= 2
   1827260.08299   712790.621527   1826337.86075    713358.67715
#Sta/Elev= 30
       0  732.63   45.96  727.37   123.9   724.6  266.79  725.17  285.77  718.64
  340.73  718.06  366.71  712.94  391.69  712.08  402.68  709.64  427.35  701.35
  459.63     684  562.55  684.49  565.55  685.03  571.54  689.12  581.54  693.04
  678.46  696.97  699.27  699.77  810.35     705  837.33  710.78  852.32  712.39
  864.31  713.02   882.3  718.95  895.29  720.22  910.27  725.57  916.27   726.5
  926.26  723.83  973.22  723.39  1001.2  724.99 1051.16  725.55 1083.14  724.08
#Mann= 6 ,-1 , 0
       0     .06       0  141.17     .05       0  317.39     .04       0
  427.35    .032       0  699.27     .04       0  852.32     .05       0
Levee=0,,,-1,929.12,726,,
#XS Ineff= 2 , 0
       0  269.97  724.73  929.12       0     726
Permanent Ineff=
       F       F
Bank Sta=427.35,699.27
XS Rating Curve= 0 ,0
Exp/Cntr=0.5,0.3

Type RM Length L Ch R = 1 ,249     ,156.71,155.69,155.43
BEGIN DESCRIPTION:
Overbank geometry from 2011 City of Columbus LiDAR data.  Channel geometry from proposed design plans.
END DESCRIPTION:
XS GIS Cut Line= 4
1826591.64108561 711915.406414361826471.59965903712361.660115018
1826000.89521986713061.0957240161826000.89521986713061.095724017
#Sta/Elev= 30
       0  743.43   29.98  742.25   62.45  725.68   97.42  713.56  258.88711.4537
  329.73   708.9  332.22  712.46  356.89717.1614  364.93718.6832  425.19  724.45
   473.1  721.28   481.1  720.58  531.04  718.48  600.97  702.31  668.51  699.12
  697.86  690.03  804.75  689.44  934.61  690.01  962.57  699.09  983.55  701.29
  1031.5  702.04 1077.45   708.2 1115.41  718.28    1153  720.21    1153  725.82
    1155  725.82    1155  720.57 1260.24715.9334 1286.31715.7479 1305.19  715.51
#Mann= 12 ,-1 , 0
       0     .06       0  258.88     .08       0  356.89     .06       0
  364.93     .08       0   473.1     .05       0   481.1     .04       0
  668.51    .032       0  962.57     .04       0  983.55     .06       0
 1081.44     .06       0 1260.24     .08       0 1286.31     .06       0
Levee=0,,,-1,1153,725.82,,
#XS Ineff= 2 , 0
       0   430.3  724.51 1156.65       0  720.58
Permanent Ineff=
       F       F
Bank Sta=668.51,962.57
XS Rating Curve= 0 ,0
Exp/Cntr=0.3,0.1

Type RM Length L Ch R = 1 ,246.5   ,95.04,95.04,95.04
XS GIS Cut Line= 5
  1825704.643843  711666.7176072 1825179.9345914  711665.4731871
 1825030.2006389  711612.0835301 1824664.6524855  711715.1840457
 1824436.8537285  711819.3885617
#Sta/Elev= 30
    14.6   769.4   442.8   769.4   446.7   758.4   499.4   758.4   735.3   750.4
   775.8   744.5   951.2   738.4    1004   738.5  1158.6   729.5  2484.4   729.6
  2521.9   740.4  2742.1   743.5  2911.9   750.5  2965.1   743.4  2990.5   721.2
  3025.6   721.4  3050.4   718.3  3076.7   705.8  3103.3   696.1  3135.4   688.1
  3318.1   691.4  3396.1   685.6  3517.2   686.9  3564.1     684  3604.9   696.2
  3622.5     701  3666.9   720.5  5571.9   721.3  5577.7   741.4  5733.7   744.1
#Mann= 3 , 0 , 0
    14.6    .066       0  3103.3    .035       0  3604.9    .064       0
#Block Obstruct= 2 , 0
                            3800
Bank Sta=3103.3,3604.9
XS Rating Curve= 0 ,0
Exp/Cntr=0.3,0.1

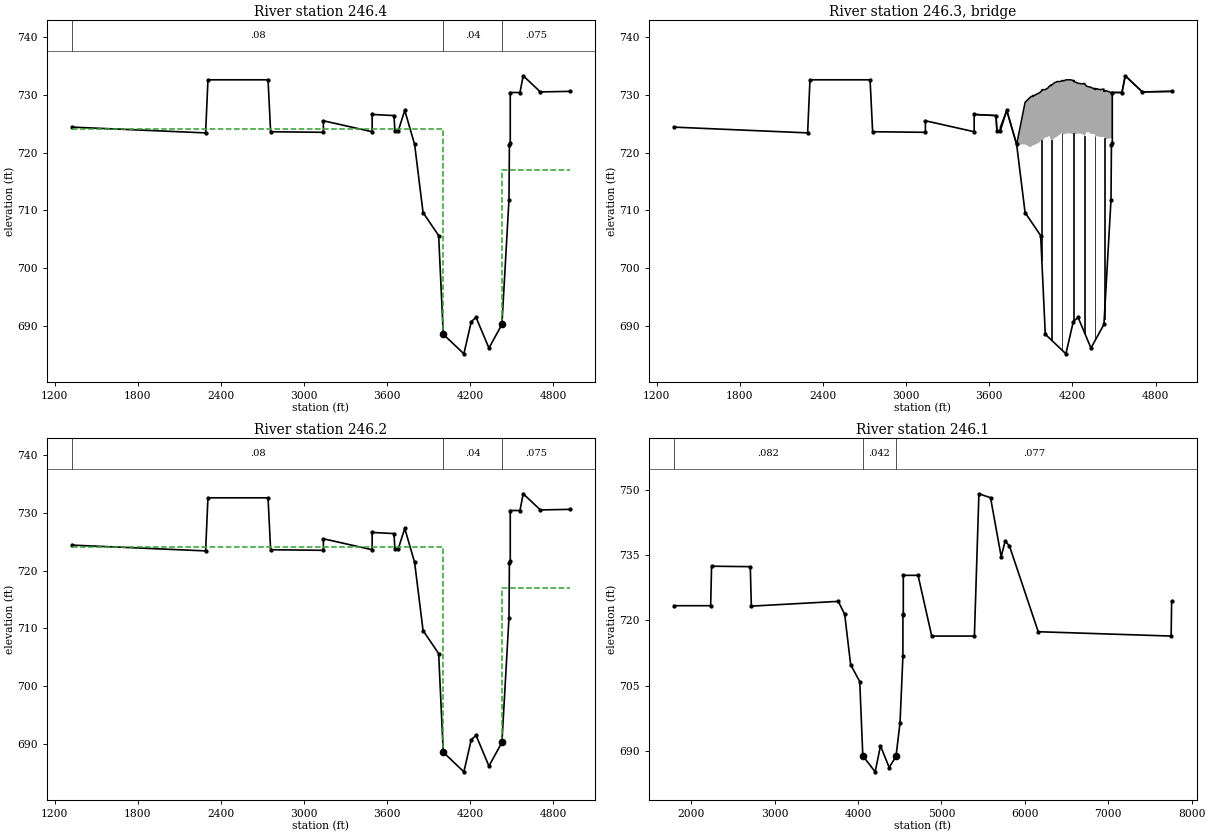
Type RM Length L Ch R = 1 ,246.4   ,301.5,301.5,301.5
BEGIN DESCRIPTION:
REPEATED section.  I-70 East/West Bridge - Upstream Section
END DESCRIPTION:
XS GIS Cut Line= 5
  1827976.925716  711577.1068941 1825196.4739284   711570.512091
 1825033.5707109  711512.4265772 1824631.8047821  711625.7422955
 1824397.3351067  711732.9983146
#Sta/Elev= 30
  1323.1   724.4  2288.7   723.4  2305.5   732.6  2739.4   732.6  2757.9   723.6
  3138.9   723.5  3138.9   725.5  3490.9   723.6  3490.9   726.6  3648.5   726.4
  3655.2   723.7  3678.6   723.7  3726.3   727.3  3797.5   721.4  3858.4   709.6
    3971   705.6  4004.3   688.5  4153.2   685.1  4206.6   690.7  4241.4   691.4
  4334.1   686.1  4427.7   690.2  4478.7   711.8  4481.8   721.3    4488   721.6
    4488   730.4    4558   730.4  4581.5   733.3  4705.3   730.5  4916.5   730.6
#Mann= 3 , 0 , 0
  1323.1     .08       0  4004.3     .04       0  4427.7    .075       0
#XS Ineff= 2 , 0
       0  4004.3     724  4427.7       0     717
Permanent Ineff=
       F       F
#Block Obstruct= 2 , 0
                            4600
Bank Sta=4004.3,4427.7
XS Rating Curve= 0 ,0
Exp/Cntr=0.3,0.1

Type RM Length L Ch R = 3 ,246.3   ,,,
BEGIN DESCRIPTION:
Structure #5 Interstate 70/71 Bridge
END DESCRIPTION:
Bridge Culvert--1,0,-1,-1, 0
Deck Dist Width WeirC Skew NumUp NumDn MinLoCord MaxHiCord MaxSubmerge Is_Ogee
1,300,2.6,0, 69, 69, 734.4, , 0.95, 0, 0,0,,
  3490.9  3648.5  3655.2  3678.6  3679.9  3726.3  3797.5  3858.4  3896.5    3912
    3912  3915.9  3916.8  3957.8    3971  3976.4  3977.2  3981.1  3983.4  3988.8
  4004.3  4023.7  4033.8  4044.7  4044.7  4047.8  4050.9  4071.1  4091.2    4109
  4122.2    4123  4127.6  4128.4  4136.9  4153.2  4187.3  4205.1  4206.6  4208.2
  4212.8  4212.8  4241.4  4272.3  4285.5  4286.3  4289.3  4289.4  4301.6  4318.7
  4334.1  4361.9  4361.9  4366.6  4366.6  4399.1  4427.7  4427.9  4432.3  4432.3
  4445.5  4478.7  4481.8    4488    4488    4558  4581.5  4705.3  4916.5
   726.6   726.4   723.7   723.7   724.4   727.3   721.4   728.7   729.6   729.8
   729.7   729.9   729.8   730.3   730.5   730.7   730.7   730.9   730.8   730.9
   730.9   731.2   731.5   731.7   731.6   731.6   731.7   732.1   732.3   732.3
   732.4   732.4   732.5   732.5   732.4   732.6   732.6   732.5   732.4   732.3
   732.5   732.3     732   731.9     732   731.9   731.9   731.9   731.5   731.4
   731.3     731   731.1   730.9   731.1   730.9     731   730.6   730.7   730.6
   730.7   730.4   730.4   730.4   730.4   730.4   733.3   730.5   730.6
   726.6   726.4   723.7   723.7   724.4   727.3   721.4   721.4   720.9   721.2
   721.2   721.3   721.2   721.7     722   722.2   722.1   722.2   722.1   722.2
   722.6   722.7   722.9   722.2   722.4     722     722   722.5   722.8   723.1
   723.4   723.4   723.3   723.3   723.1   723.3   723.3   723.2   723.2   723.2
   723.5   723.1   723.3   723.2   722.9   722.9   722.8   722.8   723.5   723.5
   723.2   723.2   723.1   722.7   722.9   722.7   722.7   722.5   722.7   722.6
   722.3   722.5   722.5   722.5   730.4   730.4   733.3   730.5   730.6
  3490.9  3648.5  3655.2  3678.6  3679.9  3726.3  3797.5  3858.4  3896.5    3912
    3912  3915.9  3916.8  3957.8    3971  3976.4  3977.2  3981.1  3983.4  3988.8
  4004.3  4023.7  4033.8  4044.7  4044.7  4047.8  4050.9  4071.1  4091.2    4109
  4122.2    4123  4127.6  4128.4  4136.9  4153.2  4187.3  4205.1  4206.6  4208.2
  4212.8  4212.8  4241.4  4272.3  4285.5  4286.3  4289.3  4289.4  4301.6  4318.7
  4334.1  4361.9  4361.9  4366.6  4366.6  4399.1  4427.7  4427.9  4432.3  4432.3
  4445.5  4478.7  4481.8    4488    4488    4558  4581.5  4705.3  4916.5
   726.6   726.4   723.7   723.7   724.4   727.3   721.4   728.7   729.6   729.8
   729.7   729.9   729.8   730.3   730.5   730.7   730.7   730.9   730.8   730.9
   730.9   731.2   731.5   731.7   731.6   731.6   731.7   732.1   732.3   732.3
   732.4   732.4   732.5   732.5   732.4   732.6   732.6   732.5   732.4   732.3
   732.5   732.3     732   731.9     732   731.9   731.9   731.9   731.5   731.4
   731.3     731   731.1   730.9   731.1   730.9     731   730.6   730.7   730.6
   730.7   730.4   730.4   730.4   730.4   730.4   733.3   730.5   730.6
   726.6   726.4   723.7   723.7   724.4   727.3   721.4   721.4   720.9   721.2
   721.2   721.3   721.2   721.7     722   722.2   722.1   722.2   722.1   722.2
   722.6   722.7   722.9   722.2   722.4     722     722   722.5   722.8   723.1
   723.4   723.4   723.3   723.3   723.1   723.3   723.3   723.2   723.2   723.2
   723.5   723.1   723.3   723.2   722.9   722.9   722.8   722.8   723.5   723.5
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Pier Skew, UpSta & Num, DnSta & Num=  ,3914, 2 ,3914, 2 , 0 , 0 , 0 ,,
     4.8     3.9
   701.4   721.3
     4.8     3.9
   701.4   721.3
Pier Skew, UpSta & Num, DnSta & Num=  ,3979.2, 2 ,3979.2, 2 , 0 , 0 , 0 ,,
       7     3.9
   690.4   722.2
       7     3.9
   690.4   722.2
Pier Skew, UpSta & Num, DnSta & Num=  ,4046.3, 2 ,4046.3, 2 , 0 , 0 , 0 ,,
     6.2     3.1
   688.4   722.4
     6.2     3.1
   688.4   722.4
Pier Skew, UpSta & Num, DnSta & Num=  ,4125.3, 2 ,4125.3, 2 , 0 , 0 , 0 ,,
     6.2     4.6
   685.4   723.4
     6.2     4.6
   685.4   723.4
Pier Skew, UpSta & Num, DnSta & Num=  ,4210.5, 2 ,4210.5, 2 , 0 , 0 , 0 ,,
     6.2     4.6
   677.4   723.5
     6.2     4.6
   677.4   723.5
Pier Skew, UpSta & Num, DnSta & Num=  ,4287.8, 2 ,4287.8, 2 , 0 , 0 , 0 ,,
     3.9       3
   677.4   722.9
     3.9       3
   677.4   722.9
Pier Skew, UpSta & Num, DnSta & Num=  ,4364.3, 2 ,4364.3, 2 , 0 , 0 , 0 ,,
     4.7     4.7
   677.4   723.1
     4.7     4.7
   677.4   723.1
Pier Skew, UpSta & Num, DnSta & Num=  ,4430.1, 2 ,4430.1, 2 , 0 , 0 , 0 ,,
     4.6     4.4
   678.4   722.7
     4.6     4.4
   678.4   722.7
BR Coef=-1 , 0 , 0 ,, 0 ,,,0.8,-1,,0,
WSPro=,,,, 1 ,,,, 0 ,,,, 0 ,,,,-1 ,-1 ,-1 , 0 , 0 , 0 , 0 , 0
BC Design=,, 0 ,, 0 ,,,,,,
BC HTab HWMax=733.3
BC Use User HTab Curves=0
BC User HTab FreeFlow(D)= 0

Type RM Length L Ch R = 1 ,246.2   ,95.04,95.04,95.04
BEGIN DESCRIPTION:
I-70 East/West Bridge - Downstream Section
END DESCRIPTION:
XS GIS Cut Line= 3
  1827215.061426  711264.8230698 1824528.7206707  711242.9838746
 1824335.0471736   711138.166499
#Sta/Elev= 30
  1323.1   724.4  2288.7   723.4  2305.5   732.6  2739.4   732.6  2757.9   723.6
  3138.9   723.5  3138.9   725.5  3490.9   723.6  3490.9   726.6  3648.5   726.4
  3655.2   723.7  3678.6   723.7  3726.3   727.3  3797.5   721.4  3858.4   709.6
    3971   705.6  4004.3   688.5  4153.2   685.1  4206.6   690.7  4241.4   691.4
  4334.1   686.1  4427.7   690.2  4478.7   711.8  4481.8   721.3    4488   721.6
    4488   730.4    4558   730.4  4581.5   733.3  4705.3   730.5  4916.5   730.6
#Mann= 3 , 0 , 0
  1323.1     .08       0  4004.3     .04       0  4427.7    .075       0
#XS Ineff= 2 , 0
       0  4004.3     724  4427.7       0     717
Permanent Ineff=
       F       F
#Block Obstruct= 2 , 0
                            5645
Bank Sta=4004.3,4427.7
XS Rating Curve= 0 ,0
Exp/Cntr=0.3,0.1

Type RM Length L Ch R = 1 ,246.1   ,1671.92,1671.92,1671.92
BEGIN DESCRIPTION:
Taken from effective Model
END DESCRIPTION:
XS GIS Cut Line= 3
  1825004.674115  711151.8501986 1824553.1402413  711148.1792742
 1824380.2642747  711054.6174535
#Sta/Elev= 30
    1793   723.4  2233.9   723.4  2244.7   732.5  2708.8   732.4  2721.5   723.3
  3763.8   724.4  3840.6   721.4    3912   709.8    4021   705.9  4057.8   688.8
  4205.7   685.1  4269.7   691.1  4373.9   686.1    4456   688.7  4503.9   696.4
  4538.4   711.7  4538.5   721.5  4543.1   721.3  4543.1   730.4    4720   730.4
  4883.9   716.4  5395.4   716.4  5449.6   749.2  5588.9   748.3  5716.6   734.7
  5764.4   738.3  5815.2   737.2  6160.5   717.4  7753.8   716.4    7760   724.4
#Mann= 3 , 0 , 0
    1793    .082       0  4057.8    .042       0    4456    .077       0
#XS Ineff= 2 , 0
          4057.8   688.8    4456           688.7
Permanent Ineff=
       F       F
#Block Obstruct= 2 , 0
                            4710
Bank Sta=4057.8,4456
XS Rating Curve= 0 ,0
Exp/Cntr=0.3,0.1

--- FRA-70-1321R.g02 (geometry) ---

Geom Title=Duplicate_Effective_Stantec
Program Version=4.10
BEGIN GEOM DESCRIPTION:
Elevations in NGVD 29
END GEOM DESCRIPTION:

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
River Reach=SciotoRiver     ,SciotoRiver
Reach XY= 2
       0.5000671       0.5435918             0.5            0.05

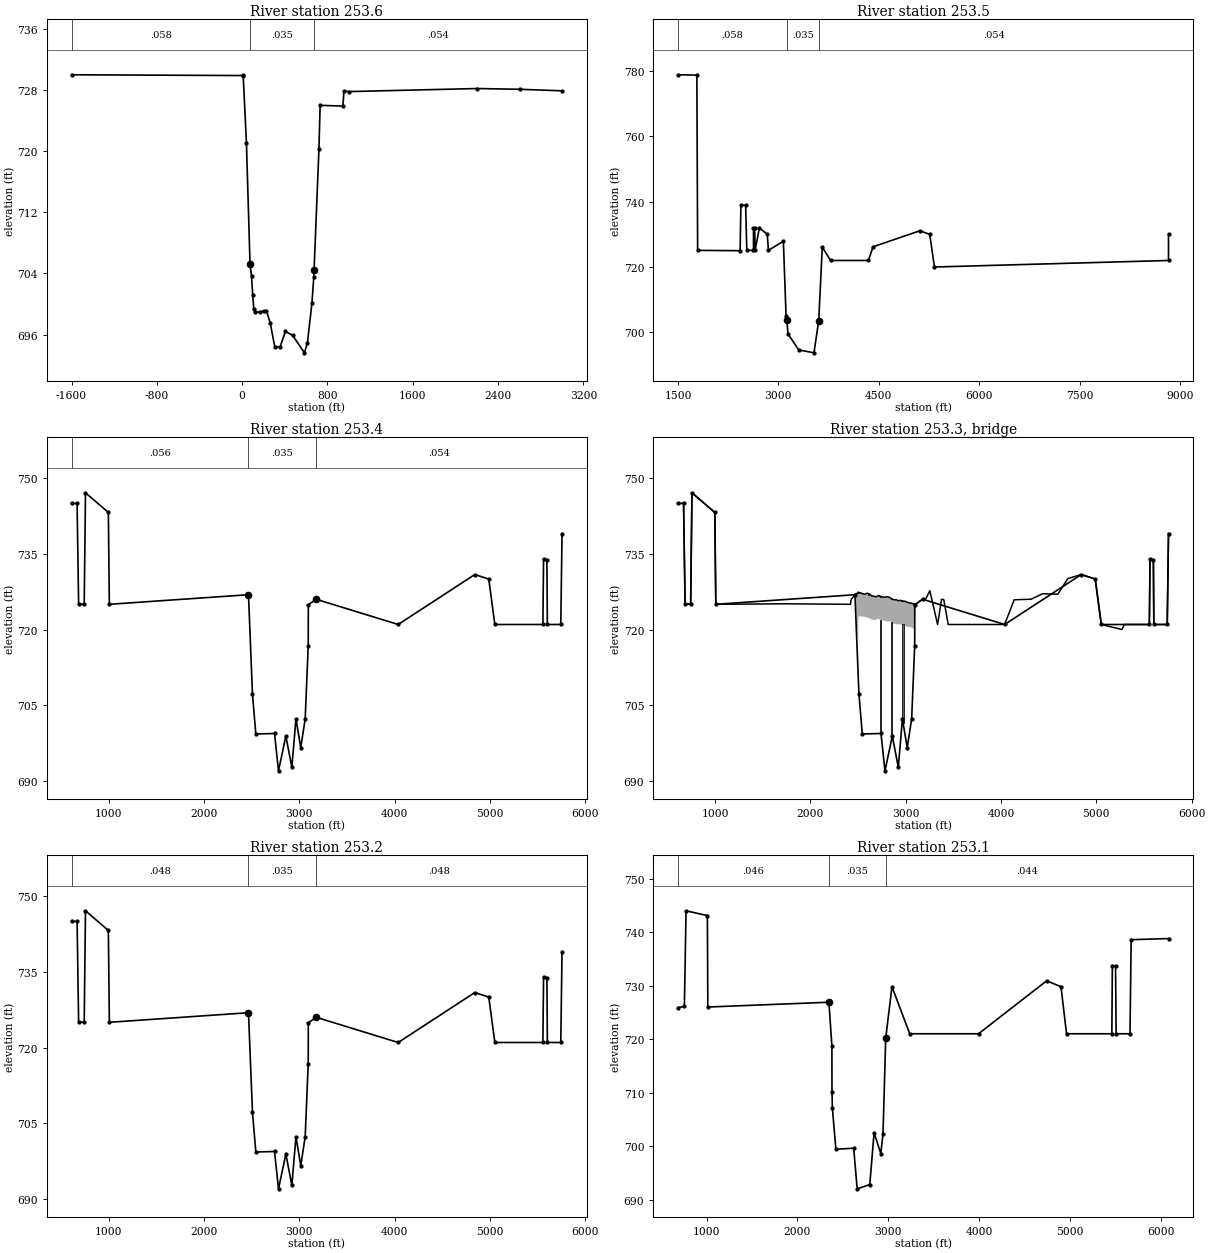
Type RM Length L Ch R = 1 ,253.6   ,610,610,610
#Sta/Elev= 30
   -1600     730     4.7   729.9     9.4     730      40   721.1    73.9   705.2
      88   703.6    98.9   701.2   108.4   699.4   123.3     699   163.4   698.9
   205.7   699.1   227.5   699.1   263.3   697.5   305.5   694.4   356.1   694.4
   405.6   696.4   472.6   695.9   584.2   693.6   611.7   694.9   654.2   700.1
   671.5   703.5   674.1   704.4     720   720.3     731     726   944.5   725.9
   954.6   727.9   999.2   727.8  2203.5   728.2  2602.4   728.1  2999.1   727.9
#Mann= 3 , 0 , 0
   -1600    .058       0    73.9    .035       0   674.1    .054       0
#Block Obstruct= 2 , 0
                            1000
Bank Sta=73.9,674.1
XS Rating Curve= 0 ,0
Exp/Cntr=0.3,0.1

Type RM Length L Ch R = 1 ,253.5   ,36.96,36.96,36.96
#Sta/Elev= 30
    1500   778.9  1782.1   778.8  1793.9   725.1  2428.7     725  2440.4     739
    2511   738.9  2528.6   725.1  2628.5   725.1  2628.5     732  2646.2     732
    2652   725.1  2716.7     732  2834.2     730  2851.9   725.1  3074.9   727.9
    3115     705  3126.2   703.8  3143.8   699.5  3303.8   694.6  3532.1   693.7
  3603.2   703.6  3656.4   726.1  3780.6     722  4344.8     722  4415.4   726.2
  5114.8   731.1  5261.8     730  5332.3     720  8829.5     722  8829.5     730
#Mann= 3 , 0 , 0
    1500    .058       0  3126.2    .035       0  3603.2    .054       0
#Block Obstruct= 2 , 0
                            3728
Bank Sta=3126.2,3603.2
XS Rating Curve= 0 ,0
Exp/Cntr=0.3,0.1

Type RM Length L Ch R = 1 ,253.4   ,24.5,24.5,24.5
BEGIN DESCRIPTION:
REPEATED section.  C & O Railroad Bridge - Upstream Section
END DESCRIPTION:
#Sta/Elev= 30
   610.1     745   668.8     745   684.7   725.1   743.3     725   756.9   747.1
   996.9   743.2  1007.1     725  2467.1   726.9  2508.8   707.2  2544.1   699.3
  2740.2   699.4  2782.1     692  2859.2   698.9    2922   692.7    2965   702.3
  3015.7   696.6  3061.9   702.3  3093.9   716.8    3095   724.9  3176.4     726
  4037.7     721  4841.8   730.9  4988.3     730  5051.9     721  5556.1     721
  5563.2     734  5598.3   733.8    5603     721  5743.7     721    5757     739
#Mann= 3 , 0 , 0
   610.1    .056       0  2467.1    .035       0  3176.4    .054       0
#Block Obstruct= 2 , 0
                            3716
Bank Sta=2467.1,3176.4
XS Rating Curve= 0 ,0
Exp/Cntr=0.3,0.1

Type RM Length L Ch R = 3 ,253.3   ,,,
BEGIN DESCRIPTION:
Structure #12 C & O Railroad Bridge
END DESCRIPTION:
Bridge Culvert--1,0,-1,-1, 0
Deck Dist Width WeirC Skew NumUp NumDn MinLoCord MaxHiCord MaxSubmerge Is_Ogee
1,23,2.6,0, 80, 80, 725, , 0.95, 0, 0,0,,
   610.1   668.8   684.7   743.3   756.9   996.9  1007.1  1728.2    2420    2426
  2467.1  2498.9    2500  2503.3  2506.6  2508.8  2525.3  2544.1  2568.3  2592.6
  2610.2  2612.4  2621.2  2622.3  2639.9  2687.3  2710.5    2727  2728.1  2739.1
  2740.2  2782.1  2798.6    2828  2849.3  2850.4  2858.1  2859.2  2873.5  2901.1
    2922  2945.1    2965  2967.2    2976  2977.1  2993.6  3015.7  3036.6  3061.9
  3080.7  3086.2    3093    3095    3095  3176.4  3211.6  3252.7  3334.2  3375.7
  3399.2  3445.6  4037.7  4137.9  4313.7  4436.9  4595.2    4701  4841.8  4988.3
  5051.9  5268.9  5292.4    5433  5556.1  5563.2  5598.3    5603  5743.7    5757
     745     745   725.1     725   747.1   743.2     725   725.1     725   725.9
   726.9   727.3   727.4   727.4   727.4   727.2   727.3   727.1     727   727.2
   727.1   726.8     727     727   726.7   726.5   726.7   726.6   726.7   726.4
   726.5   726.4   726.5   726.4   726.1   726.1   726.1     726   725.9   725.9
   725.7   725.8   725.6   725.7   725.6   725.6   725.6   725.4   725.3   725.2
   725.1     725     725     725   724.9     726   726.1   727.7     721     726
   725.9     721     721   725.9     726   727.1     727   730.1   730.9     730
     721     720     721     721     721     734   733.8     721     721     739
     745     745   725.1     725   747.1   743.2     725   725.1     725   725.9
   726.9     718     718   722.6   722.7   722.6   722.6   722.6   722.5   722.4
   722.2   722.4   722.2   722.2     722   721.9   722.2   721.9     722   721.9
   721.9   721.7   721.6   721.6   721.6   721.6   721.3     721   721.2     721
   721.1     721   720.9     721     721   720.9   720.7   720.5   720.5   720.4
   720.2   720.2     720   719.9   724.9     726   726.1   727.7   720.2     726
   725.9     721     721   725.9     726   727.1     727   730.1   730.9     730
     721     720     721     721     721     734   733.8     721     721     739
   610.1   668.8   684.7   743.3   756.9   996.9  1007.1  1728.2    2420    2426
  2467.1  2498.9    2500  2503.3  2506.6  2508.8  2525.3  2544.1  2568.3  2592.6
  2610.2  2612.4  2621.2  2622.3  2639.9  2687.3  2710.5    2727  2728.1  2739.1
  2740.2  2782.1  2798.6    2828  2849.3  2850.4  2858.1  2859.2  2873.5  2901.1
    2922  2945.1    2965  2967.2    2976  2977.1  2993.6  3015.7  3036.6  3061.9
  3080.7  3086.2    3093    3095    3095  3176.4  3211.6  3252.7  3334.2  3375.7
  3399.2  3445.6  4037.7  4137.9  4313.7  4436.9  4595.2    4701  4841.8  4988.3
  5051.9  5268.9  5292.4    5433  5556.1  5563.2  5598.3    5603  5743.7    5757
     745     745   725.1     725   747.1   743.2     725   725.1     725   725.9
   726.9   727.3   727.4   727.4   727.4   727.2   727.3   727.1     727   727.2
   727.1   726.8     727     727   726.7   726.5   726.7   726.6   726.7   726.4
   726.5   726.4   726.5   726.4   726.1   726.1   726.1     726   725.9   725.9
   725.7   725.8   725.6   725.7   725.6   725.6   725.6   725.4   725.3   725.2
   725.1     725     725     725   724.9     726   726.1   727.7     721     726
   725.9     721     721   725.9     726   727.1     727   730.1   730.9     730
     721     720     721     721     721     734   733.8     721     721     739
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Pier Skew, UpSta & Num, DnSta & Num=  ,2616.8, 2 ,2616.8, 2 , 0 , 0 , 0 ,,
    12.1     8.8
   700.7   722.4
    12.1     8.8
   700.7   722.4
Pier Skew, UpSta & Num, DnSta & Num=  ,2732.6, 2 ,2732.6, 2 , 0 , 0 , 0 ,,
    13.2      11
   699.1     722
    13.2      11
   699.1     722
Pier Skew, UpSta & Num, DnSta & Num=  ,2854.3, 2 ,2854.3, 2 , 0 , 0 , 0 ,,
     9.9     7.7
   698.8   721.6
     9.9     7.7
   698.8   721.6
Pier Skew, UpSta & Num, DnSta & Num=  ,2971.6, 2 ,2971.6, 2 , 0 , 0 , 0 ,,
    12.1     8.8
   702.1     721
    12.1     8.8
   702.1     721
BR Coef=-1 , 0 , 0 ,, 0 ,,,0.8,-1,,0,
WSPro=,,,, 1 ,,,, 0 ,,,, 0 ,,,,-1 ,-1 ,-1 , 0 , 0 , 0 , 0 , 0
BC Design=,, 0 ,, 0 ,,,,,,
BC HTab HWMax=747.1
BC Use User HTab Curves=0
BC User HTab FreeFlow(D)= 0

Type RM Length L Ch R = 1 ,253.2   ,52,52,52
BEGIN DESCRIPTION:
C & O Railroad Bridge - Downstream Section
END DESCRIPTION:
#Sta/Elev= 30
   610.1     745   668.8     745   684.7   725.1   743.3     725   756.9   747.1
   996.9   743.2  1007.1     725  2467.1   726.9  2508.8   707.2  2544.1   699.3
  2740.2   699.4  2782.1     692  2859.2   698.9    2922   692.7    2965   702.3
  3015.7   696.6  3061.9   702.3  3093.9   716.8    3095   724.9  3176.4     726
  4037.7     721  4841.8   730.9  4988.3     730  5051.9     721  5556.1     721
  5563.2     734  5598.3   733.8    5603     721  5743.7     721    5757     739
#Mann= 3 , 0 , 0
   610.1    .048       0  2467.1    .035       0  3176.4    .048       0
#Block Obstruct= 2 , 0
                            3170
Bank Sta=2467.1,3176.4
XS Rating Curve= 0 ,0
Exp/Cntr=0.3,0.1

Type RM Length L Ch R = 1 ,253.1   ,903.42,903.42,903.42
#Sta/Elev= 30
   683.9   725.9   754.5   726.1     773     744  1007.5   743.1  1012.8     726
  2346.2   726.9  2378.9   718.7  2379.9   710.1  2384.3   707.1  2422.7   699.4
  2618.8   699.6  2657.3     692  2796.1   692.8  2843.6   702.5  2917.4   698.6
  2941.7   702.3  2971.7   720.2  3040.2   729.8  3236.2     721  3993.7     721
  4743.7   730.9  4901.8   729.8  4962.7     721  5461.8     721  5467.1   733.7
  5502.3   733.7  5508.9     721  5661.5     721  5674.5   738.6  6085.6   738.8
#Mann= 3 , 0 , 0
   683.9    .046       0  2346.2    .035       0  2971.7    .044       0
#Block Obstruct= 2 , 0
                            3075
Bank Sta=2346.2,2971.7
XS Rating Curve= 0 ,0
Exp/Cntr=0.3,0.1