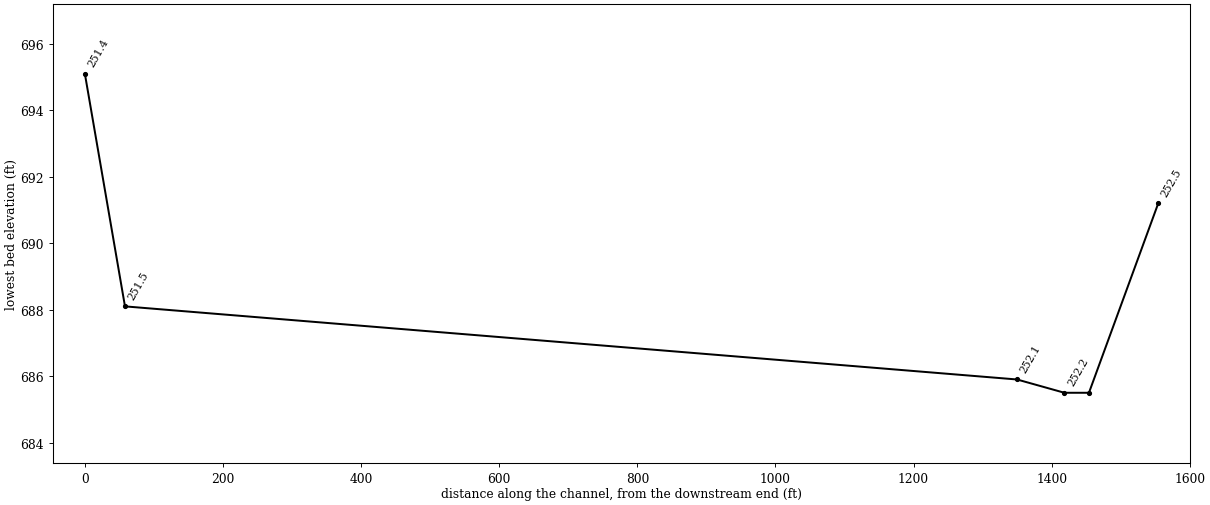
HEC-RAS study FRA-70-1321R.prj: FRA-70-1321R

--- FRA-70-1321R.g02 (geometry) --- (continued)

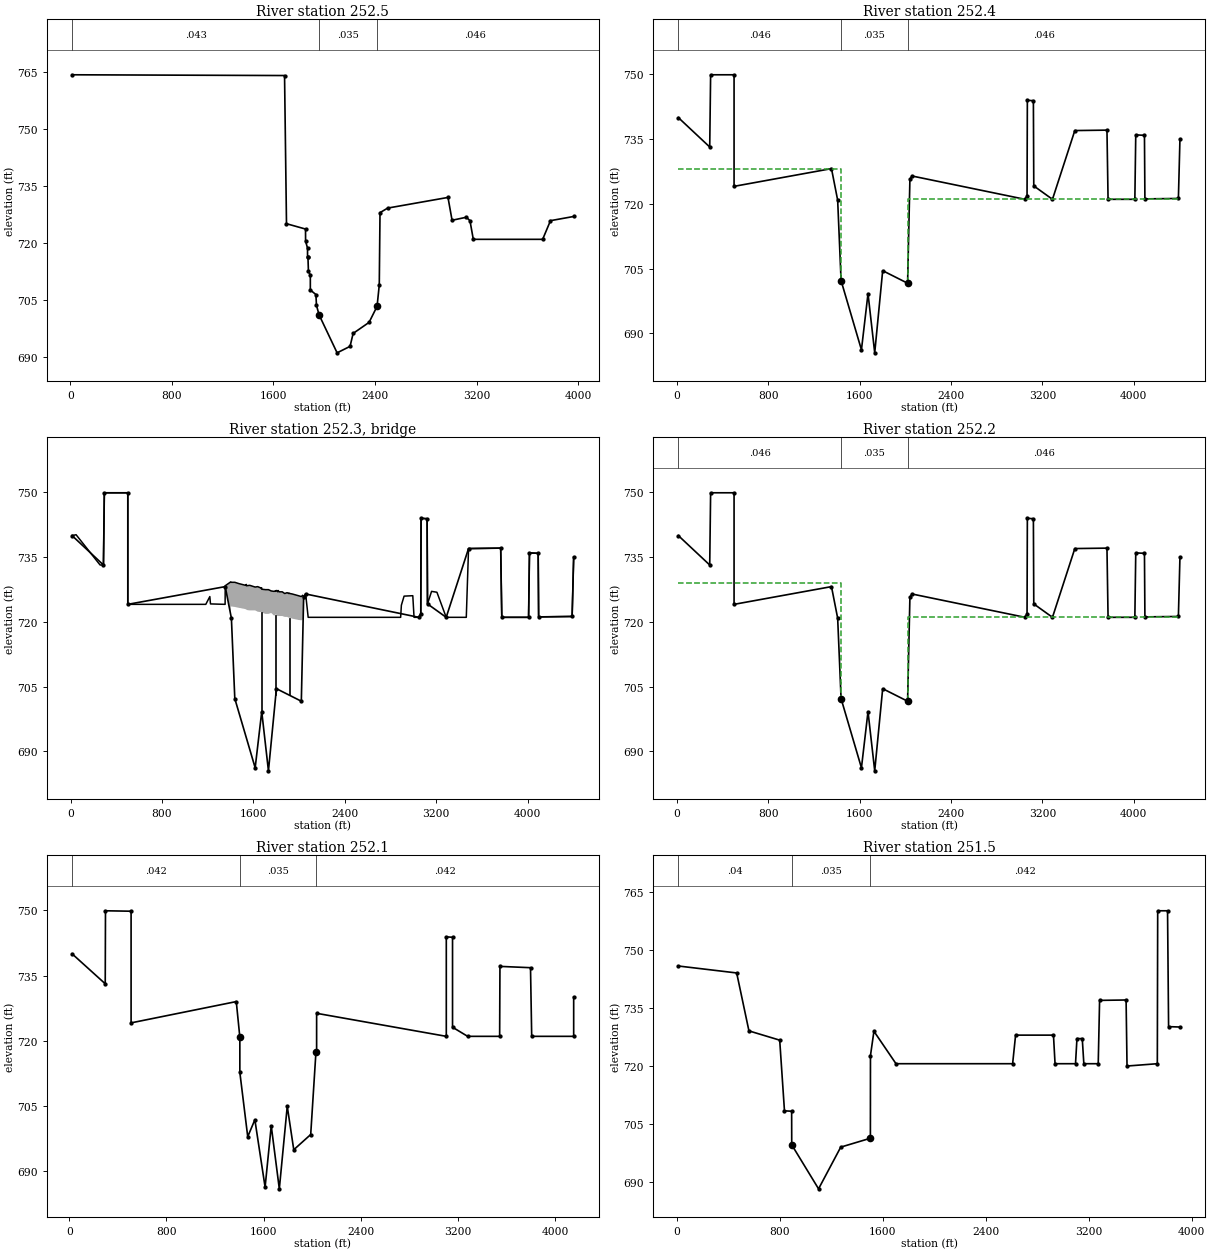
Type RM Length L Ch R = 1 ,252.5   ,100.32,100.32,100.32
BEGIN DESCRIPTION:
AK
From 12-05-3607P LOMR
END DESCRIPTION:
#Sta/Elev= 30
    13.9   764.2  1687.8     764  1703.1   725.1    1853   723.7  1853.5   720.5
  1868.8   718.7    1869   716.4  1872.1   716.4  1875.9   712.6  1890.9   711.6
  1890.9   707.7  1934.9   706.5  1939.2   703.7  1959.4   701.2  2101.8   691.2
  2203.8   692.9  2228.1   696.3  2353.7   699.2  2416.6   703.4    2434     709
  2439.8     728    2500   729.2  2975.3     732  3007.5     726  3119.5   726.8
  3148.4   725.9  3174.7     721    3721     721  3782.7   725.9  3965.4     727
#Mann= 3 , 0 , 0
    13.9    .043       0  1959.4    .035       0  2416.6    .046       0
#Block Obstruct= 2 , 0
                            2646
Bank Sta=1959.4,2416.6
XS Rating Curve= 0 ,0
Exp/Cntr=0.3,0.1

Type RM Length L Ch R = 1 ,252.4   ,35.5,35.5,35.5
BEGIN DESCRIPTION:
REPEATED section. Penn Central Railroad Bridge Crossing #2 - Upstream Section
From 12-05-3607P LOMR
END DESCRIPTION:
#Sta/Elev= 30
    13.4   739.9   288.1   733.1     296   749.8   501.2   749.8   501.2     724
  1353.9   728.1    1408   720.8  1437.9   702.2  1616.1   686.2  1673.6   699.2
  1732.3   685.5    1802   704.5  2020.1   701.6  2040.3   725.6  2057.8   726.4
  3047.7     721  3065.6   721.8  3068.3   743.9  3121.1   743.8  3124.5   724.1
  3288.1     721  3483.7   736.9  3765.1     737  3774.7     721  4009.2     721
  4017.1   735.9  4093.3   735.8  4097.2   721.1  4390.3   721.2  4403.9   734.9
#Mann= 3 , 0 , 0
    13.4    .046       0  1437.9    .035       0  2020.1    .046       0
#XS Ineff= 2 , 0
          1437.9     728  2020.1             721
Permanent Ineff=
       F       F
#Block Obstruct= 2 , 0
                            2687
Bank Sta=1437.9,2020.1
XS Rating Curve= 0 ,0
Exp/Cntr=0.3,0.1

Type RM Length L Ch R = 3 ,252.3   ,,,
BEGIN DESCRIPTION:
Structure #11 Penn Central Railroad Bridge, Crossing #2
END DESCRIPTION:
Bridge Culvert--1,0,-1,-1, 0
Deck Dist Width WeirC Skew NumUp NumDn MinLoCord MaxHiCord MaxSubmerge Is_Ogee
1,34,2.6,0, 79, 79, 725, , 0.95, 0, 0,0,,
    13.4    48.6   258.8   288.1     296   501.2   501.2  1183.9  1219.3    1225
    1353  1353.9  1402.5  1402.5    1408  1410.2  1437.9  1473.3    1532  1534.2
  1538.6  1539.7  1568.5  1616.1  1638.2  1664.8    1667  1673.6  1673.6  1706.8
  1732.3  1756.6    1781    1791  1793.2  1799.8    1802  1814.2  1816.4  1826.4
    1853  1875.1    1895  1911.6  1913.8  1920.5    1921  1940.4  1994.6  2020.1
  2032.3  2038.9  2040.3  2057.8    2080    2098  2889.5  2895.8  2919.5  2995.7
  3006.7  3047.7  3065.6  3068.3  3121.1  3124.5    3160  3206.9  3288.1    3464
  3483.7  3765.1  3774.7  4009.2  4017.1  4093.3  4097.2  4390.3  4403.9
   739.9   740.1   733.1   733.1   749.8   749.8     724     724   725.8   724.1
     724   728.3   729.2   729.2   729.1   729.1   729.1   728.8   728.4   728.5
   728.6   728.3   728.4     728   728.1   727.8   727.7   727.8   727.5   727.4
   727.4   727.1     727   727.1     727   727.2   727.2   726.9   727.2   726.9
   726.9   726.5   726.7   726.5   726.6   726.5   726.5   726.4     726   725.8
   726.1   725.8   725.6   726.4     721     721     721   723.8   725.9     726
     721     721   721.8   743.9   743.8   724.1     727   726.8     721     721
   736.9     737     721     721   735.9   735.8   721.1   721.2   734.9
   739.9   740.1   733.1   733.1   749.8   749.8     724     724   725.8   724.1
     724   728.1     720   723.5   723.5   723.5   723.4   723.2   722.9   722.8
   722.9   722.7   722.6   722.6   722.3   722.2   722.3   722.2   722.1   721.8
   721.8     722   721.4   721.5   721.6   721.7   721.4   721.3   721.3   721.3
   721.3   721.1   721.1   720.9   720.9   720.9   720.9   720.7   720.4   720.3
   720.5   720.3   725.6   726.4     721     721     721   723.8   725.9     726
     721     721   721.8   743.9   743.8   724.1     727   726.8     721     721
   736.9     737     721     721   735.9   735.8   721.1   721.2   734.9
    13.4    48.6   258.8   288.1     296   501.2   501.2  1183.9  1219.3    1225
    1353  1353.9  1402.5  1402.5    1408  1410.2  1437.9  1473.3    1532  1534.2
  1538.6  1539.7  1568.5  1616.1  1638.2  1664.8    1667  1673.6  1673.6  1706.8
  1732.3  1756.6    1781    1791  1793.2  1799.8    1802  1814.2  1816.4  1826.4
    1853  1875.1    1895  1911.6  1913.8  1920.5    1921  1940.4  1994.6  2020.1
  2032.3  2038.9  2040.3  2057.8    2080    2098  2889.5  2895.8  2919.5  2995.7
  3006.7  3047.7  3065.6  3068.3  3121.1  3124.5    3160  3206.9  3288.1    3464
  3483.7  3765.1  3774.7  4009.2  4017.1  4093.3  4097.2  4390.3  4403.9
   739.9   740.1   733.1   733.1   749.8   749.8     724     724   725.8   724.1
     724   728.3   729.2   729.2   729.1   729.1   729.1   728.8   728.4   728.5
   728.6   728.3   728.4     728   728.1   727.8   727.7   727.8   727.5   727.4
   727.4   727.1     727   727.1     727   727.2   727.2   726.9   727.2   726.9
   726.9   726.5   726.7   726.5   726.6   726.5   726.5   726.4     726   725.8
   726.1   725.8   725.6   726.4     721     721     721   723.8   725.9     726
     721     721   721.8   743.9   743.8   724.1     727   726.8     721     721
   736.9     737     721     721   735.9   735.8   721.1   721.2   734.9
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Pier Skew, UpSta & Num, DnSta & Num=  ,1536.4, 2 ,1536.4, 2 , 0 , 0 , 0 ,,
     7.7     4.4
   699.3   722.9
     7.7     4.4
   699.3   722.9
Pier Skew, UpSta & Num, DnSta & Num=  ,1670.3, 2 ,1670.3, 2 , 0 , 0 , 0 ,,
     8.8     6.6
   699.1   722.3
     8.8     6.6
   699.1   722.3
Pier Skew, UpSta & Num, DnSta & Num=  ,1796.5, 2 ,1796.5, 2 , 0 , 0 , 0 ,,
      11     6.6
   703.8   721.7
      11     6.6
   703.8   721.7
Pier Skew, UpSta & Num, DnSta & Num=  ,1917.2, 2 ,1917.2, 2 , 0 , 0 , 0 ,,
     9.5     6.7
   695.9   720.9
     9.5     6.7
   695.9   720.9
BR Coef=-1 , 0 , 0 ,, 0 ,,,0.8,-1,,0,
WSPro=,,,, 1 ,,,, 0 ,,,, 0 ,,,,-1 ,-1 ,-1 , 0 , 0 , 0 , 0 , 0
BC Design=,, 0 ,, 0 ,,,,,,
BC HTab HWMax=749.8
BC Use User HTab Curves=0
BC User HTab FreeFlow(D)= 0

Type RM Length L Ch R = 1 ,252.2   ,68.64,68.64,68.64
BEGIN DESCRIPTION:
Penn Central Railroad Bridge Crossing #2 - Downstream Section
From 12-05-3607P LOMR
END DESCRIPTION:
#Sta/Elev= 30
    13.4   739.9   288.1   733.1     296   749.8   501.2   749.8   501.2     724
  1353.9   728.1    1408   720.8  1437.9   702.2  1616.1   686.2  1673.6   699.2
  1732.3   685.5    1802   704.5  2020.1   701.6  2040.3   725.6  2057.8   726.4
  3047.7     721  3065.6   721.8  3068.3   743.9  3121.1   743.8  3124.5   724.1
  3288.1     721  3483.7   736.9  3765.1     737  3774.7     721  4009.2     721
  4017.1   735.9  4093.3   735.8  4097.2   721.1  4390.3   721.2  4403.9   734.9
#Mann= 3 , 0 , 0
    13.4    .046       0  1437.9    .035       0  2020.1    .046       0
#XS Ineff= 2 , 0
          1437.9     729  2020.1             721
Permanent Ineff=
       F       F
#Block Obstruct= 2 , 0
                            2189
Bank Sta=1437.9,2020.1
XS Rating Curve= 0 ,0
Exp/Cntr=0.3,0.1

Type RM Length L Ch R = 1 ,252.1   ,1291.67,1291.67,1291.67
BEGIN DESCRIPTION:
From 12-05-3607P LOMR
END DESCRIPTION:
#Sta/Elev= 30
    23.4     740   296.5   733.1   298.6   749.9   509.4   749.8   509.4   724.1
  1375.4     729  1404.8   720.8  1404.8   712.7  1469.7   697.9  1528.5   701.8
  1612.7   686.3  1663.3   700.4  1729.8   685.9  1795.1   704.9  1848.7   694.9
  1988.2   698.4  2031.4   717.4  2036.9   717.5    2037   726.3  3104.6     721
  3104.6   743.9  3155.9   743.8  3155.9   723.1  3280.3     721  3543.8     721
  3546.3   737.1  3797.9   736.8  3807.7     721  4153.3     721  4153.3     730
#Mann= 3 , 0 , 0
    23.4    .042       0  1404.8    .035       0  2031.4    .042       0
#Block Obstruct= 2 , 0
                            2151
Bank Sta=1404.8,2031.4
XS Rating Curve= 0 ,0
Exp/Cntr=0.3,0.1

Type RM Length L Ch R = 1 ,251.5   ,58.09,58.09,58.09
BEGIN DESCRIPTION:
AJ
From 12-05-3607P LOMR
END DESCRIPTION:
#Sta/Elev= 30
    13.5   745.8   466.6     744   561.8     729   800.7   726.6   837.7   708.3
   893.4   708.2   894.1   699.5  1102.4   688.1  1274.6   698.9  1504.9   701.2
  1505.5   722.6  1532.4   728.9  1703.7   720.5  2609.5   720.5  2632.5   727.9
  2926.6   727.9  2938.9   720.5  3097.8   720.5    3109     727  3150.2     727
  3162.5   720.5  3274.2   720.5  3284.8   736.9  3490.6     737  3497.8   719.9
  3733.1   720.5    3736   760.1  3812.5   760.1  3820.6   730.1  3908.8     730
#Mann= 3 , 0 , 0
    13.5     .04       0   894.1    .035       0  1504.9    .042       0
#Block Obstruct= 2 , 0
                            1521
Bank Sta=894.1,1504.9
XS Rating Curve= 0 ,0
Exp/Cntr=0.3,0.1

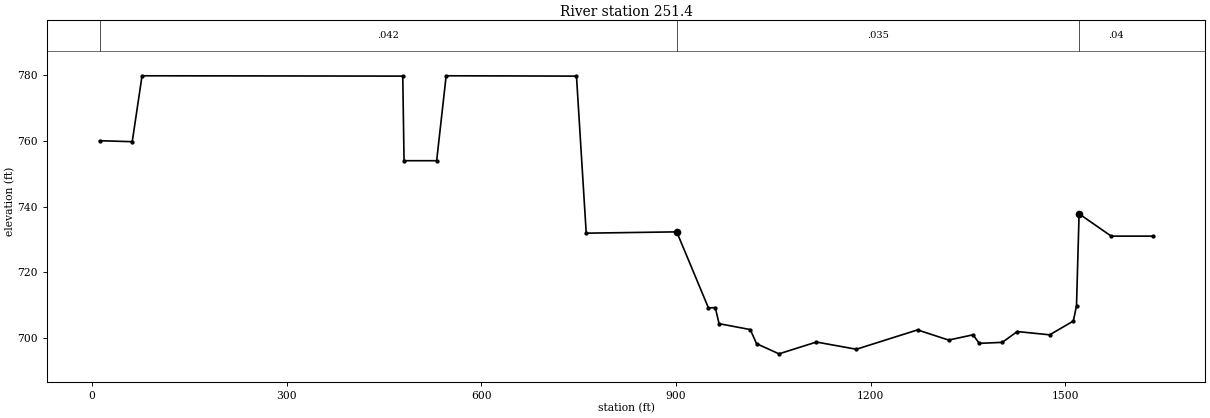
Type RM Length L Ch R = 1 ,251.4   ,87.5,87.5,87.5
BEGIN DESCRIPTION:
REPEATED section. Broad Street / US 40 Arch Bridge - Upstream Section
From 12-05-3607P LOMR
END DESCRIPTION:
#Sta/Elev= 30
    11.7   760.1  61.955   759.8   77.06   779.9 478.815   779.8  480.81     754
 531.065     754 545.695   779.9 746.525   779.8 761.535   731.9 900.995   732.3
  949.92   709.1 960.465   709.2  966.26   704.3 1014.33   702.5 1024.02   698.2
  1058.6   695.11116.265   698.71177.825   696.51272.065   702.4 1320.04   699.3
1357.565   700.91367.255   698.3 1402.69   698.61425.775   701.91475.745   700.9
1512.225   705.1 1517.07   709.8 1521.06   737.81570.555     7311634.585     731
#Mann= 3 , 0 , 0
    11.7    .042       0 900.995    .035       0 1521.06     .04       0
#XS Ineff= 2 , 0
         900.995     732 1521.06             731
Permanent Ineff=
       F       F
#Block Obstruct= 2 , 0
                            1720
Bank Sta=900.995,1521.06
XS Rating Curve= 0 ,0
Exp/Cntr=0.5,0.3