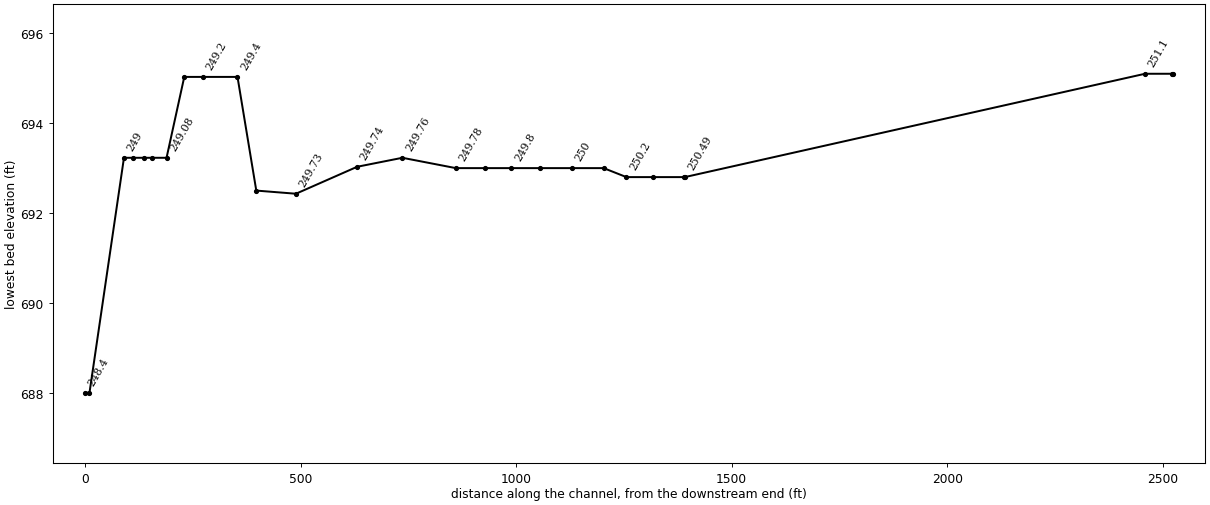
HEC-RAS study FRA-70-1321R.prj: FRA-70-1321R

--- FRA-70-1321R.g02 (geometry) --- (continued)

Type RM Length L Ch R = 3 ,251.3   ,,,
BEGIN DESCRIPTION:
Structure #10 West Broad Street / US 40 Arch Bridge
END DESCRIPTION:
Bridge Culvert--1,0,-1,-1, 0
Deck Dist Width WeirC Skew NumUp NumDn MinLoCord MaxHiCord MaxSubmerge Is_Ogee
1,86,3.1,0, 67, 67, 731, , 0.95, 0, 0,0,,
    11.7  61.955   77.06 478.815  480.81 531.065 545.695 746.525 761.535 794.975
 900.995  949.92 960.465  964.36  966.26983.54991004.735 1014.33 1015.281022.975
 1024.021033.615  1058.61081.685 1094.13 1094.13 1103.82 1103.821116.265  1138.4
 1168.231177.8251179.915 1185.52 1187.42 1199.01 1230.74 1264.371272.0651272.065
 1280.711281.7551292.205 1320.041345.9751357.565 1358.61 1366.211367.2551379.605
 1402.691425.775 1431.57 1434.611443.0651445.155 1452.661475.7451498.7351509.375
1512.225 1517.07 1521.061570.5551587.275 1598.771634.585
   760.1   759.8   779.9   779.8     754     754   779.9   779.8     732     732
   732.3   736.2   736.3   736.4   736.5   736.9   737.1   737.5   737.5   737.3
   737.8   737.8     738   738.5   738.8   739.1   738.8   739.1   739.4   739.6
   740.2   740.6   740.8   740.4   740.4   740.8   741.5   741.1     741   741.1
   740.9     741   740.7   740.3   740.1     740     740   739.8   739.8   739.8
   739.3     739   739.2   739.2   738.8   738.7     739   738.3   738.2   738.2
   738.2   738.1   737.8     731     731     731     731
   760.1   759.8   779.9   779.8     754     754   779.9   779.8     732     732
   732.3   709.1   709.2   717.2   721.1   726.9   718.2   712.3   712.2   712.2
   712.2   718.3   728.3     719   708.5   708.5   708.5   708.5   718.9     730
   719.9   711.1   708.9   708.9   708.9   719.8   731.8     720   709.3   709.3
   709.3   709.3   720.2     731   720.6   708.7   708.2   708.2   708.2   719.8
   729.7   720.1   709.7   709.7   709.7   709.7   720.1   728.9   720.1   713.7
     705   709.8   737.8     731     731     731     731
    11.7  61.955   77.06 478.815  480.81 531.065 545.695 746.525 761.535 794.975
 900.995  949.92 960.465  964.36  966.26983.54991004.735 1014.33 1015.281022.975
 1024.021033.615  1058.61081.685 1094.13 1094.13 1103.82 1103.821116.265  1138.4
 1168.231177.8251179.915 1185.52 1187.42 1199.01 1230.74 1264.371272.0651272.065
 1280.711281.7551292.205 1320.041345.9751357.565 1358.61 1366.211367.2551379.605
 1402.691425.775 1431.57 1434.611443.0651445.155 1452.661475.7451498.7351509.375
1512.225 1517.07 1521.061570.5551587.275 1598.771634.585
   760.1   759.8   779.9   779.8     754     754   779.9   779.8     732     732
   732.3   736.2   736.3   736.4   736.5   736.9   737.1   737.5   737.5   737.3
   737.8   737.8     738   738.5   738.8   739.1   738.8   739.1   739.4   739.6
   740.2   740.6   740.8   740.4   740.4   740.8   741.5   741.1     741   741.1
   740.9     741   740.7   740.3   740.1     740     740   739.8   739.8   739.8
   739.3     739   739.2   739.2   738.8   738.7     739   738.3   738.2   738.2
   738.2   738.1   737.8     731     731     731     731
   760.1   759.8   779.9   779.8     754     754   779.9   779.8     732     732
   732.3   709.1   709.2   717.2   721.1   726.9   718.2   712.2   712.2   712.2
   712.2   718.3   728.3     719   708.5   708.5   708.5   708.5   718.9     730
   719.9   711.1   708.9   708.9   708.9   719.8   731.8     720   709.3   709.3
   709.3   709.3   720.2     731   720.6   708.7   708.2   708.2   708.2   719.8
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Pier Skew, UpSta & Num, DnSta & Num=  ,1019.1, 2 ,1019.1, 2 , 0 , 0 , 0 ,,
     9.7     7.7
   698.2   712.2
     9.7     7.7
   698.2   712.2
Pier Skew, UpSta & Num, DnSta & Num=  ,1099, 2 ,1099, 2 , 0 , 0 , 0 ,,
     9.7     9.7
   698.2   708.5
     9.7     9.7
   698.2   708.5
Pier Skew, UpSta & Num, DnSta & Num=  ,1182.7, 2 ,1182.7, 2 , 0 , 0 , 0 ,,
     9.6     5.6
   696.5   708.9
     9.6     5.6
   696.5   708.9
Pier Skew, UpSta & Num, DnSta & Num=  ,1276.4, 2 ,1276.4, 2 , 0 , 0 , 0 ,,
     9.7     8.7
   702.4   709.3
     9.7     8.7
   702.4   709.3
Pier Skew, UpSta & Num, DnSta & Num=  ,1361.4, 2 ,1361.4, 2 , 0 , 0 , 0 ,,
     9.7     7.6
   698.3   708.2
     9.7     7.6
   698.3   708.2
Pier Skew, UpSta & Num, DnSta & Num=  ,1438.8, 2 ,1438.8, 2 , 0 , 0 , 0 ,,
    13.5     8.5
   701.8   709.7
    13.5     8.5
   701.8   709.7
BR Coef= 1 , 0 ,-1 ,0.9, 0 ,,,0.7980869,-1,,0,731.5
WSPro=,,,, 1 ,,,, 0 ,,,, 0 ,,,,-1 ,-1 ,-1 , 0 , 0 , 0 , 0 , 0
BR D #Sta/Elev= 55
    11.7   760.1  61.955   759.8   77.06   779.9 478.815   779.8  480.81     754
 531.065     754 545.695   779.9 746.525   779.8 761.535   731.9 794.975     732
 900.995   732.3  949.92   709.1 960.465   709.2  964.36     706  966.26   704.3
983.5499   702.61004.735   702.5 1014.33   702.5 1024.02   698.21033.615   697.3
  1058.6   695.11081.685   697.3 1094.13   698.2 1103.82   698.51116.265   698.7
  1138.4   698.7 1168.23   697.21177.825   696.5 1187.42   698.3 1199.01   698.9
 1230.74   700.5 1264.37   702.21272.065   702.41281.755   702.41292.205   701.9
 1320.04   699.31345.975   700.91357.565   700.91367.255   698.31379.605   698.7
 1402.69   698.61425.775   701.9 1431.57     7021445.155   701.8 1452.66   701.7
1475.745   700.91498.735   703.91509.375   704.61512.225   705.1 1517.07   709.8
 1521.06   737.81570.555     7311587.275     731 1598.77     7311634.585     731
BR D #Mann= 3
    11.7    .042 900.995    .035 1521.06     .04
BR D Banks=900.995,1521.06
BC Design=,, 0 ,, 0 ,,,,,,
BC HTab HWMax=779.9
BC Use User HTab Curves=0
BC User HTab FreeFlow(D)= 0

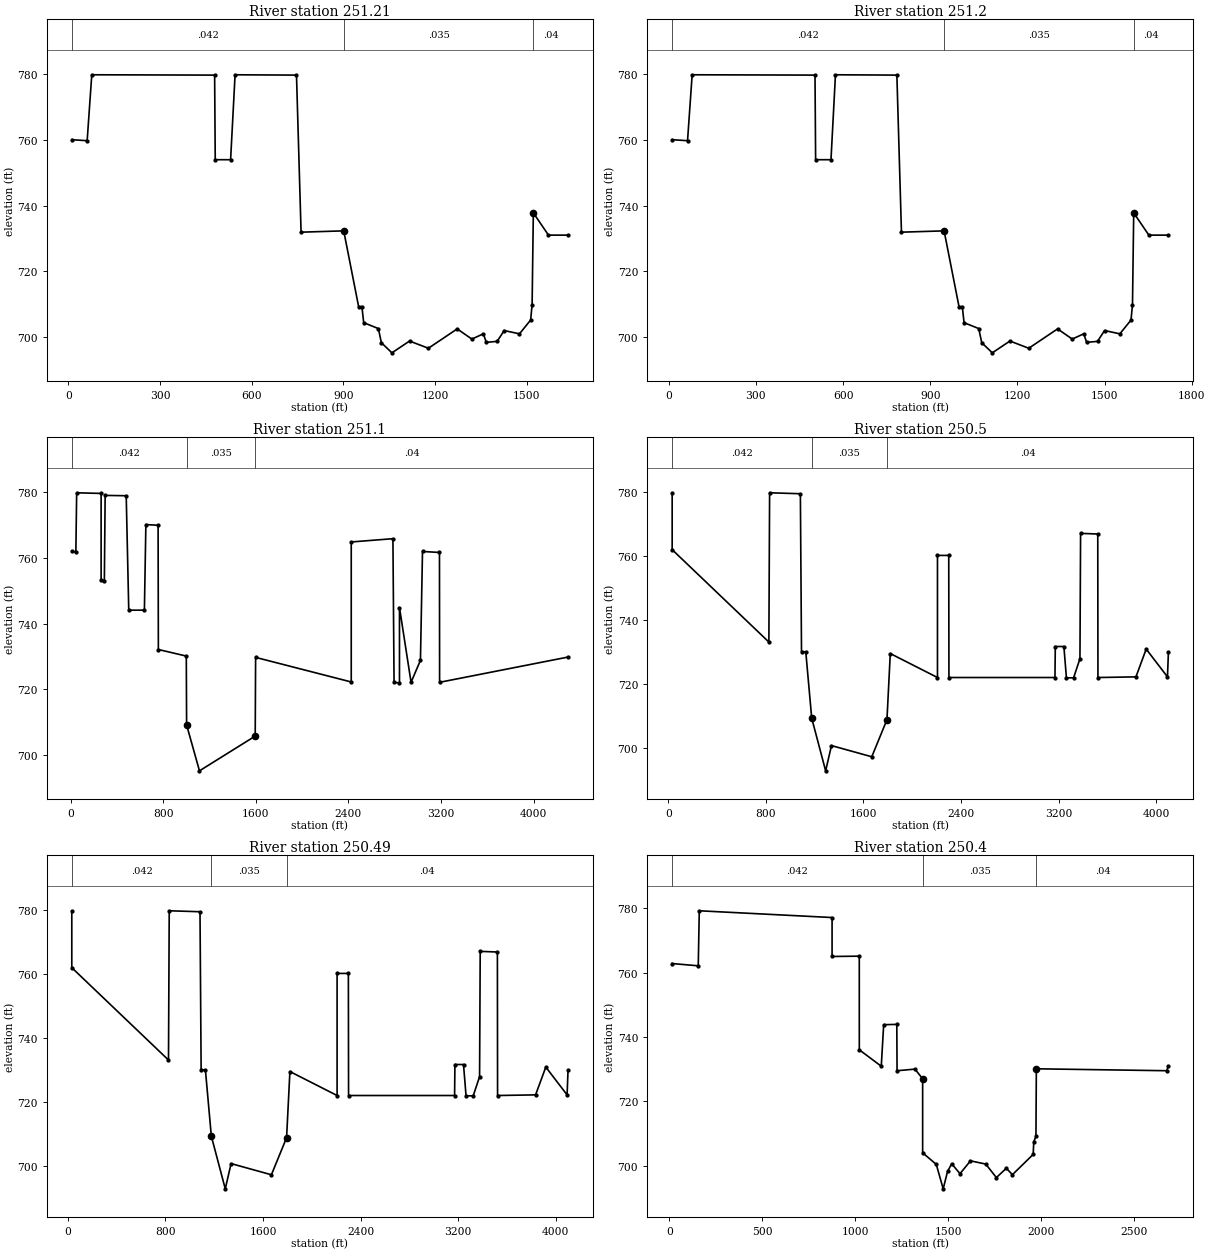
Type RM Length L Ch R = 1 ,251.21  ,1,1,1
BEGIN DESCRIPTION:
Broad Street / US 40 Arch Bridge - Downstream Section
From 12-05-3607P LOMR
END DESCRIPTION:
#Sta/Elev= 30
    11.7   760.1  61.955   759.8   77.06   779.9 478.815   779.8  480.81     754
 531.065     754 545.695   779.9 746.525   779.8 761.535   731.9 900.995   732.3
  949.92   709.1 960.465   709.2  966.26   704.3 1014.33   702.5 1024.02   698.2
  1058.6   695.11116.265   698.71177.825   696.51272.065   702.4 1320.04   699.3
1357.565   700.91367.255   698.3 1402.69   698.61425.775   701.91475.745   700.9
1512.225   705.1 1517.07   709.8 1521.06   737.81570.555     7311634.585     731
#Mann= 3 , 0 , 0
    11.7    .042       0 900.995    .035       0 1521.06     .04       0
#XS Ineff= 2 , 0
         900.995     732 1521.06             731
Permanent Ineff=
       F       F
#Block Obstruct= 2 , 0
                            1720
Bank Sta=900.995,1521.06
XS Rating Curve= 0 ,0
Exp/Cntr=0.5,0.3

Type RM Length L Ch R = 1 ,251.2   ,63.37,63.37,63.37
BEGIN DESCRIPTION:
From 12-05-3607P LOMR
END DESCRIPTION:
#Sta/Elev= 30
    11.7   760.1    64.6   759.8    80.5   779.9   503.4   779.8   505.5     754
   558.4     754   573.8   779.9   785.2   779.8     801   731.9   947.8   732.3
   999.3   709.1  1010.4   709.2  1016.5   704.3  1067.1   702.5  1077.3   698.2
  1113.7   695.1  1174.4   698.7  1239.2   696.5  1338.4   702.4  1388.9   699.3
  1428.4   700.9  1438.6   698.3  1475.9   698.6  1500.2   701.9  1552.8   700.9
  1591.2   705.1  1596.3   709.8  1600.5   737.8  1652.6     731    1720     731
#Mann= 3 , 0 , 0
    11.7    .042       0   947.8    .035       0  1600.5     .04       0
#XS Ineff= 2 , 0
           947.8     732  1600.5             731
Permanent Ineff=
       F       F
#Block Obstruct= 2 , 0
                            1720
Bank Sta=947.8,1600.5
XS Rating Curve= 0 ,0
Exp/Cntr=0.5,0.3

Type RM Length L Ch R = 1 ,251.1   ,1067.79,1067.79,1067.79
BEGIN DESCRIPTION:
From 12-05-3607P LOMR
END DESCRIPTION:
#Sta/Elev= 30
    10.3     762    45.5   761.9    52.4   779.9   263.7   779.7   263.7   753.3
   291.6     753   298.5   779.1   480.5     779   502.5   744.1   637.6   744.1
   650.4   770.2     756     770   758.3   732.1   999.6   730.1  1002.3   709.1
  1113.4   695.1  1595.1   705.7  1598.5   729.7  2424.8   722.2  2424.8   764.9
  2784.9   765.9  2794.7   722.1  2841.6   721.9  2841.6   744.9  2941.6   722.1
  3022.7   728.8  3040.5     762  3187.1   761.7  3188.2   722.1    4298   729.8
#Mann= 3 , 0 , 0
    10.3    .042       0  1002.3    .035       0  1595.1     .04       0
#Block Obstruct= 2 , 0
                            1653
Bank Sta=1002.3,1595.1
XS Rating Curve= 0 ,0
Exp/Cntr=0.5,0.3

Type RM Length L Ch R = 1 ,250.5   ,1,1,1
BEGIN DESCRIPTION:
AI
From 12-05-3607P LOMR
END DESCRIPTION:
#Sta/Elev= 30
    32.2   779.7    32.2     762   824.9   733.1   830.9   779.8  1083.1   779.5
  1092.4   730.1  1127.5     730  1175.9   709.3  1290.2   692.8    1338   700.7
  1668.4   697.2  1792.8   708.8  1820.1   729.5  2206.9     722  2206.9   760.2
  2299.3   760.2  2300.9     722    3170     722  3172.7   731.7  3243.1   731.7
  3263.9   721.9  3322.6   721.9  3374.8   727.9    3380   767.1  3520.8   766.9
  3522.3     722  3833.8   722.2  3917.7   730.9  4092.2   722.2    4100     730
#Mann= 3 , 0 , 0
    32.2    .042       0  1175.9    .035       0  1792.8     .04       0
#Block Obstruct= 2 , 0
                            1940
Bank Sta=1175.9,1792.8
XS Rating Curve= 0 ,0
Exp/Cntr=0.5,0.3

Type RM Length L Ch R = 1 ,250.49  ,72.92,72.92,72.92
BEGIN DESCRIPTION:
B&N added section
From 12-05-3607P LOMR
END DESCRIPTION:
#Sta/Elev= 30
    32.2   779.7    32.2     762   824.9   733.1   830.9   779.8  1083.1   779.5
  1092.4   730.1  1127.5     730  1175.9   709.3  1290.2   692.8    1338   700.7
  1668.4   697.2  1792.8   708.8  1820.1   729.5  2206.9     722  2206.9   760.2
  2299.3   760.2  2300.9     722    3170     722  3172.7   731.7  3243.1   731.7
  3263.9   721.9  3322.6   721.9  3374.8   727.9    3380   767.1  3520.8   766.9
  3522.3     722  3833.8   722.2  3917.7   730.9  4092.2   722.2    4100     730
#Mann= 3 , 0 , 0
    32.2    .042       0  1175.9    .035       0  1792.8     .04       0
#Block Obstruct= 2 , 0
       0                    1940       0
Bank Sta=1175.9,1792.8
XS Rating Curve= 0 ,0
Exp/Cntr=0.5,0.3

Type RM Length L Ch R = 1 ,250.4   ,61.5,61.5,61.5
BEGIN DESCRIPTION:
REPEATED section. Town Street / US 62 Arch Bridge - Upstream Section
From 12-05-3607P LOMR
END DESCRIPTION:
#Sta/Elev= 30
    14.7   762.8     155   762.1   160.5   779.2   874.8   777.1   874.8     765
  1021.2   765.1  1021.3     736  1139.4   730.9  1152.4   743.8    1223   743.9
  1224.4   729.5  1320.6     730    1362     727    1362     704  1435.3   700.4
  1472.5   692.8  1495.9   698.2  1518.2   700.6  1562.9   697.5  1619.3   701.5
  1701.2   700.5  1758.6   696.3  1812.2   699.2  1844.8   697.2  1956.5   703.5
  1959.7   707.4  1971.4   709.1  1973.6   730.1  2674.9   729.5    2684     731
#Mann= 3 , 0 , 0
    14.7    .042       0    1362    .035       0  1973.6     .04       0
#Block Obstruct= 2 , 0
                            2100
Bank Sta=1362,1973.6
XS Rating Curve= 0 ,0
Exp/Cntr=0.5,0.3

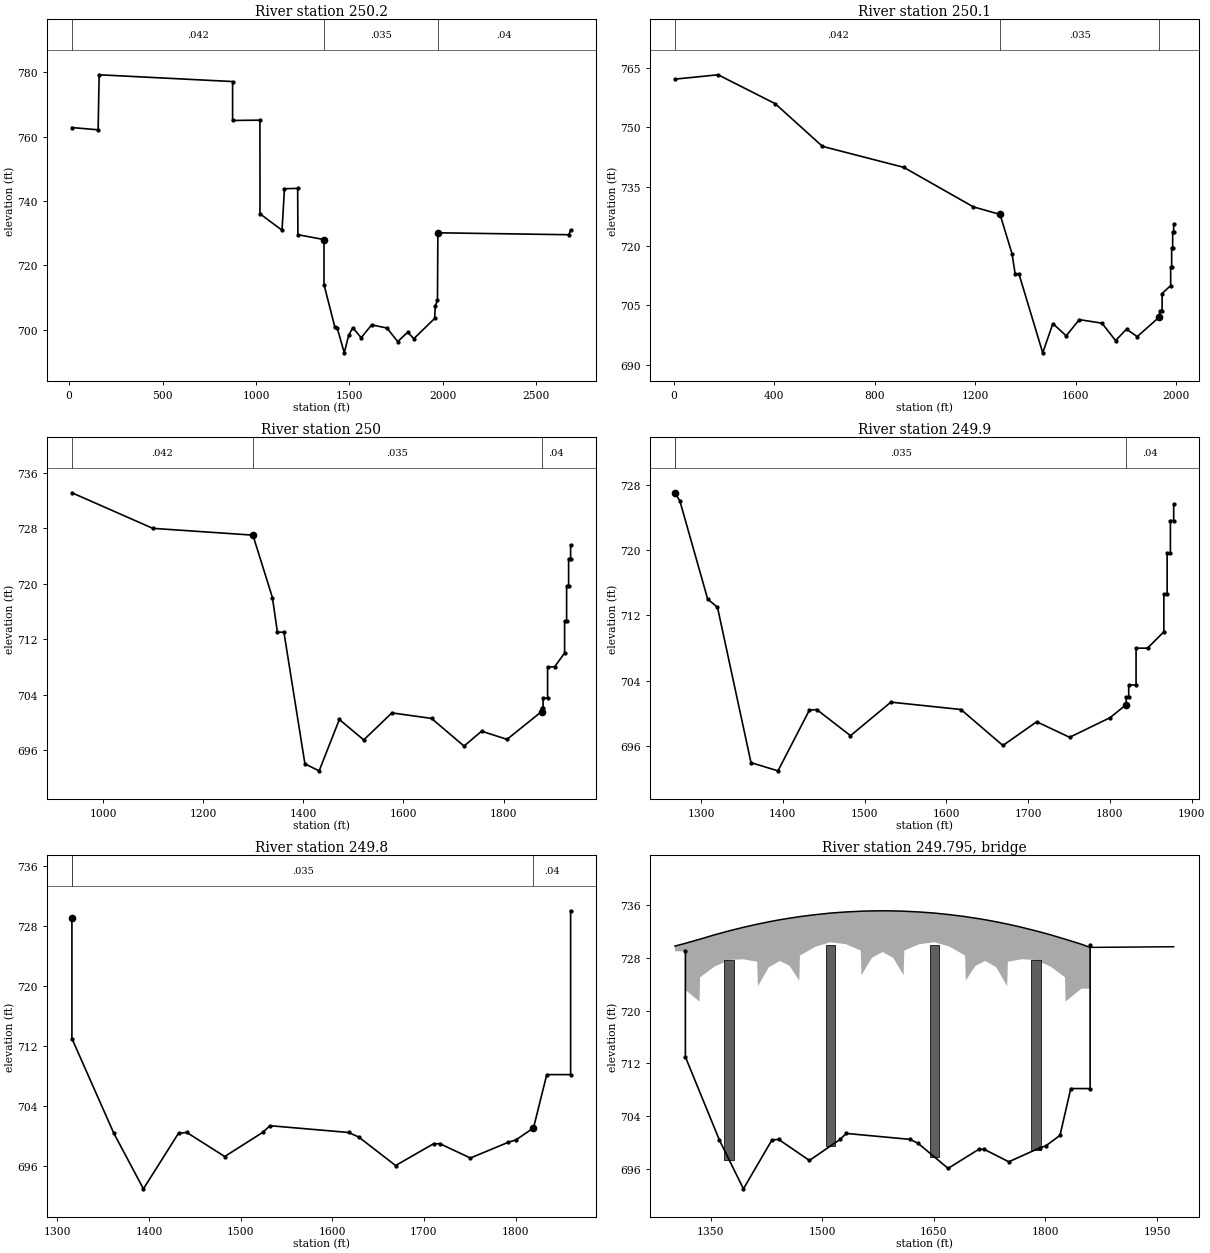
Type RM Length L Ch R = 1 ,250.2   ,52.8,52.8,52.8
BEGIN DESCRIPTION:
Town Street / US 62 Arch Bridge - Downstream Section
From 12-05-3607P LOMR
END DESCRIPTION:
#Sta/Elev= 30
    14.7   762.8     155   762.1   160.5   779.2   874.8   777.1   874.8     765
  1021.2   765.1  1021.3     736  1139.4   730.9  1152.4   743.8    1223   743.9
  1224.4   729.5    1364     728    1364     714  1422.5   700.7  1435.3   700.4
  1472.5   692.8  1495.9   698.2  1518.2   700.6  1562.9   697.5  1619.3   701.5
  1701.2   700.5  1758.6   696.3  1812.2   699.2  1844.8   697.2  1956.5   703.5
  1959.7   707.4  1971.4   709.1  1973.6   730.1  2674.9   729.5    2684     731
#Mann= 3 , 0 , 0
    14.7    .042       0    1364    .035       0  1973.6     .04       0
#Block Obstruct= 2 , 0
                            2100
Bank Sta=1364,1973.6
XS Rating Curve= 0 ,0
Exp/Cntr=0.5,0.3

Type RM Length L Ch R = 1 ,250.1   ,73.42,73.42,73.42
BEGIN DESCRIPTION:
From 12-05-3607P LOMR
END DESCRIPTION:
#Sta/Elev= 30
     5.4   762.2   176.9   763.3   404.1     756   592.4   745.2   915.7   739.9
    1193   729.9    1299     728    1347     718    1359     713    1374     713
  1468.9     693  1509.3   700.4  1562.4   697.3  1614.4   701.4  1704.7   700.5
  1758.8   696.1  1802.4     699  1844.8   697.1    1932     702    1935   703.5
    1944   703.5    1944     708    1978     710    1978   714.6    1982   714.6
    1982   719.6    1986   719.6    1986   723.6    1990   723.6    1990   725.6
#Mann= 3 , 0 , 0
     5.4    .042       0    1299    .035       0    1932     .04       0
#XS Ineff= 2 , 0
       0                    2025       0
Permanent Ineff=
       F       T
#Block Obstruct= 2 , 0
                            2101
Bank Sta=1299,1932
XS Rating Curve= 0 ,0
Exp/Cntr=0.5,0.3

Type RM Length L Ch R = 1 ,250     ,73.5,73.5,73.5
BEGIN DESCRIPTION:
EMHT added cross section, based on B&N adjacent section
From 12-05-3607P LOMR
END DESCRIPTION:
#Sta/Elev= 30
  937.27  733.11 1098.93  727.98    1299     727    1338     718    1348     713
    1361     713    1403     694 1431.45     693 1471.77  700.41 1520.49  697.46
 1576.83  701.36 1656.01  700.56 1721.05  696.57  1756.1  698.72 1806.95  697.54
    1876  701.55    1876     702    1879     702    1879   703.5    1888   703.5
    1888     708    1902     708    1922     710    1922   714.6    1926   714.6
    1926   719.6    1930   719.6    1930   723.6    1934   723.6    1934   725.6
#Mann= 3 , 0 , 0
  937.27    .042       0    1299    .035       0    1876     .04       0
Bank Sta=1299,1876
XS Rating Curve= 0 ,0
Exp/Cntr=0.5,0.3

Type RM Length L Ch R = 1 ,249.9   ,67,67,67
BEGIN DESCRIPTION:
B&N added section
From 12-05-3607P LOMR
END DESCRIPTION:
#Sta/Elev= 30
    1268     727    1274     726    1308     714    1320     713    1361     694
    1394     693  1432.3   700.4  1441.3   700.5  1482.7   697.3  1532.1   701.4
  1617.8   700.5  1669.1   696.1  1710.5     699  1750.7   697.1  1800.2   699.5
    1820   701.1    1820     702    1823     702    1823   703.5    1832   703.5
    1832     708    1846     708    1866     710    1866   714.6    1870   714.6
    1870   719.6    1874   719.6    1874   723.6    1878   723.6    1878   725.6
#Mann= 3 , 0 , 0
    1268    .042       0    1268    .035       0    1820     .04       0
Bank Sta=1268,1820
XS Rating Curve= 0 ,0
Exp/Cntr=0.5,0.3

Type RM Length L Ch R = 1 ,249.8   ,62,62,62
BEGIN DESCRIPTION:
B&N added section - US proposed Rich St Bridge
From 12-05-3607P LOMR
END DESCRIPTION:
#Sta/Elev= 21
    1316     729    1316     713  1361.7   700.4    1394     693  1432.3   700.4
  1441.3   700.5  1482.7   697.3    1524   700.5  1532.1   701.4  1617.8   700.5
  1628.8   699.9  1669.1   696.1  1710.5     699  1717.5     699  1750.7   697.1
  1792.1   699.2  1800.2   699.5  1819.5   701.1    1834   708.2    1860   708.2
    1860     730
#Mann= 3 , 0 , 0
    1316    .042       0    1316    .035       0  1819.5     .04       0
Bank Sta=1316,1819.5
XS Rating Curve= 0 ,0
Exp/Cntr=0.5,0.3

Type RM Length L Ch R = 3 ,249.795 ,,,
BEGIN DESCRIPTION:
Proposed Rich St Bridge
END DESCRIPTION:
Bridge Culvert--1,0,-1,-1, 0
Deck Dist Width WeirC Skew NumUp NumDn MinLoCord MaxHiCord MaxSubmerge Is_Ogee
1,60,2.6,0, 44, 44, , , 0.95, 0, 0,0,,
    1302 1313.75 1335.06 1335.75 1355.25    1375 1393.75  1412.5 1413.47 1428.25
    1443    1456 1469.12    1470  1490.5    1511  1531.5 1551.75 1552.69 1566.75
    1581 1595.25 1609.31 1610.25  1630.5    1651  1671.5    1692 1692.88    1706
    1719 1733.75 1748.53  1749.5 1768.25    1787 1806.75 1826.25 1826.94 1848.25
    1860    1860    1862  1972.3
   729.8  730.15  730.83  730.85  731.51  732.11  732.64  733.12  733.14  733.48
  733.79  734.03  734.25  734.27  734.56   734.8  734.97  735.08  735.09  735.13
  735.15  735.13  735.09  735.08  734.97   734.8  734.56  734.27  734.25  734.03
  733.79  733.48  733.14  733.12  732.64  732.11  731.51  730.85  730.83  730.08
   729.6   729.6   729.6   729.7
  723.35  723.35  721.38  725.06   726.7  727.69   727.8  727.42  723.72   726.6
  727.54  726.81  724.56  728.36  729.69  730.38  730.09  729.12  725.39  728.02
   728.9  728.02  725.39  729.12  730.09  730.38  729.69  728.36  724.56  726.81
  727.54   726.6  723.72  727.42   727.8  727.69   726.7  725.06  721.38  723.35
  723.35       0       0       0
    1302 1313.75 1335.06 1335.75 1355.25    1375 1393.75  1412.5 1413.47 1428.25
    1443    1456 1469.12    1470  1490.5    1511  1531.5 1551.75 1552.69 1566.75
    1581 1595.25 1609.31 1610.25  1630.5    1651  1671.5    1692 1692.88    1706
    1719 1733.75 1748.53  1749.5 1768.25    1787 1806.75 1826.25 1826.94 1848.25
    1860    1860    1862  1972.3
   729.8  730.15  730.83  730.85  731.51  732.11  732.64  733.12  733.14  733.48
  733.79  734.03  734.25  734.27  734.56   734.8  734.97  735.08  735.09  735.13
  735.15  735.13  735.09  735.08  734.97   734.8  734.56  734.27  734.25  734.03
  733.79  733.48  733.14  733.12  732.64  732.11  731.51  730.85  730.83  730.08
   729.6   729.6   729.6   729.7
  723.35  723.35  721.38  725.06   726.7  727.69   727.8  727.42  723.72   726.6
  727.54  726.81  724.56  728.36  729.69  730.38  730.09  729.12  725.39  728.02
   728.9  728.02  725.39  729.12  730.09  730.38  729.69  728.36  724.56  726.81
  727.54   726.6  723.72  727.42   727.8  727.69   726.7  725.06  721.38  723.35
  723.35       0       0       0
Pier Skew, UpSta & Num, DnSta & Num=  ,1375, 6 ,1375, 6 , 3 , 3 , 0 ,,
     6.5     6.5       9       9      13      13
       0   701.5   701.5   706.5   706.5     730
     6.5     6.5       9       9      13      13
       0   701.5   701.5   706.5   706.5     730
Pier Skew, UpSta & Num, DnSta & Num=  ,1511, 6 ,1511, 6 , 3 , 3 , 0 ,,
     6.5     6.5       9       9      13      13
       0   701.5   701.5   706.5   706.5     730
     6.5     6.5       9       9      13      13
       0   701.5   701.5   706.5   706.5     730
Pier Skew, UpSta & Num, DnSta & Num=  ,1651, 6 ,1651, 6 , 3 , 3 , 0 ,,
     6.5     6.5       9       9      13      13
       0   701.5   701.5   706.5   706.5     730
     6.5     6.5       9       9      13      13
       0   701.5   701.5   706.5   706.5     730
Pier Skew, UpSta & Num, DnSta & Num=  ,1787, 6 ,1787, 6 , 3 , 3 , 0 ,,
     6.5     6.5       9       9      13      13
       0   701.5   701.5   706.5   706.5     730
     6.5     6.5       9       9      13      13
       0   701.5   701.5   706.5   706.5     730
BR Coef=-1 , 0 , 0 ,, 0 ,,,0.8,-1,,0,
WSPro=,,,, 1 ,,,, 0 ,,,, 0 ,,,,-1 ,-1 ,-1 , 0 , 0 , 0 , 0 , 0
BC Design=,, 0 ,, 0 ,,,,,,
BC Use User HTab Curves=0
BC User HTab FreeFlow(D)= 0

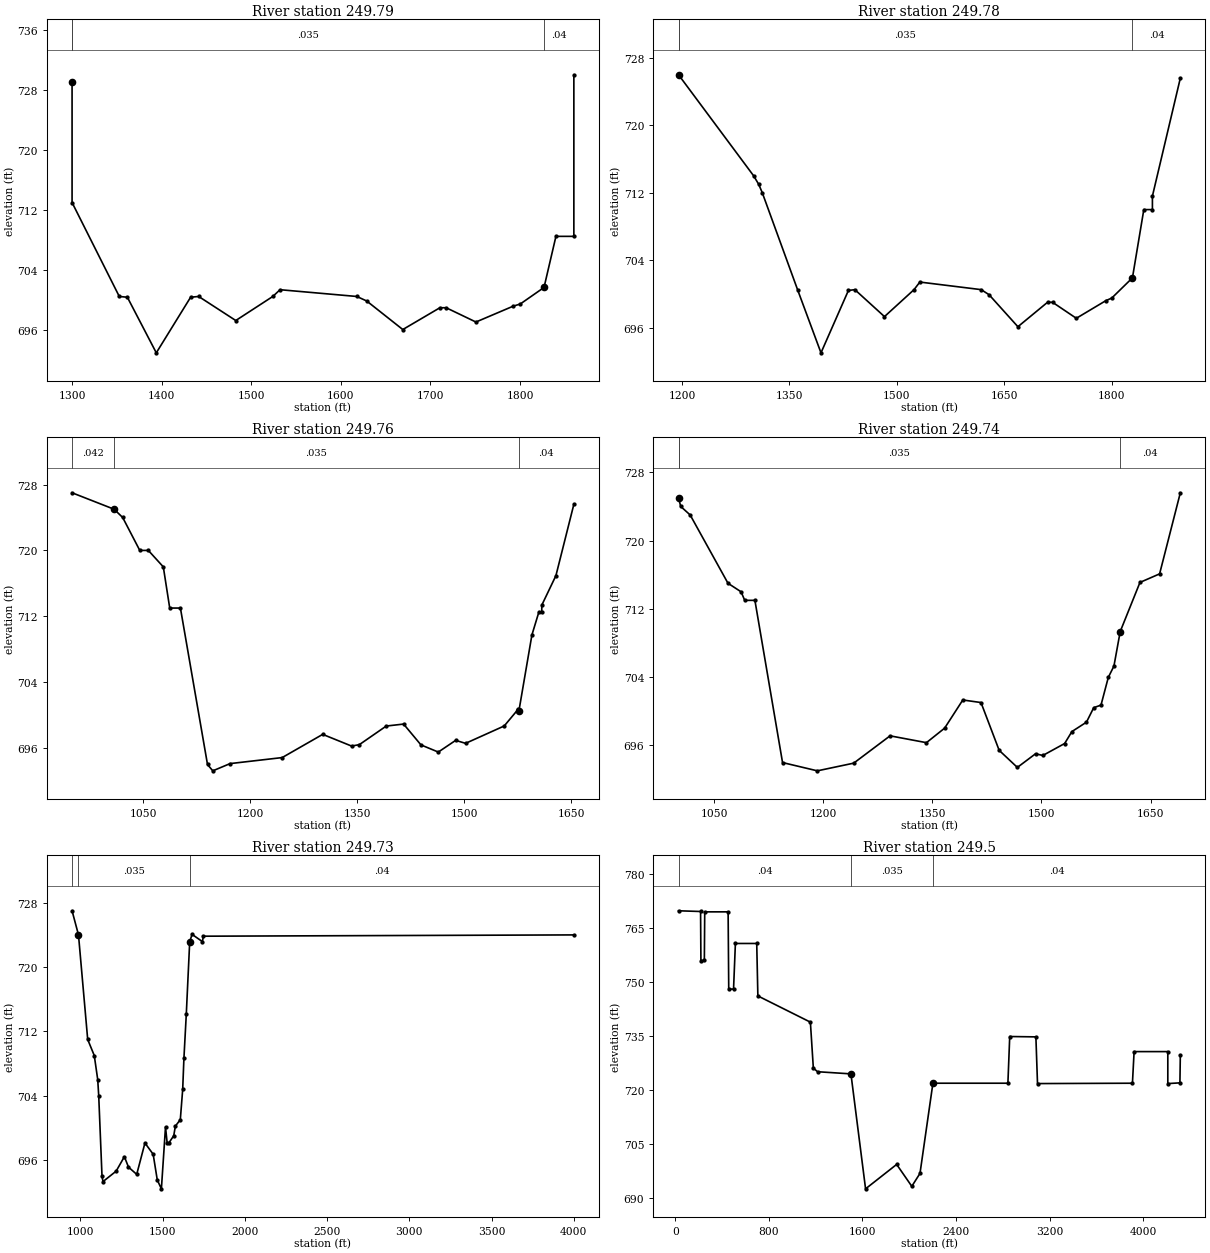
Type RM Length L Ch R = 1 ,249.79  ,67,67,67
BEGIN DESCRIPTION:
B&N added section - DS proposed Rich St Bridge
From 12-05-3607P LOMR
END DESCRIPTION:
#Sta/Elev= 22
    1300     729    1300     713  1352.7   700.5  1361.7   700.4    1394     693
  1432.3   700.4  1441.3   700.5  1482.7   697.3    1524   700.5  1532.1   701.4
  1617.8   700.5  1628.8   699.9  1669.1   696.1  1710.5     699  1717.5     699
  1750.7   697.1  1792.1   699.2  1800.2   699.5  1826.7   701.7    1840   708.5
    1860   708.5    1860     730
#Mann= 3 , 0 , 0
    1300    .042       0    1300    .035       0  1826.7     .04       0
Bank Sta=1300,1826.7
XS Rating Curve= 0 ,0
Exp/Cntr=0.5,0.3

Type RM Length L Ch R = 1 ,249.78  ,124,124,124
BEGIN DESCRIPTION:
B&N added section
From 12-05-3607P LOMR
END DESCRIPTION:
#Sta/Elev= 24
    1195     726    1300     714    1307     713    1312     712  1361.7   700.4
    1394     693  1432.3   700.4  1441.3   700.5  1482.7   697.3    1524   700.5
  1532.1   701.4  1617.8   700.5  1628.8   699.9  1669.1   696.1  1710.5     699
  1717.5     699  1750.7   697.1  1792.1   699.2  1800.2   699.5  1829.1   701.9
    1845     710    1857     710    1857   711.6    1896   725.6
#Mann= 3 , 0 , 0
    1195    .042       0    1195    .035       0  1829.1     .04       0
Bank Sta=1195,1829.1
XS Rating Curve= 0 ,0
Exp/Cntr=0.5,0.3

Type RM Length L Ch R = 1 ,249.76  ,105,105,105
BEGIN DESCRIPTION:
EMH&T added cross section, based on DLZ survey
From 12-05-3607P LOMR
END DESCRIPTION:
#Sta/Elev= 30
     950     727    1009     725    1021     724    1045     720    1057     720
    1078     718    1087     713    1102     713    1140     694 1147.41  693.23
 1171.74  694.11 1244.75  694.84 1301.61  697.66  1342.1  696.24 1353.01  696.41
 1390.77  698.67 1415.11  698.91 1439.44  696.38 1463.78  695.51 1488.12  696.93
 1502.07  696.57 1556.26  698.68 1575.73   700.7 1576.75  700.45  1595.1  709.73
 1604.98  712.55 1608.95  712.55 1608.95  713.35  1628.8  716.94 1653.95   725.6
#Mann= 3 , 0 , 0
     950    .042       0    1009    .035       0 1576.75     .04       0
Bank Sta=1009,1576.75
XS Rating Curve= 0 ,0
Exp/Cntr=0.5,0.3

Type RM Length L Ch R = 1 ,249.74  ,142,142,142
BEGIN DESCRIPTION:
DLZ survey section #4
From 12-05-3607P LOMR
END DESCRIPTION:
#Sta/Elev= 30
    1001     725    1004     724    1017     723    1069     715    1087     714
    1092     713    1106     713    1144     694 1191.84  693.03 1241.84  693.93
 1291.84  697.13 1341.84  696.33 1366.84  698.03 1391.84  701.33 1416.84  701.03
 1441.84  695.43 1466.84  693.43 1491.84  695.03 1501.84  694.83 1531.84  696.23
 1541.84  697.63 1561.84  698.73 1571.84  700.43 1581.84  700.73 1591.89  703.98
 1599.62   705.3 1608.23  709.34  1635.4   715.1  1662.4   716.1  1690.9   725.6
#Mann= 3 , 0 , 0
    1001    .042       0    1001    .035       0 1608.23     .04       0
Bank Sta=1001,1608.23
XS Rating Curve= 0 ,0
Exp/Cntr=0.5,0.3

Type RM Length L Ch R = 1 ,249.73  ,92,92,92
BEGIN DESCRIPTION:
DLZ survey section #3
From 12-05-3607P LOMR
END DESCRIPTION:
#Sta/Elev= 30
     950     727     989     724    1045     711    1085     709    1106     706
    1112     704    1132     694 1137.95  693.33 1217.95  694.63 1267.95  696.43
 1292.95  695.13 1342.95  694.23 1392.95  698.13 1442.95  696.73 1467.95  693.53
 1492.95  692.43 1517.95  700.13 1527.95  698.13 1537.95  698.13 1567.95  699.03
 1577.95  700.23 1607.95  701.03 1622.41   704.8 1629.91  708.68  1644.2  714.11
 1664.94  723.14 1679.35  724.07 1741.78  723.17 1748.46  723.84    4000     724
#Mann= 3 , 0 , 0
     950    .042       0     989    .035       0 1664.94     .04       0
#Block Obstruct= 2 , 0
       0                 1748.46       0     740
Bank Sta=989,1664.94
XS Rating Curve= 0 ,0
Exp/Cntr=0.5,0.3

Type RM Length L Ch R = 1 ,249.5   ,43.6,43.6,43.6
BEGIN DESCRIPTION:
AH
From 12-05-3607P LOMR
END DESCRIPTION:
#Sta/Elev= 30
    27.8   769.9   216.2   769.7   219.1     756   248.5   756.1   251.7   769.6
   451.7   769.6     457   748.1   498.1   748.1   513.9   760.8   696.3   760.8
     706   746.2    1155   738.9  1180.3   726.1  1216.7   725.1  1501.7   724.5
  1626.8   692.5  1892.6   699.3    2022   693.2  2092.1   696.8  2202.5   721.9
  2843.6   721.9  2859.2   734.9  3082.9   734.8  3096.7   721.8  3908.3   721.9
  3922.5   730.7  4210.7   730.7  4210.7   721.8  4314.2     722  4317.7   729.7
#Mann= 3 , 0 , 0
    27.8     .04       0  1501.7    .035       0  2202.5     .04       0
#Block Obstruct= 2 , 0
                            2225
Bank Sta=1501.7,2202.5
XS Rating Curve= 0 ,0
Exp/Cntr=0.5,0.3

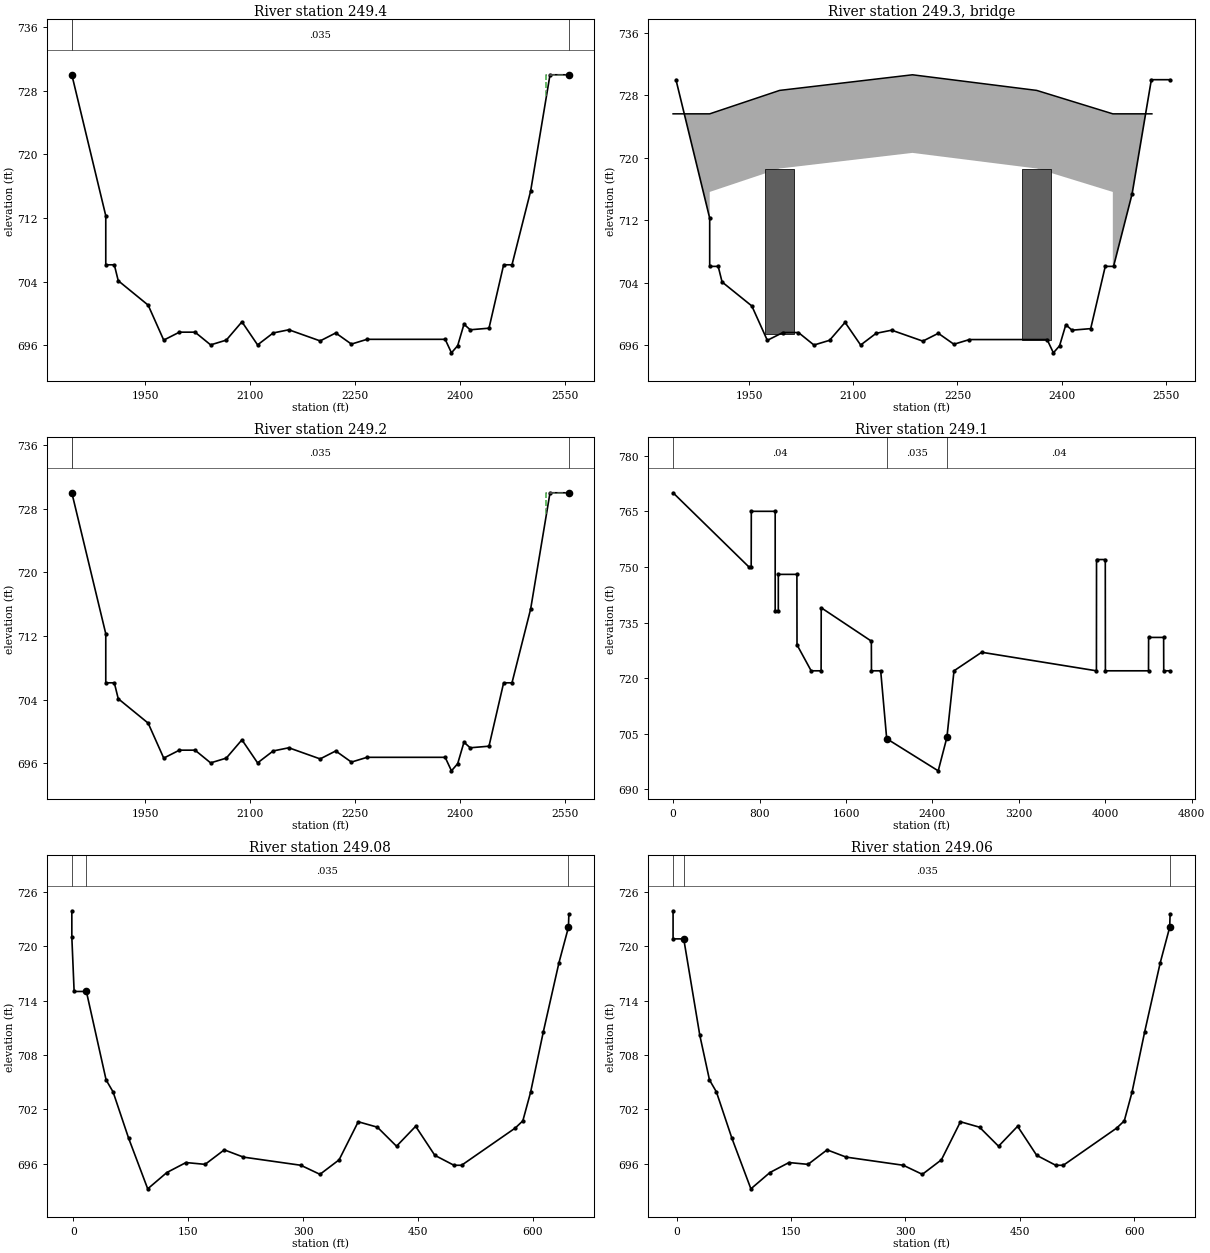
Type RM Length L Ch R = 1 ,249.4   ,80,80,80
BEGIN DESCRIPTION:
DLZ rev w/ #2  Main Street Bridge - Upstream Section
From 12-05-3607P LOMR
END DESCRIPTION:
#Sta/Elev= 30
  1844.8     730 1893.36  712.27 1893.36   706.1  1905.6   706.1  1911.2   704.1
    1954  701.03  1976.3  696.63  1998.7  697.63  2021.1  697.63  2043.4  696.03
  2065.8  696.63  2088.2  698.93  2110.6  696.03  2132.9  697.53  2155.3  697.93
  2200.1  696.53  2222.4  697.53  2244.8  696.13  2267.2  696.73    2379  696.73
    2388  695.03  2396.9  695.93  2405.9  698.63  2414.8  697.93  2441.7  698.13
 2462.66   706.1  2474.6   706.1  2501.3  715.38    2529     730    2556     730
#Mann= 3 , 0 , 0
  1844.8     .04       0  1844.8    .035       0    2556     .04       0
#XS Ineff= 2 , 0
       0 1844.95     730 2523.85       0     730
Permanent Ineff=
       F       F
#Block Obstruct= 2 , 0
                            2556
Bank Sta=1844.8,2556
XS Rating Curve= 0 ,0
Skew Angle= 26.5
Exp/Cntr=0.5,0.3

Type RM Length L Ch R = 3 ,249.3   ,,,
BEGIN DESCRIPTION:
Structure #8 West Main Street / Ohio State Route 3 Arch Bridge  C-Pier parallel to flow
END DESCRIPTION:
Bridge Culvert--1,0,-1,-1, 0
Deck Dist Width WeirC Skew NumUp NumDn MinLoCord MaxHiCord MaxSubmerge Is_Ogee
2,76,3.1,0, 7, 7, 730, , 0.95, 0, 0,0,,
1840.6591893.364    19942185.209    23642473.5332529.759
  725.63  725.63  728.63  730.63  728.63  725.63  725.63
          715.63  718.63  720.63  718.63  715.63
1840.6591893.364    19942185.209    23642473.5332529.759
  725.63  725.63  728.63  730.63  728.63  725.63  725.63
          715.63  718.63  720.63  718.63  715.63
Pier Skew, UpSta & Num, DnSta & Num=  ,1994, 7 ,1994, 7 , 0 , 0 , 0 ,,
    41.2      40      40      34      34      28      28
   701.5   701.5   708.8   708.8   711.8   711.8     720
    41.2      40      40      34      34      28      28
   701.5   701.5   708.8   708.8   711.8   711.8     720
Pier Skew, UpSta & Num, DnSta & Num=  ,2364, 7 ,2364, 7 , 0 , 0 , 0 ,,
    41.2      40      40      34      34      28      28
   701.5   701.5   708.8   708.8   711.8   711.8     720
    41.2      40      40      34      34      28      28
   701.5   701.5   708.8   708.8   711.8   711.8     720
BR Coef= 1 , 0 ,-1 ,1.25, 0 ,,,0.7980869,-1,,0,728
WSPro=,,,, 1 ,,,, 0 ,,,, 0 ,,,,-1 ,-1 ,-1 , 0 , 0 , 0 , 0 , 0
BC Design=,, 0 ,, 0 ,,,,,,
BC HTab HWMax=769.9
BC Use User HTab Curves=0
BC User HTab FreeFlow(D)= 0

Type RM Length L Ch R = 1 ,249.2   ,43.5,43.5,43.5
BEGIN DESCRIPTION:
DLZ rev w/ #2 Main Street Bridge - Downstream Section
From 12-05-3607P LOMR
END DESCRIPTION:
#Sta/Elev= 30
  1844.8     730 1893.36  712.27 1893.36   706.1  1905.6   706.1  1911.2   704.1
    1954  701.03  1976.3  696.63  1998.7  697.63  2021.1  697.63  2043.4  696.03
  2065.8  696.632088.199  698.93  2110.6  696.03  2132.9  697.53  2155.3  697.93
  2200.1  696.53  2222.4  697.532244.801  696.13  2267.2  696.73    2379  696.73
    2388  695.03  2396.9  695.93  2405.9  698.632414.801  697.932441.699  698.13
 2462.66   706.1  2474.6   706.12501.301  715.38    2529     730    2556     730
#Mann= 3 , 0 , 0
  1844.8     .04       0  1844.8    .035       0    2556     .04       0
#XS Ineff= 2 , 0
       0 1844.95     730 2523.85       0     730
Permanent Ineff=
       F       F
#Block Obstruct= 2 , 0
                            2556
Bank Sta=1844.8,2556
XS Rating Curve= 0 ,0
Skew Angle= 26.5
Exp/Cntr=0.5,0.3

Type RM Length L Ch R = 1 ,249.1   ,41.1,41.1,41.1
BEGIN DESCRIPTION:
Bikeway Sta. 2+25
From 12-05-3607P LOMR
END DESCRIPTION:
#Sta/Elev= 30
       0     770     702     750     723     750     724     765     945     765
     945     738     974     738     974     748    1146     748    1147     729
    1278     722    1370     722    1371     739    1835     730    1836     722
  1921.4     722    1977   703.7  2453.8  695.03  2534.2  704.04    2600     722
    2856     727    3918     722    3919     752    4000     752    4001     722
    4400     722    4401     731    4540     731    4541     722    4600     722
#Mann= 3 , 0 , 0
       0     .04       0    1977    .035       0  2534.2     .04       0
#Block Obstruct= 2 , 0
                            2600
Bank Sta=1977,2534.2
XS Rating Curve= 0 ,0
Exp/Cntr=0.5,0.3

Type RM Length L Ch R = 1 ,249.08  ,32.9,32.9,32.9
BEGIN DESCRIPTION:
Bikeway Sta. 3+25
From 12-05-3607P LOMR
END DESCRIPTION:
#Sta/Elev= 30
      -2   723.9      -2     721       1     715      17     715   42.78  705.24
   51.88  703.92   72.12  698.83   97.12  693.23  122.12  695.03  147.12  696.13
  172.12  695.93  197.12  697.53  222.12  696.73  297.12  695.83  322.12  694.83
  347.12  696.43  372.12  700.63  397.12  700.03  422.12  697.93  447.12  700.13
  472.12  696.93  497.12  695.83  507.12  695.83  577.12  699.93  587.12  700.73
  597.22  703.87  613.86  710.54  634.33  718.18  646.69  722.08  647.26  723.54
#Mann= 3 , 0 , 0
      -2     .04       0      17    .035       0  646.69     .04       0
Bank Sta=17,646.69
XS Rating Curve= 0 ,0
Exp/Cntr=0.5,0.3

Type RM Length L Ch R = 1 ,249.06  ,18.7,18.7,18.7
BEGIN DESCRIPTION:
Bikeway Sta. 4+25
From 12-05-3607P LOMR
END DESCRIPTION:
#Sta/Elev= 30
      -5   723.9      -5   720.8       9   720.8   30.09  710.16   42.78  705.24
   51.88  703.92   72.12  698.83   97.12  693.23  122.12  695.03  147.12  696.13
  172.12  695.93  197.12  697.53  222.12  696.73  297.12  695.83  322.12  694.83
  347.12  696.43  372.12  700.63  397.12  700.03  422.12  697.93  447.12  700.13
  472.12  696.93  497.12  695.83  507.12  695.83  577.12  699.93  587.12  700.73
  597.22  703.87  613.86  710.54  634.33  718.18  646.69  722.08  647.26  723.54
#Mann= 3 , 0 , 0
      -5     .04       0       9    .035       0  646.69     .04       0
Bank Sta=9,646.69
XS Rating Curve= 0 ,0
Exp/Cntr=0.5,0.3

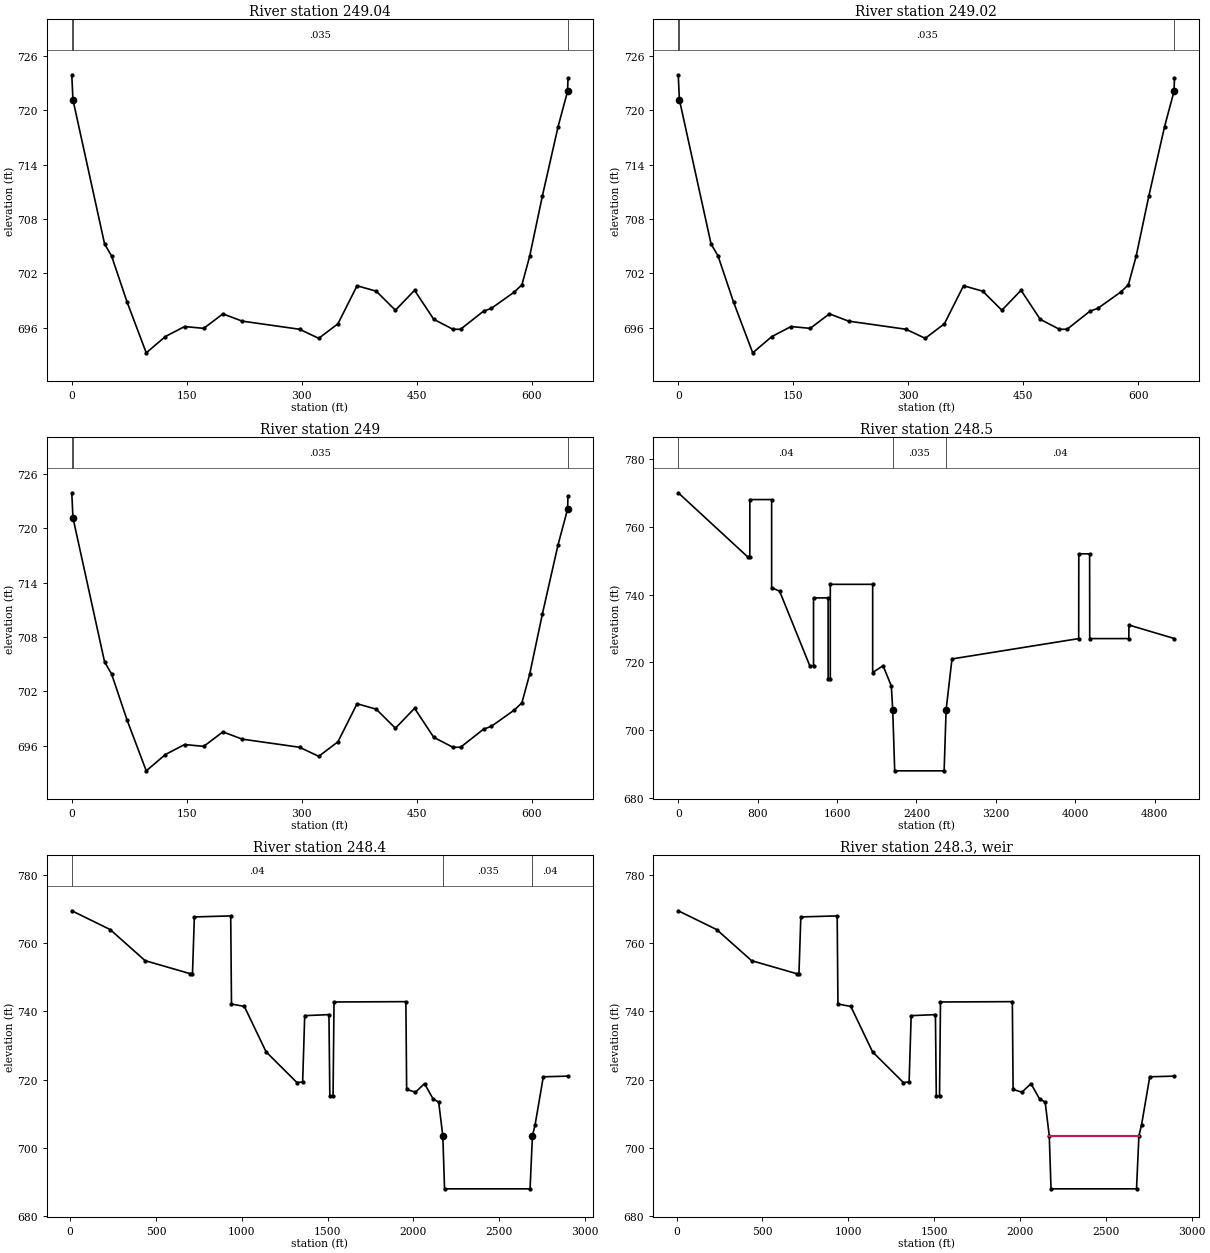
Type RM Length L Ch R = 1 ,249.04  ,25.8,25.8,25.8
BEGIN DESCRIPTION:
Bikeway Sta. 4+75
From 12-05-3607P LOMR
END DESCRIPTION:
#Sta/Elev= 30
       0   723.9    1.48  721.16   42.78  705.24   51.88  703.92   72.12  698.83
   97.12  693.23  122.12  695.03  147.12  696.13  172.12  695.93  197.12  697.53
  222.12  696.73  297.12  695.83  322.12  694.83  347.12  696.43  372.12  700.63
  397.12  700.03  422.12  697.93  447.12  700.13  472.12  696.93  497.12  695.83
  507.12  695.83  537.12  697.83  547.12  698.13  577.12  699.93  587.12  700.73
  597.22  703.87  613.86  710.54  634.33  718.18  646.69  722.08  647.26  723.54
#Mann= 3 , 0 , 0
       0     .04       0    1.48    .035       0  646.69     .04       0
Bank Sta=1.48,646.69
XS Rating Curve= 0 ,0
Exp/Cntr=0.5,0.3

Type RM Length L Ch R = 1 ,249.02  ,21.4,21.4,21.4
BEGIN DESCRIPTION:
Bikeway Sta. 5+50, tie-in into existing conditon
From 12-05-3607P LOMR
END DESCRIPTION:
#Sta/Elev= 30
       0   723.9    1.48  721.16   42.78  705.24   51.88  703.92   72.12  698.83
   97.12  693.23  122.12  695.03  147.12  696.13  172.12  695.93  197.12  697.53
  222.12  696.73  297.12  695.83  322.12  694.83  347.12  696.43  372.12  700.63
  397.12  700.03  422.12  697.93  447.12  700.13  472.12  696.93  497.12  695.83
  507.12  695.83  537.12  697.83  547.12  698.13  577.12  699.93  587.12  700.73
  597.22  703.87  613.86  710.54  634.33  718.18  646.69  722.08  647.26  723.54
#Mann= 3 , 0 , 0
       0     .04       0    1.48    .035       0  646.69     .04       0
Bank Sta=1.48,646.69
XS Rating Curve= 0 ,0
Exp/Cntr=0.5,0.3

Type RM Length L Ch R = 1 ,249     ,80,80,80
BEGIN DESCRIPTION:
DLZ #1 just upstream of weir
From 12-05-3607P LOMR
END DESCRIPTION:
#Sta/Elev= 30
       0   723.9    1.48  721.16   42.78  705.24   51.88  703.92   72.12  698.83
   97.12  693.23  122.12  695.03  147.12  696.13  172.12  695.93  197.12  697.53
  222.12  696.73  297.12  695.83  322.12  694.83  347.12  696.43  372.12  700.63
  397.12  700.03  422.12  697.93  447.12  700.13  472.12  696.93  497.12  695.83
  507.12  695.83  537.12  697.83  547.12  698.13  577.12  699.93  587.12  700.73
  597.22  703.87  613.86  710.54  634.33  718.18  646.69  722.08  647.26  723.54
#Mann= 3 , 0 , 0
       0     .04       0    1.48    .035       0  646.69     .04       0
Bank Sta=1.48,646.69
XS Rating Curve= 0 ,0
Exp/Cntr=0.5,0.3

Type RM Length L Ch R = 1 ,248.5   ,10,10,10
BEGIN DESCRIPTION:
From 12-05-3607P LOMR
END DESCRIPTION:
#Sta/Elev= 30
       0     770     703     751     721     751     721     768     941     768
     941     742    1021     741    1325     719    1363     719    1363     739
    1510     739    1510     715    1532     715    1532     743    1959     743
    1959     717    2064     719    2147     713    2161     706    2181     688
    2679     688    2699     706    2758     721    4035     727    4036     752
    4145     752    4146     727    4540     727    4541     731    5000     727
#Mann= 3 , 0 , 0
       0     .04       0    2161    .035       0    2699     .04       0
#XS Ineff= 2 , 0
       0    1950                       0
Permanent Ineff=
       T       F
#Block Obstruct= 2 , 0
                            2758
Bank Sta=2161,2699
XS Rating Curve= 0 ,0
Exp/Cntr=0.5,0.3

Type RM Length L Ch R = 1 ,248.4   ,11.5,11.5,11.5
BEGIN DESCRIPTION:
REPEATED section. Rich Street Weir - Upstream Section
From 12-05-3607P LOMR
END DESCRIPTION:
#Sta/Elev= 30
     9.9   769.4   233.5   763.9   436.9   754.8   698.8     751   712.9     751
   723.8   767.6   935.5   767.9     940   742.1  1014.9   741.4  1141.6   728.1
  1321.5   719.1  1354.5   719.3  1366.5   738.7  1507.7     739  1512.8   715.1
  1531.6   715.1  1537.2   742.7  1955.7   742.8  1960.2   717.1  2011.6   716.3
  2064.3   718.8  2114.3   714.3  2146.8   713.4  2170.8   703.5    2181     688
    2679     688  2692.8   703.5  2708.5   706.8  2756.1   720.8    2900     721
#Mann= 3 , 0 , 0
     9.9     .04       0  2170.8    .035       0  2692.8     .04       0
#XS Ineff= 2 , 0
       0    1950                       0
Permanent Ineff=
       T       F
#Block Obstruct= 2 , 0
                            2900
Bank Sta=2170.8,2692.8
XS Rating Curve= 0 ,0
Exp/Cntr=0.5,0.3

Type RM Length L Ch R = 5 ,248.3   ,,,
Node Photo=Rich Street Weir.jpg
IW Pilot Flow=0
#Inline Weir SE= 2
  2170.8   703.5  2692.8   703.5
IW Dist,WD,Coef,Skew,MaxSub,Min_El,Is_Ogee,SpillHt,DesHd
1,10,3,0,0.95,, 0 ,,,0,0,