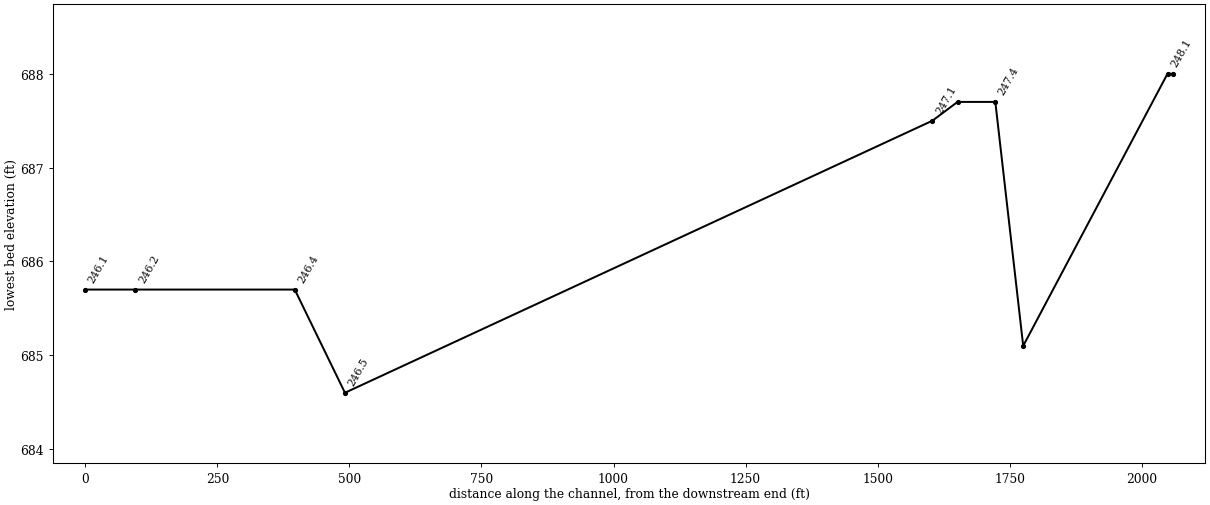
HEC-RAS study FRA-70-1321R.prj: FRA-70-1321R

--- FRA-70-1321R.g02 (geometry) --- (continued)

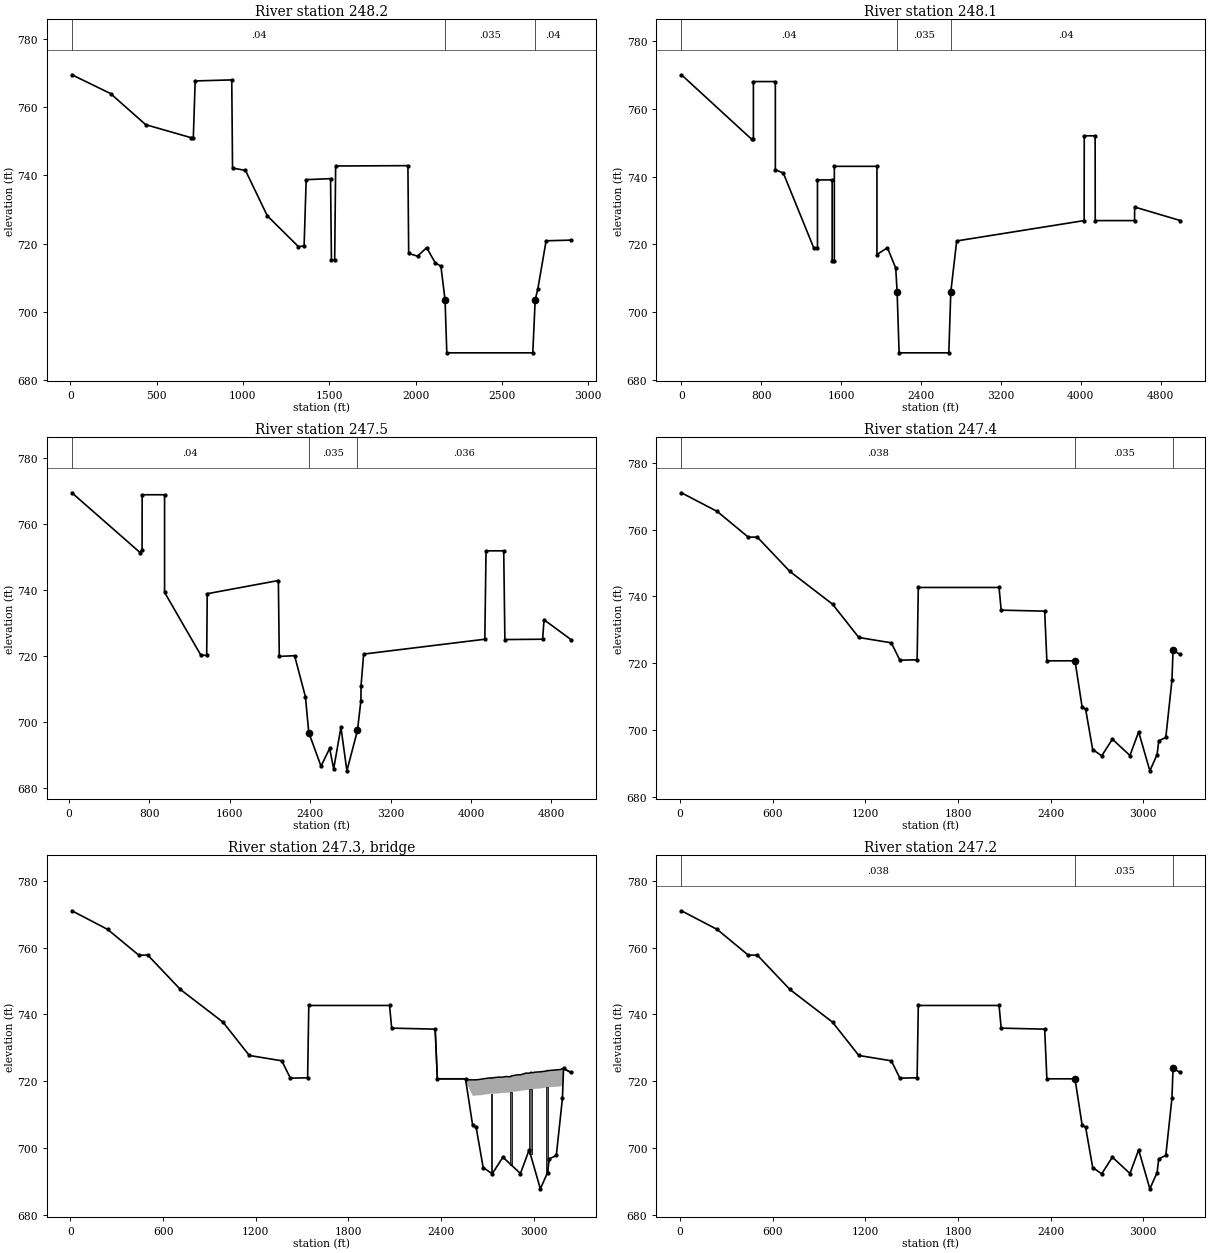
Type RM Length L Ch R = 1 ,248.2   ,10,10,10
BEGIN DESCRIPTION:
Rich Street Weir - Downstream Section
From 12-05-3607P LOMR
END DESCRIPTION:
#Sta/Elev= 30
     9.9   769.4   233.5   763.9   436.9   754.8   698.8     751   712.9     751
   723.8   767.6   935.5   767.9     940   742.1  1014.9   741.4  1141.6   728.1
  1321.5   719.1  1354.5   719.3  1366.5   738.7  1507.7     739  1512.8   715.1
  1531.6   715.1  1537.2   742.7  1955.7   742.8  1960.2   717.1  2011.6   716.3
  2064.3   718.8  2114.3   714.3  2146.8   713.4  2170.8   703.5    2181     688
    2679     688  2692.8   703.5  2708.5   706.8  2756.1   720.8    2900     721
#Mann= 3 , 0 , 0
     9.9     .04       0  2170.8    .035       0  2692.8     .04       0
#XS Ineff= 2 , 0
       0    1950                       0
Permanent Ineff=
       T       F
#Block Obstruct= 2 , 0
                            2900
Bank Sta=2170.8,2692.8
XS Rating Curve= 0 ,0
Exp/Cntr=0.5,0.3

Type RM Length L Ch R = 1 ,248.1   ,273.19,273.19,273.19
BEGIN DESCRIPTION:
From 12-05-3607P LOMR
END DESCRIPTION:
#Sta/Elev= 30
       0     770     703     751     721     751     721     768     941     768
     941     742    1021     741    1325     719    1363     719    1363     739
    1510     739    1510     715    1532     715    1532     743    1959     743
    1959     717    2064     719    2147     713    2161     706    2181     688
    2679     688    2699     706    2758     721    4035     727    4036     752
    4145     752    4146     727    4540     727    4541     731    5000     727
#Mann= 3 , 0 , 0
       0     .04       0    2161    .035       0    2699     .04       0
#XS Ineff= 2 , 0
       0    1950                       0
Permanent Ineff=
       T       F
#Block Obstruct= 2 , 0
                            2758
Bank Sta=2161,2699
XS Rating Curve= 0 ,0
Exp/Cntr=0.5,0.3

Type RM Length L Ch R = 1 ,247.5   ,52.8,52.8,52.8
BEGIN DESCRIPTION:
AG
From 12-05-3607P LOMR
END DESCRIPTION:
#Sta/Elev= 30
    30.1   769.4   710.9   751.2   727.9   752.1   728.8   768.8   951.8   768.8
   951.8   739.2    1312   720.2  1370.7   720.1  1376.2   738.8  2083.7   742.8
  2092.7   719.8  2245.2     720  2353.3   707.5  2386.1   696.7    2508   686.5
  2593.7   691.9  2633.9   685.7  2706.1   698.3  2765.4   685.1  2870.8   697.4
  2904.9   706.4  2906.2   710.9  2931.9   720.5  4137.5     725  4149.5   751.8
  4325.5   751.8  4337.1   724.9  4712.6     725  4726.4   730.9  4994.4   724.9
#Mann= 3 , 0 , 0
    30.1     .04       0  2386.1    .035       0  2870.8    .036       0
#XS Ineff= 2 , 0
       0    2075                       0
Permanent Ineff=
       T       F
#Block Obstruct= 2 , 0
                            3140
Bank Sta=2386.1,2870.8
XS Rating Curve= 0 ,0
Exp/Cntr=0.3,0.1

Type RM Length L Ch R = 1 ,247.4   ,71.5,71.5,71.5
BEGIN DESCRIPTION:
REPEATED section.  Penn Central Railroad Bridge Crossing #1 - Upstream Section
END DESCRIPTION:
#Sta/Elev= 30
     9.5   771.1   241.1   765.5     442   757.8   500.7   757.8   711.7   747.5
   987.6   737.7  1157.8   727.7  1368.2   726.1  1423.7   720.9  1535.4     721
    1543   742.7  2065.9   742.7  2079.5   735.9  2361.2   735.6  2375.4   720.7
  2557.6   720.7    2604   706.7  2626.2   706.2  2671.9   694.1  2730.5   692.2
  2799.6   697.2  2913.3   692.3  2969.6   699.4  3042.2   687.7  3089.1   692.6
  3099.6   696.7  3145.4   697.7  3185.2   714.9  3192.2   723.8  3240.3   722.6
#Mann= 3 , 0 , 0
     9.5    .038       0  2557.6    .035       0  3192.2    .038       0
#XS Ineff= 2 , 0
       0    2350                       0
Permanent Ineff=
       T       F
#Block Obstruct= 2 , 0
                          3240.3
Bank Sta=2557.6,3192.2
XS Rating Curve= 0 ,0
Exp/Cntr=0.5,0.3

Type RM Length L Ch R = 3 ,247.3   ,,,
BEGIN DESCRIPTION:
Structure #6 Penn Central Railroad Bridge, Crossing #1
END DESCRIPTION:
Bridge Culvert--1,0,-1,-1, 0
Deck Dist Width WeirC Skew NumUp NumDn MinLoCord MaxHiCord MaxSubmerge Is_Ogee
1,70,2.6,0, 37, 37, 720, , 0.95, 0, 0,0,,
  2361.2  2375.4  2557.6    2560  2626.2  2661.4  2671.9    2720  2722.1  2728.1
  2730.5  2769.2  2799.6  2819.5  2846.4  2848.2    2857  2858.2  2893.4  2913.3
  2947.3  2969.6  2971.9  2982.5    2986  3008.2  3042.2  3077.4  3080.9  3086.8
  3089.1  3099.6    3175  3180.5    3190  3192.2  3240.3
   735.6   720.7   720.7   720.4   720.4   720.6   720.7     721   720.9   720.9
     721   721.2   721.2   721.4   721.3   721.4   721.6   721.6   721.9   721.9
   722.4   722.4   722.4   722.7   722.5   722.7   722.8     723   723.1   723.2
   723.1   723.2   723.5   723.7   723.8   723.8   722.6
   735.6   720.7   720.7   715.4   715.7   715.8   715.9   716.2   716.3   716.2
   716.2   716.3   716.5   716.5   716.6   716.7   716.8   716.8   716.9   717.1
   717.3   717.4   717.5   717.7   717.6   717.7   717.8   718.1   718.2   718.1
   718.2   718.2   718.4   718.7   718.8   723.8   722.6
  2361.2  2375.4  2557.6    2560  2626.2  2661.4  2671.9    2720  2722.1  2728.1
  2730.5  2769.2  2799.6  2819.5  2846.4  2848.2    2857  2858.2  2893.4  2913.3
  2947.3  2969.6  2971.9  2982.5    2986  3008.2  3042.2  3077.4  3080.9  3086.8
  3089.1  3099.6    3175  3180.5    3190  3192.2  3240.3
   735.6   720.7   720.7   720.4   720.4   720.6   720.7     721   720.9   720.9
     721   721.2   721.2   721.4   721.3   721.4   721.6   721.6   721.9   721.9
   722.4   722.4   722.4   722.7   722.5   722.7   722.8     723   723.1   723.2
   723.1   723.2   723.5   723.7   723.8   723.8   722.6
   735.6   720.7   720.7   715.4   715.7   715.8   715.9   716.2   716.3   716.2
   716.2   716.3   716.5   716.5   716.6   716.7   716.8   716.8   716.9   717.1
   717.3   717.4   717.5   717.7   717.6   717.7   717.8   718.1   718.2   718.1
   718.2   718.2   718.4   718.7   718.8   723.8   722.6
Pier Skew, UpSta & Num, DnSta & Num=  ,2725.1, 2 ,2725.1, 2 , 0 , 0 , 0 ,,
    10.5       6
   692.2   716.3
    10.5       6
   692.2   716.3
Pier Skew, UpSta & Num, DnSta & Num=  ,2852.6, 2 ,2852.6, 2 , 0 , 0 , 0 ,,
    11.8     8.8
     695   716.8
    11.8     8.8
     695   716.8
Pier Skew, UpSta & Num, DnSta & Num=  ,2977.7, 2 ,2977.7, 2 , 0 , 0 , 0 ,,
    16.4    10.6
   698.2   717.7
    16.4    10.6
   698.2   717.7
Pier Skew, UpSta & Num, DnSta & Num=  ,3083.7, 2 ,3083.7, 2 , 0 , 0 , 0 ,,
    11.7     5.9
   691.1   718.2
    11.7     5.9
   691.1   718.2
BR Coef=-1 , 0 , 0 ,, 0 ,,,0.8,-1,,0,
WSPro=,,,, 1 ,,,, 0 ,,,, 0 ,,,,-1 ,-1 ,-1 , 0 , 0 , 0 , 0 , 0
BC Design=,, 0 ,, 0 ,,,,,,
BC HTab HWMax=771.1
BC Use User HTab Curves=0
BC User HTab FreeFlow(D)= 0

Type RM Length L Ch R = 1 ,247.2   ,47.52,47.52,47.52
BEGIN DESCRIPTION:
Penn Central Railroad Bridge Crossing #1 - Downstream Section
END DESCRIPTION:
#Sta/Elev= 30
     9.5   771.1   241.1   765.5     442   757.8   500.7   757.8   711.7   747.5
   987.6   737.7  1157.8   727.7  1368.2   726.1  1423.7   720.9  1535.4     721
    1543   742.7  2065.9   742.7  2079.5   735.9  2361.2   735.6  2375.4   720.7
  2557.6   720.7    2604   706.7  2626.2   706.2  2671.9   694.1  2730.5   692.2
  2799.6   697.2  2913.3   692.3  2969.6   699.4  3042.2   687.7  3089.1   692.6
  3099.6   696.7  3145.4   697.7  3185.2   714.9  3192.2   723.8  3240.3   722.6
#Mann= 3 , 0 , 0
     9.5    .038       0  2557.6    .035       0  3192.2    .038       0
#XS Ineff= 2 , 0
       0    2350                       0
Permanent Ineff=
       T       F
#Block Obstruct= 2 , 0
                          3240.3
Bank Sta=2557.6,3192.2
XS Rating Curve= 0 ,0
Exp/Cntr=0.5,0.3

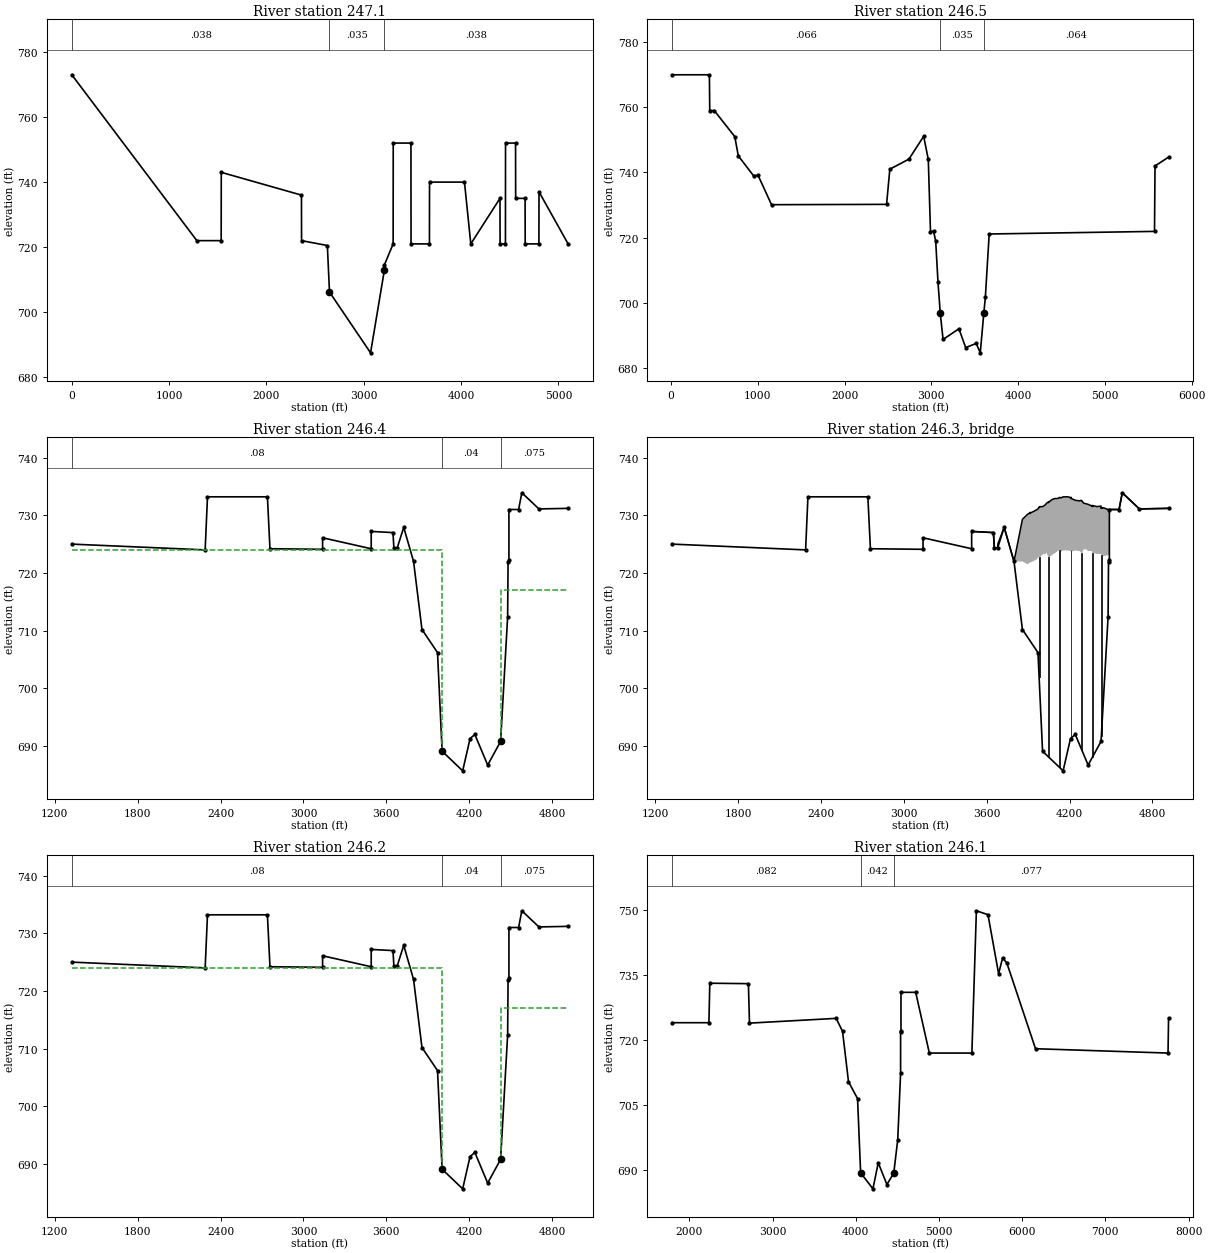
Type RM Length L Ch R = 1 ,247.1   ,1112.24,1112.24,1112.24
#Sta/Elev= 30
       0     773    1285     722    1535     722    1536     743    2360     736
    2361     722    2626   720.5    2648   706.2    3070   687.5    3213   713.1
    3213   714.6    3302     721    3303     752    3485     752    3486     721
    3675     721    3676     740    4035     740    4100     721    4400     735
    4401     721    4456     721    4457     752    4560     752    4561     735
    4658     735    4659     721    4800     721    4801     737    5100     721
#Mann= 3 , 0 , 0
       0    .038       0    2648    .035       0    3213    .038       0
#XS Ineff= 2 , 0
       0    2350                       0
Permanent Ineff=
       T       F
#Block Obstruct= 2 , 0
                            3257
Bank Sta=2648,3213
XS Rating Curve= 0 ,0
Exp/Cntr=0.5,0.3

Type RM Length L Ch R = 1 ,246.5   ,95.04,95.04,95.04
#Sta/Elev= 30
    14.6     770   442.8     770   446.7     759   499.4     759   735.3     751
   775.8   745.1   951.2     739    1004   739.1  1158.6   730.1  2484.4   730.2
  2521.9     741  2742.1   744.1  2911.9   751.1  2965.1     744  2990.5   721.8
  3025.6     722  3050.4   718.9  3076.7   706.4  3103.3   696.7  3135.4   688.7
  3318.1     692  3396.1   686.2  3517.2   687.5  3564.1   684.6  3604.9   696.8
  3622.5   701.6  3666.9   721.1  5571.9   721.9  5577.7     742  5733.7   744.7
#Mann= 3 , 0 , 0
    14.6    .066       0  3103.3    .035       0  3604.9    .064       0
#Block Obstruct= 2 , 0
                            3800
Bank Sta=3103.3,3604.9
XS Rating Curve= 0 ,0
Exp/Cntr=0.3,0.1

Type RM Length L Ch R = 1 ,246.4   ,301.5,301.5,301.5
BEGIN DESCRIPTION:
REPEATED section.  I-70 East/West Bridge - Upstream Section
END DESCRIPTION:
#Sta/Elev= 30
  1323.1     725  2288.7     724  2305.5   733.2  2739.4   733.2  2757.9   724.2
  3138.9   724.1  3138.9   726.1  3490.9   724.2  3490.9   727.2  3648.5     727
  3655.2   724.3  3678.6   724.3  3726.3   727.9  3797.5     722  3858.4   710.2
    3971   706.2  4004.3   689.1  4153.2   685.7  4206.6   691.3  4241.4     692
  4334.1   686.7  4427.7   690.8  4478.7   712.4  4481.8   721.9    4488   722.2
    4488     731    4558     731  4581.5   733.9  4705.3   731.1  4916.5   731.2
#Mann= 3 , 0 , 0
  1323.1     .08       0  4004.3     .04       0  4427.7    .075       0
#XS Ineff= 2 , 0
          4004.3     724  4427.7             717
Permanent Ineff=
       F       F
#Block Obstruct= 2 , 0
                            4600
Bank Sta=4004.3,4427.7
XS Rating Curve= 0 ,0
Exp/Cntr=0.3,0.1

Type RM Length L Ch R = 3 ,246.3   ,,,
BEGIN DESCRIPTION:
Structure #5 Interstate 70/71 Bridge
END DESCRIPTION:
Bridge Culvert--1,0,-1,-1, 0
Deck Dist Width WeirC Skew NumUp NumDn MinLoCord MaxHiCord MaxSubmerge Is_Ogee
1,300,2.6,0, 69, 69, 735, , 0.95, 0, 0,0,,
  3490.9  3648.5  3655.2  3678.6  3679.9  3726.3  3797.5  3858.4  3896.5    3912
    3912  3915.9  3916.8  3957.8    3971  3976.4  3977.2  3981.1  3983.4  3988.8
  4004.3  4023.7  4033.8  4044.7  4044.7  4047.8  4050.9  4071.1  4091.2    4109
  4122.2    4123  4127.6  4128.4  4136.9  4153.2  4187.3  4205.1  4206.6  4208.2
  4212.8  4212.8  4241.4  4272.3  4285.5  4286.3  4289.3  4289.4  4301.6  4318.7
  4334.1  4361.9  4361.9  4366.6  4366.6  4399.1  4427.7  4427.9  4432.3  4432.3
  4445.5  4478.7  4481.8    4488    4488    4558  4581.5  4705.3  4916.5
   727.2     727   724.3   724.3     725   727.9     722   729.3   730.2   730.4
   730.3   730.5   730.4   730.9   731.1   731.3   731.3   731.5   731.4   731.5
   731.5   731.8   732.1   732.3   732.2   732.2   732.3   732.7   732.9   732.9
     733     733   733.1   733.1     733   733.2   733.2   733.1     733   732.9
   733.1   732.9   732.6   732.5   732.6   732.5   732.5   732.5   732.1     732
   731.9   731.6   731.7   731.5   731.7   731.5   731.6   731.2   731.3   731.2
   731.3     731     731     731     731     731   733.9   731.1   731.2
   727.2     727   724.3   724.3     725   727.9     722     722   721.5   721.8
   721.8   721.9   721.8   722.3   722.6   722.8   722.7   722.8   722.7   722.8
   723.2   723.3   723.5   722.8     723   722.6   722.6   723.1   723.4   723.7
     724     724   723.9   723.9   723.7   723.9   723.9   723.8   723.8   723.8
   724.1   723.7   723.9   723.8   723.5   723.5   723.4   723.4   724.1   724.1
   723.8   723.8   723.7   723.3   723.5   723.3   723.3   723.1   723.3   723.2
   722.9   723.1   723.1   723.1     731     731   733.9   731.1   731.2
  3490.9  3648.5  3655.2  3678.6  3679.9  3726.3  3797.5  3858.4  3896.5    3912
    3912  3915.9  3916.8  3957.8    3971  3976.4  3977.2  3981.1  3983.4  3988.8
  4004.3  4023.7  4033.8  4044.7  4044.7  4047.8  4050.9  4071.1  4091.2    4109
  4122.2    4123  4127.6  4128.4  4136.9  4153.2  4187.3  4205.1  4206.6  4208.2
  4212.8  4212.8  4241.4  4272.3  4285.5  4286.3  4289.3  4289.4  4301.6  4318.7
  4334.1  4361.9  4361.9  4366.6  4366.6  4399.1  4427.7  4427.9  4432.3  4432.3
  4445.5  4478.7  4481.8    4488    4488    4558  4581.5  4705.3  4916.5
   727.2     727   724.3   724.3     725   727.9     722   729.3   730.2   730.4
   730.3   730.5   730.4   730.9   731.1   731.3   731.3   731.5   731.4   731.5
   731.5   731.8   732.1   732.3   732.2   732.2   732.3   732.7   732.9   732.9
     733     733   733.1   733.1     733   733.2   733.2   733.1     733   732.9
   733.1   732.9   732.6   732.5   732.6   732.5   732.5   732.5   732.1     732
   731.9   731.6   731.7   731.5   731.7   731.5   731.6   731.2   731.3   731.2
   731.3     731     731     731     731     731   733.9   731.1   731.2
   727.2     727   724.3   724.3     725   727.9     722     722   721.5   721.8
   721.8   721.9   721.8   722.3   722.6   722.8   722.7   722.8   722.7   722.8
   723.2   723.3   723.5   722.8     723   722.6   722.6   723.1   723.4   723.7
     724     724   723.9   723.9   723.7   723.9   723.9   723.8   723.8   723.8
   724.1   723.7   723.9   723.8   723.5   723.5   723.4   723.4   724.1   724.1
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Pier Skew, UpSta & Num, DnSta & Num=  ,3914, 2 ,3914, 2 , 0 , 0 , 0 ,,
     4.8     3.9
     702   721.9
     4.8     3.9
     702   721.9
Pier Skew, UpSta & Num, DnSta & Num=  ,3979.2, 2 ,3979.2, 2 , 0 , 0 , 0 ,,
       7     3.9
     691   722.8
       7     3.9
     691   722.8
Pier Skew, UpSta & Num, DnSta & Num=  ,4046.3, 2 ,4046.3, 2 , 0 , 0 , 0 ,,
     6.2     3.1
     689     723
     6.2     3.1
     689     723
Pier Skew, UpSta & Num, DnSta & Num=  ,4125.3, 2 ,4125.3, 2 , 0 , 0 , 0 ,,
     6.2     4.6
     686     724
     6.2     4.6
     686     724
Pier Skew, UpSta & Num, DnSta & Num=  ,4210.5, 2 ,4210.5, 2 , 0 , 0 , 0 ,,
     6.2     4.6
     678   724.1
     6.2     4.6
     678   724.1
Pier Skew, UpSta & Num, DnSta & Num=  ,4287.8, 2 ,4287.8, 2 , 0 , 0 , 0 ,,
     3.9       3
     678   723.5
     3.9       3
     678   723.5
Pier Skew, UpSta & Num, DnSta & Num=  ,4364.3, 2 ,4364.3, 2 , 0 , 0 , 0 ,,
     4.7     4.7
     678   723.7
     4.7     4.7
     678   723.7
Pier Skew, UpSta & Num, DnSta & Num=  ,4430.1, 2 ,4430.1, 2 , 0 , 0 , 0 ,,
     4.6     4.4
     679   723.3
     4.6     4.4
     679   723.3
BR Coef=-1 , 0 , 0 ,, 0 ,,,0.8,-1,,0,
WSPro=,,,, 1 ,,,, 0 ,,,, 0 ,,,,-1 ,-1 ,-1 , 0 , 0 , 0 , 0 , 0
BC Design=,, 0 ,, 0 ,,,,,,
BC HTab HWMax=733.9
BC Use User HTab Curves=0
BC User HTab FreeFlow(D)= 0

Type RM Length L Ch R = 1 ,246.2   ,95.04,95.04,95.04
BEGIN DESCRIPTION:
 I-70 East/West Bridge - Downstream Section
END DESCRIPTION:
#Sta/Elev= 30
  1323.1     725  2288.7     724  2305.5   733.2  2739.4   733.2  2757.9   724.2
  3138.9   724.1  3138.9   726.1  3490.9   724.2  3490.9   727.2  3648.5     727
  3655.2   724.3  3678.6   724.3  3726.3   727.9  3797.5     722  3858.4   710.2
    3971   706.2  4004.3   689.1  4153.2   685.7  4206.6   691.3  4241.4     692
  4334.1   686.7  4427.7   690.8  4478.7   712.4  4481.8   721.9    4488   722.2
    4488     731    4558     731  4581.5   733.9  4705.3   731.1  4916.5   731.2
#Mann= 3 , 0 , 0
  1323.1     .08       0  4004.3     .04       0  4427.7    .075       0
#XS Ineff= 2 , 0
          4004.3     724  4427.7             717
Permanent Ineff=
       F       F
#Block Obstruct= 2 , 0
                            5645
Bank Sta=4004.3,4427.7
XS Rating Curve= 0 ,0
Exp/Cntr=0.3,0.1

Type RM Length L Ch R = 1 ,246.1   ,1671.92,1671.92,1671.92
#Sta/Elev= 30
    1793     724  2233.9     724  2244.7   733.1  2708.8     733  2721.5   723.9
  3763.8     725  3840.6     722    3912   710.4    4021   706.5  4057.8   689.4
  4205.7   685.7  4269.7   691.7  4373.9   686.7    4456   689.3  4503.9     697
  4538.4   712.3  4538.5   722.1  4543.1   721.9  4543.1     731    4720     731
  4883.9     717  5395.4     717  5449.6   749.8  5588.9   748.9  5716.6   735.3
  5764.4   738.9  5815.2   737.8  6160.5     718  7753.8     717    7760     725
#Mann= 3 , 0 , 0
    1793    .082       0  4057.8    .042       0    4456    .077       0
#XS Ineff= 2 , 0
          4057.8   689.4    4456           689.3
Permanent Ineff=
       F       F
#Block Obstruct= 2 , 0
                            4710
Bank Sta=4057.8,4456
XS Rating Curve= 0 ,0
Exp/Cntr=0.3,0.1