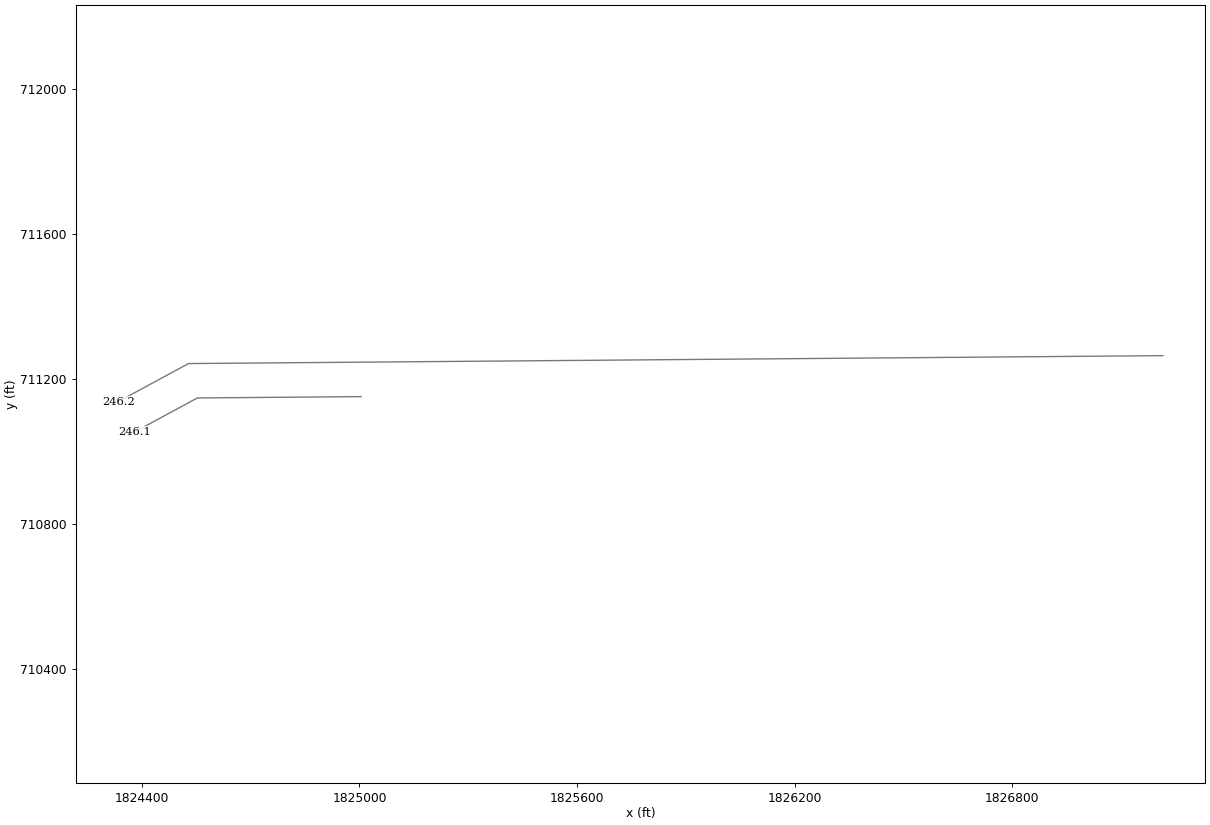
HEC-RAS study FRA-70-1321R.prj: FRA-70-1321R

--- FRA-70-1321R.g03 (geometry) --- (continued)

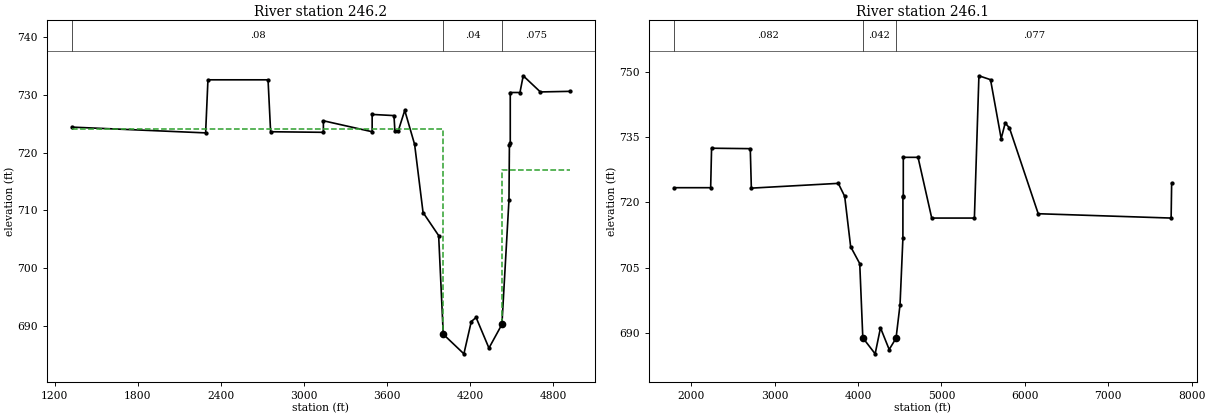
Type RM Length L Ch R = 1 ,246.2   ,95.04,95.04,95.04
BEGIN DESCRIPTION:
I-70 East/West Bridge - Downstream Section
END DESCRIPTION:
XS GIS Cut Line= 3
  1827215.061426  711264.8230698 1824528.7206707  711242.9838746
 1824335.0471736   711138.166499
#Sta/Elev= 30
  1323.1   724.4  2288.7   723.4  2305.5   732.6  2739.4   732.6  2757.9   723.6
  3138.9   723.5  3138.9   725.5  3490.9   723.6  3490.9   726.6  3648.5   726.4
  3655.2   723.7  3678.6   723.7  3726.3   727.3  3797.5   721.4  3858.4   709.6
    3971   705.6  4004.3   688.5  4153.2   685.1  4206.6   690.7  4241.4   691.4
  4334.1   686.1  4427.7   690.2  4478.7   711.8  4481.8   721.3    4488   721.6
    4488   730.4    4558   730.4  4581.5   733.3  4705.3   730.5  4916.5   730.6
#Mann= 3 , 0 , 0
  1323.1     .08       0  4004.3     .04       0  4427.7    .075       0
#XS Ineff= 2 , 0
       0  4004.3     724  4427.7       0     717
Permanent Ineff=
       F       F
#Block Obstruct= 2 , 0
                            5645
Bank Sta=4004.3,4427.7
XS Rating Curve= 0 ,0
Exp/Cntr=0.3,0.1

Type RM Length L Ch R = 1 ,246.1   ,1671.92,1671.92,1671.92
BEGIN DESCRIPTION:
Taken from effective Model
END DESCRIPTION:
XS GIS Cut Line= 3
  1825004.674115  711151.8501986 1824553.1402413  711148.1792742
 1824380.2642747  711054.6174535
#Sta/Elev= 30
    1793   723.4  2233.9   723.4  2244.7   732.5  2708.8   732.4  2721.5   723.3
  3763.8   724.4  3840.6   721.4    3912   709.8    4021   705.9  4057.8   688.8
  4205.7   685.1  4269.7   691.1  4373.9   686.1    4456   688.7  4503.9   696.4
  4538.4   711.7  4538.5   721.5  4543.1   721.3  4543.1   730.4    4720   730.4
  4883.9   716.4  5395.4   716.4  5449.6   749.2  5588.9   748.3  5716.6   734.7
  5764.4   738.3  5815.2   737.2  6160.5   717.4  7753.8   716.4    7760   724.4
#Mann= 3 , 0 , 0
    1793    .082       0  4057.8    .042       0    4456    .077       0
#XS Ineff= 2 , 0
          4057.8   688.8    4456           688.7
Permanent Ineff=
       F       F
#Block Obstruct= 2 , 0
                            4710
Bank Sta=4057.8,4456
XS Rating Curve= 0 ,0
Exp/Cntr=0.3,0.1

--- FRA-70-1321R.g04 (geometry) ---

Geom Title=Prpsd_Cndtn_3_Prfrrd_wo_dam_w_TAF
Program Version=4.10
BEGIN GEOM DESCRIPTION:
Vertical Datum = NAVD 88
Projection = State Plane Ohio South
END GEOM DESCRIPTION:

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
River Reach=SciotoRiver     ,SciotoRiver

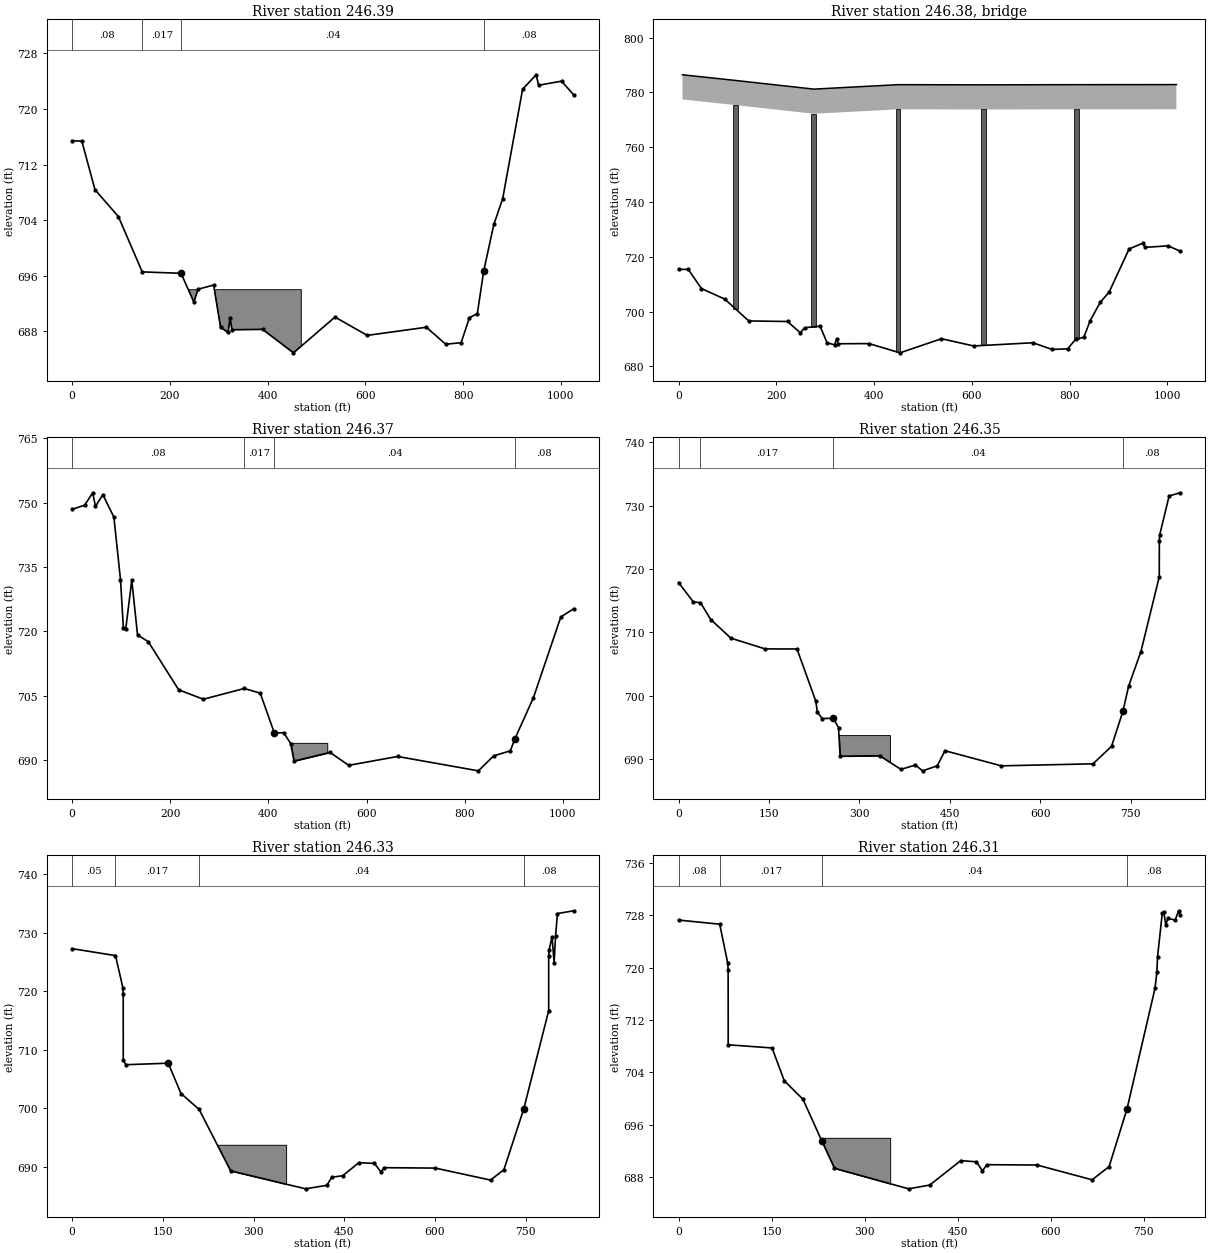
Type RM Length L Ch R = 1 ,246.39  ,65,113,110
XS GIS Cut Line= 6
      1825651.07       711942.18      1825563.07       711913.46
      1825121.78       711760.79      1824915.38       711693.74
       1824688.8       711625.07      1824434.68       711553.99
#Sta/Elev= 30
       0  715.42   19.96  715.36  46.921  708.38  94.743  704.52 143.617  696.56
  222.95  696.36 249.252  692.22 257.877  694.07  289.63  694.67 303.898  688.58
   319.3  687.85 323.279   689.9 327.138  688.24 389.854  688.29 453.046  684.92
 537.965  690.07 603.801  687.43 724.854   688.6 764.524  686.16   796.1  686.38
 812.908  689.97 829.194  690.57 842.289  696.71 862.964  703.39 881.027  707.08
 921.815  722.83 949.411  724.91 954.668  723.411001.477  723.991026.678     722
#Mann= 4 ,-1 , 0
       0     .08       0 143.617    .017       0  222.95     .04       0
 842.289     .08       0
#Block Obstruct= 2 , 0
       0     469     694  603.47       0     694
Bank Sta=222.95,842.289
XS Rating Curve= 0 ,0
Skew Angle= 36.5
Exp/Cntr=0.3,0.1

Type RM Length L Ch R = 3 ,246.38  ,,,
BEGIN DESCRIPTION:
FRA-71-1503L FRA-71-SB
END DESCRIPTION:
Bridge Culvert--1,0,-1,-1, 0
Deck Dist Width WeirC Skew NumUp NumDn MinLoCord MaxHiCord MaxSubmerge Is_Ogee
1,109.5,2.6,36.5, 7, 7, , , 0.98, 0, 0,0,,
   8.033 116.043 276.814 448.985 623.473  813.821018.628
  786.41 784.353781.1778 782.801 782.738 782.801 782.829
  777.41 775.353772.1778 773.801 773.738 773.801 773.829
   8.045   166.6 327.372 500.092 678.103 877.1071014.403
  783.71 782.498 780.225 777.985 777.566779.2638781.5989
  774.71 773.498 771.225 768.985 768.566770.2639772.5989
Pier Skew, UpSta & Num, DnSta & Num=  ,116.043, 6 ,166.6, 6 , 0 , 0 , 0 ,,
      10      10      10      10       8       8
     650     693   695.2   700.2   700.2 775.353
      10      10      10      10       8       8
     650     693   695.2   700.2   700.2 773.498
Pier Skew, UpSta & Num, DnSta & Num=  ,276.814, 6 ,327.372, 6 , 0 , 0 , 0 ,,
      10      10      10      10       8       8
     650     693   695.2   700.2   700.2 772.178
      10      10      10      10       8       8
     650     693   695.2   700.2   700.2 771.225
Pier Skew, UpSta & Num, DnSta & Num=  ,448.985, 6 ,500.092, 6 , 0 , 0 , 0 ,,
      10      10      10      10       8       8
     650     693   695.2   700.2   700.2 773.801
      10      10      10      10       8       8
     650     693   695.2   700.2   700.2 768.985
Pier Skew, UpSta & Num, DnSta & Num=  ,623.473, 6 ,678.103, 6 , 0 , 0 , 0 ,,
      10      10      10      10       8       8
     650     693   695.2   700.2   700.2 773.738
      10      10      10      10       8       8
     650     693   695.2   700.2   700.2 768.566
Pier Skew, UpSta & Num, DnSta & Num=  ,813.82, 6 ,877.107, 6 , 0 , 0 , 0 ,,
      10      10      10      10       8       8
     650     693   695.2   700.2   700.2 773.801
      10      10      10      10       8       8
     650     693   695.2   700.2   700.2 770.264
BR Coef=-1 , 0 , 0 ,, 0 ,,,0.8,-1,,0,
WSPro=,,,, 1 ,,,, 0 ,,,, 0 ,,,,-1 ,-1 ,-1 , 0 , 0 , 0 , 0 , 0
BC Design=,, 0 ,, 0 ,,,,,,
BC Use User HTab Curves=0
BC User HTab FreeFlow(D)= 0

Type RM Length L Ch R = 1 ,246.37  ,25,79,66
XS GIS Cut Line= 6
      1825670.41       711880.14       1825573.3       711848.23
       1824747.1       711560.98      1824589.71       711502.83
       1824517.5       711472.18      1824473.41       711451.37
#Sta/Elev= 30
       0  748.46  25.699  749.43  41.961  752.32  47.717  749.15  62.741  751.88
  85.185  746.65  98.681  732.08 104.542  720.79 109.389  720.57  121.64  731.96
   133.4  719.15 155.152  717.61 217.339  706.36 267.564  704.17  351.02  706.68
 383.391  705.58 412.186  696.29 431.277  696.37 445.634  693.79 452.202  689.75
 525.626  691.77 563.648  688.75 663.286  690.82 827.948  687.47 858.977  690.96
 892.924  692.13 902.249  694.92 940.038  704.53 995.898  723.371022.458  725.29
#Mann= 4 ,-1 , 0
       0     .08       0  351.02    .017       0 412.186     .04       0
 902.249     .08       0
#Block Obstruct= 2 , 0
       0     520     694     658       0     694
Bank Sta=412.186,902.249
XS Rating Curve= 0 ,0
Skew Angle= 36.5
Exp/Cntr=0.3,0.1

Type RM Length L Ch R = 1 ,246.35  ,76,89,68
XS GIS Cut Line= 6
      1825458.76       711781.91      1825331.26        711734.8
      1825027.19       711611.44      1824839.22       711536.51
      1824624.49       711454.18      1824449.47       711389.63
#Sta/Elev= 30
       0  717.86  24.534   714.8   36.42  714.68  53.519  712.01  86.895  709.07
 143.781  707.37 196.562  707.36 227.816   699.1 230.337  697.38 238.495  696.37
 256.947   696.4  265.45  694.93 268.126  690.41 333.808  690.49 369.106  688.33
 393.001  689.02 404.995   688.1 429.183  688.89 442.092  691.28 535.521  688.89
 687.698  689.21 718.498  691.97 737.465  697.54 746.891  701.51  767.22  706.95
 797.689  718.79 797.789  724.38 798.458  725.42 814.065  731.56 832.617  732.05
#Mann= 4 ,-1 , 0
       0     .08       0   36.42    .017       0 256.947     .04       0
 737.465     .08       0
#Block Obstruct= 2 , 0
       0  350.75  693.75  493.88       0  693.75
Bank Sta=256.947,737.465
XS Rating Curve= 0 ,0
Skew Angle= 39.75
Exp/Cntr=0.3,0.1

Type RM Length L Ch R = 1 ,246.33  ,1.5,5,21.5
XS GIS Cut Line= 6
      1825430.43       711711.43      1825366.18       711687.23
      1825025.53       711549.27      1824810.24       711464.05
      1824603.22       711385.38        1824425.       711320.09
#Sta/Elev= 30
       0  727.31  71.764  726.12  83.958  720.65  84.542  719.57  84.642   708.2
   89.04  707.45 158.981  707.71 180.117  702.52 210.071   699.8 262.106  689.29
 386.243  686.21 421.302  686.82 429.229  688.19 447.581  688.46 474.145  690.69
 499.924  690.56 510.511   689.1 516.123  689.83 600.542  689.76 691.819  687.71
 713.946  689.49 746.715  699.87 787.948  716.68 788.009  726.03 788.593  727.02
 793.506  729.35 796.935  724.92 799.311  729.45 802.471  733.32  829.58  733.79
#Mann= 4 ,-1 , 0
       0     .05       0  71.764    .017       0 210.071     .04       0
 746.715     .08       0
#Block Obstruct= 2 , 0
       0  353.87  693.75  496.37       0  693.75
Bank Sta=158.981,746.715
XS Rating Curve= 0 ,0
Skew Angle= 39.75
Exp/Cntr=0.3,0.1

Type RM Length L Ch R = 1 ,246.31  ,53,79.5,66
XS GIS Cut Line= 6
      1825427.66       711708.66      1825378.97       711690.29
      1825334.47       711673.05      1825289.29       711654.89
      1824490.33       711329.84      1824418.97       711299.53
#Sta/Elev= 30
       0  727.27  66.385  726.64  79.427  720.64  79.962  719.57  80.081  708.21
 150.762  707.73 170.448  702.72 200.575  699.89  230.91  693.53 251.428  689.34
 371.008   686.2  404.94  686.78 454.998  690.51  480.28  690.33 489.933  688.94
 496.986  689.89 577.996  689.84 666.705  687.58  694.12   689.6 723.058  698.44
 768.181  716.87 771.042  719.27 772.254   721.7 779.901  728.37 782.271  728.49
 785.534  726.55 789.004  727.56 800.538  727.25 806.223  728.69 808.943  727.99
#Mann= 4 ,-1 , 0
       0     .08       0  66.385    .017       0  230.91     .04       0
 723.058     .08       0
#Block Obstruct= 2 , 0
       0   341.2     694  479.26       0     694
Bank Sta=230.91,723.058
XS Rating Curve= 0 ,0
Skew Angle= 42
Exp/Cntr=0.3,0.1

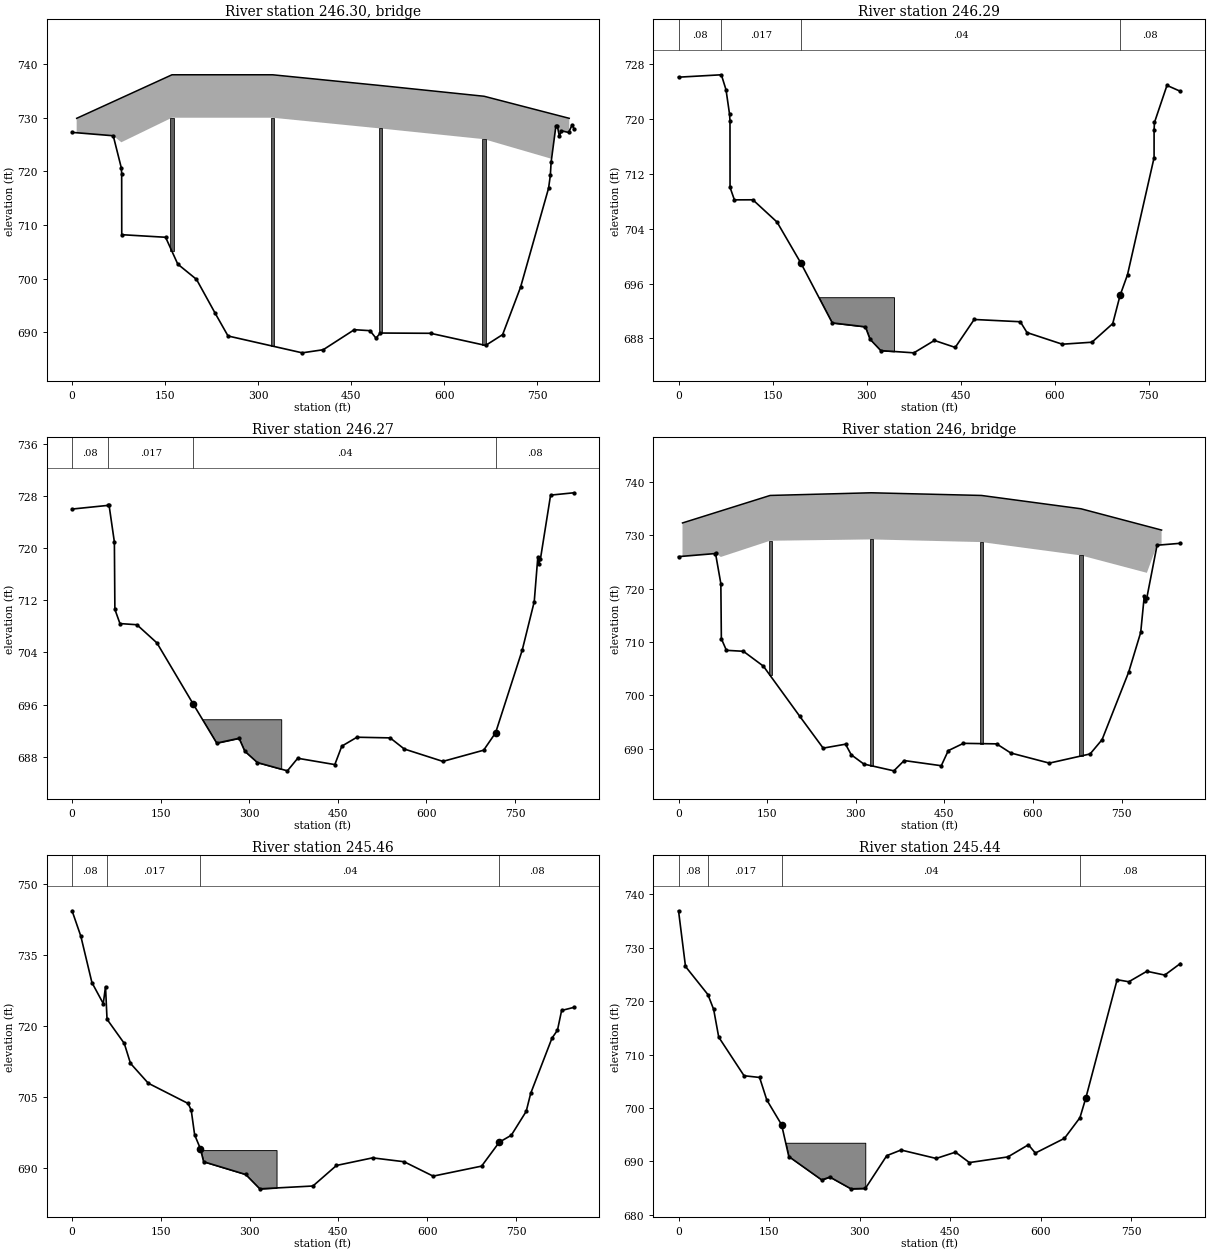
Type RM Length L Ch R = 3 ,246.30  ,,,
BEGIN DESCRIPTION:
FRA-70-1322L FRA-70-WB
END DESCRIPTION:
Bridge Culvert--1,0,-1,-1, 0
Deck Dist Width WeirC Skew NumUp NumDn MinLoCord MaxHiCord MaxSubmerge Is_Ogee
1,76.5,2.6,42, 6, 6, , , 0.98, 0, 0,0,,
   7.423 161.032 323.348 497.012 664.248 801.518
  729.89     738     738     736     734  729.89
  721.39     730     730     728     726  721.39
    7.44 163.496 325.811 499.475 660.804 792.804
  729.82     738     738     736     734  729.82
  721.32     730     730     728     726  721.32
Pier Skew, UpSta & Num, DnSta & Num=  ,161.032, 4 ,163.496, 4 , 0 , 0 , 0 ,,
     5.5     5.5       5       5
   649.5   697.2   697.2     730
     5.5     5.5       5       5
   649.5   697.2   697.2     730
Pier Skew, UpSta & Num, DnSta & Num=  ,323.348, 4 ,325.811, 4 , 0 , 0 , 0 ,,
     5.5     5.5       5       5
   648.5   697.2   697.2     730
     5.5     5.5       5       5
   648.5   697.2   697.2     730
Pier Skew, UpSta & Num, DnSta & Num=  ,497.012, 4 ,499.475, 4 , 0 , 0 , 0 ,,
     5.5     5.5       5       5
   649.5   697.2   697.2     728
     5.5     5.5       5       5
   649.5   697.2   697.2     728
Pier Skew, UpSta & Num, DnSta & Num=  ,664.248, 4 ,660.804, 4 , 0 , 0 , 0 ,,
     5.5     5.5       5       5
     645   697.2   697.2     726
     5.5     5.5       5       5
     645   697.2   697.2     726
BR Coef=-1 , 0 , 0 ,, 0 ,,,0.8,-1,,0,
WSPro=,,,, 1 ,,,, 0 ,,,, 0 ,,,,-1 ,-1 ,-1 , 0 , 0 , 0 , 0 , 0
BC Design=,, 0 ,, 0 ,,,,,,
BC Use User HTab Curves=0
BC User HTab FreeFlow(D)= 0

Type RM Length L Ch R = 1 ,246.29  ,6.5,42.5,56.5
XS GIS Cut Line= 6
      1825401.16       711642.22      1825312.85       711607.25
      1825197.97       711560.53      1824577.95       711308.34
      1824484.59       711269.97      1824404.37       711234.92
#Sta/Elev= 30
       0  726.12  68.288  726.47  75.726  724.28    81.3  720.75  82.043  719.78
  82.155  710.03  89.096  708.21 118.539  708.22 157.086  704.97 195.365  698.94
 245.163  690.25 297.964  689.68 305.351  687.87 322.495  686.21  375.31  685.88
 408.053  687.69  441.25  686.67 471.488  690.75 545.045  690.42 555.716  688.84
 611.957  687.14 659.273  687.43 692.455  690.15 704.145  694.26 716.013  697.29
 758.379  714.37 758.394  718.43 759.004  719.51 778.935  724.92 800.241  724.06
#Mann= 4 ,-1 , 0
       0     .08       0  68.288    .017       0 195.365     .04       0
 704.145     .08       0
#Block Obstruct= 2 , 0
       0  343.56     694  481.73       0     694
Bank Sta=195.365,704.145
XS Rating Curve= 0 ,0
Skew Angle= 42
Exp/Cntr=0.3,0.1

Type RM Length L Ch R = 1 ,246.27  ,88.5,142.5,181
XS GIS Cut Line= 6
       1825385.5       711629.15      1825247.29       711574.58
      1825192.54       711551.32      1824984.67        711455.9
      1824558.31       711249.13      1824359.14       711147.47
#Sta/Elev= 30
       0  726.02  61.377  726.59  62.613  726.63  71.638  720.95  72.491  710.62
  81.067  708.44 109.789  708.26  143.68  705.47 204.997   696.1 244.856  690.09
 282.731  690.83 292.422  688.84  313.76   687.1 364.569  685.83  382.02  687.76
 444.842  686.79 456.668  689.62 482.268  690.99 538.507  690.89 562.466  689.18
 627.775  687.28 696.813     689 717.065  691.68 762.152  704.37 782.456   711.8
 788.538  718.66 790.096  717.65 792.927  718.34 810.145  728.16 849.541  728.52
#Mann= 4 ,-1 , 0
       0     .08       0  61.377    .017       0 204.997     .04       0
 717.065     .08       0
#Block Obstruct= 2 , 0
       0  354.07  693.75  495.13       0  693.75
Bank Sta=204.997,717.065
XS Rating Curve= 0 ,0
Skew Angle= 41.5
Exp/Cntr=0.3,0.1

Type RM Length L Ch R = 3 ,246     ,,,
BEGIN DESCRIPTION:
FRA-70-1321R RC4
END DESCRIPTION:
Bridge Culvert--1,0,-1,-1, 0
Deck Dist Width WeirC Skew NumUp NumDn MinLoCord MaxHiCord MaxSubmerge Is_Ogee
1,139.5,2.6,41.5, 6, 6, , , 0.98, 0, 0,0,,
   6.704 155.066 326.324 512.877 681.391 817.808
 732.342   737.5     738   737.5     735 731.005
 723.592     729  729.25  728.75  726.25 722.255
    .757  152.64  327.74 508.595 680.981 836.084
 728.656   738.5  737.75   737.5   731.5 728.259
 719.906  727.75     729  727.75  723.25 719.509
Pier Skew, UpSta & Num, DnSta & Num=  ,155.066, 4 ,152.64, 4 , 0 , 0 , 0 ,,
     5.5     5.5       5       5
   652.2   697.2   697.2     729
     5.5     5.5       5       5
   652.2   697.2   697.2  727.75
Pier Skew, UpSta & Num, DnSta & Num=  ,326.324, 4 ,327.74, 4 , 0 , 0 , 0 ,,
     5.5     5.5       5       5
     649   697.2   697.2  729.25
     5.5     5.5       5       5
     649   697.2   697.2     729
Pier Skew, UpSta & Num, DnSta & Num=  ,512.877, 4 ,508.596, 4 , 0 , 0 , 0 ,,
     5.5     5.5       5       5
   647.5   697.2   697.2  728.75
     5.5     5.5       5       5
   647.5   697.2   697.2  727.75
Pier Skew, UpSta & Num, DnSta & Num=  ,681.39, 4 ,680.981, 4 , 0 , 0 , 0 ,,
     5.5     5.5       5       5
     644   697.2   697.2  726.25
     5.5     5.5       5       5
     644   697.2   697.2  723.25
BR Coef=-1 , 0 , 0 ,, 0 ,,,0.8,-1,,0,
WSPro=,,,, 1 ,,,, 0 ,,,, 0 ,,,,-1 ,-1 ,-1 , 0 , 0 , 0 , 0 , 0
BC Design=,, 0 ,, 0 ,,,,,,
BC Use User HTab Curves=0
BC User HTab FreeFlow(D)= 0

Type RM Length L Ch R = 1 ,245.46  ,37.5,93.5,6.5
XS GIS Cut Line= 6
      1825330.07       711512.21      1825008.91       711368.39
      1824651.57        711182.4      1824589.22       711147.61
      1824473.59       711072.51      1824342.96       710967.15
#Sta/Elev= 30
       0  744.42  14.777  739.05  33.546  729.22  52.719  724.77  56.509  728.37
  59.078  721.45  88.212  716.34   98.72  712.11  128.76  707.91 196.122  703.62
 201.334   702.2 207.109  696.98 216.755  694.07 222.245  691.29 293.366  688.59
 317.175  685.55 406.983  686.15 446.767   690.5 507.807  692.11  560.96  691.29
 610.092  688.24 691.983  690.36 721.881  695.43 742.118  696.89 767.328  701.95
 774.915  705.76 810.894  717.46 820.151  719.13 827.162  723.31 847.855  723.97
#Mann= 4 ,-1 , 0
       0     .08       0  59.078    .017       0 216.755     .04       0
 721.881     .08       0
#Block Obstruct= 2 , 0
       0  345.49  693.75  490.85       0  693.75
Bank Sta=216.755,721.881
XS Rating Curve= 0 ,0
Skew Angle= 41.5
Exp/Cntr=0.3,0.1

Type RM Length L Ch R = 1 ,245.44  ,92.7,87.5,178.2
XS GIS Cut Line= 6
      1825257.45       711441.41       1824686.9       711126.91
      1824476.62       711015.64      1824341.26        710959.8
      1824278.08        710941.9      1824205.35       710928.08
#Sta/Elev= 30
       0  736.94  11.533  726.51  48.642  721.25  58.195  718.47  66.574  713.28
 108.541  706.05 134.273  705.73 146.187  701.52 170.759  696.87 182.667  690.92
 237.157  686.54 250.676  687.08 285.706  684.87 309.536  684.95 345.012  691.09
 368.636  692.14 426.852  690.56 458.799  691.74 481.893  689.79 545.632  690.85
 579.637  693.12 591.155  691.57 639.387  694.33 664.999  698.19 674.891  701.94
 726.588  724.03 745.962  723.65 775.845  725.61 805.515   724.9  831.31  727.06
#Mann= 4 ,-1 , 0
       0     .08       0  48.642    .017       0 170.759     .04       0
 664.999     .08       0
#Block Obstruct= 2 , 0
       0  309.36   693.5  442.36       0   693.5
Bank Sta=170.759,674.891
XS Rating Curve= 0 ,0
Skew Angle= 45
Exp/Cntr=0.3,0.1

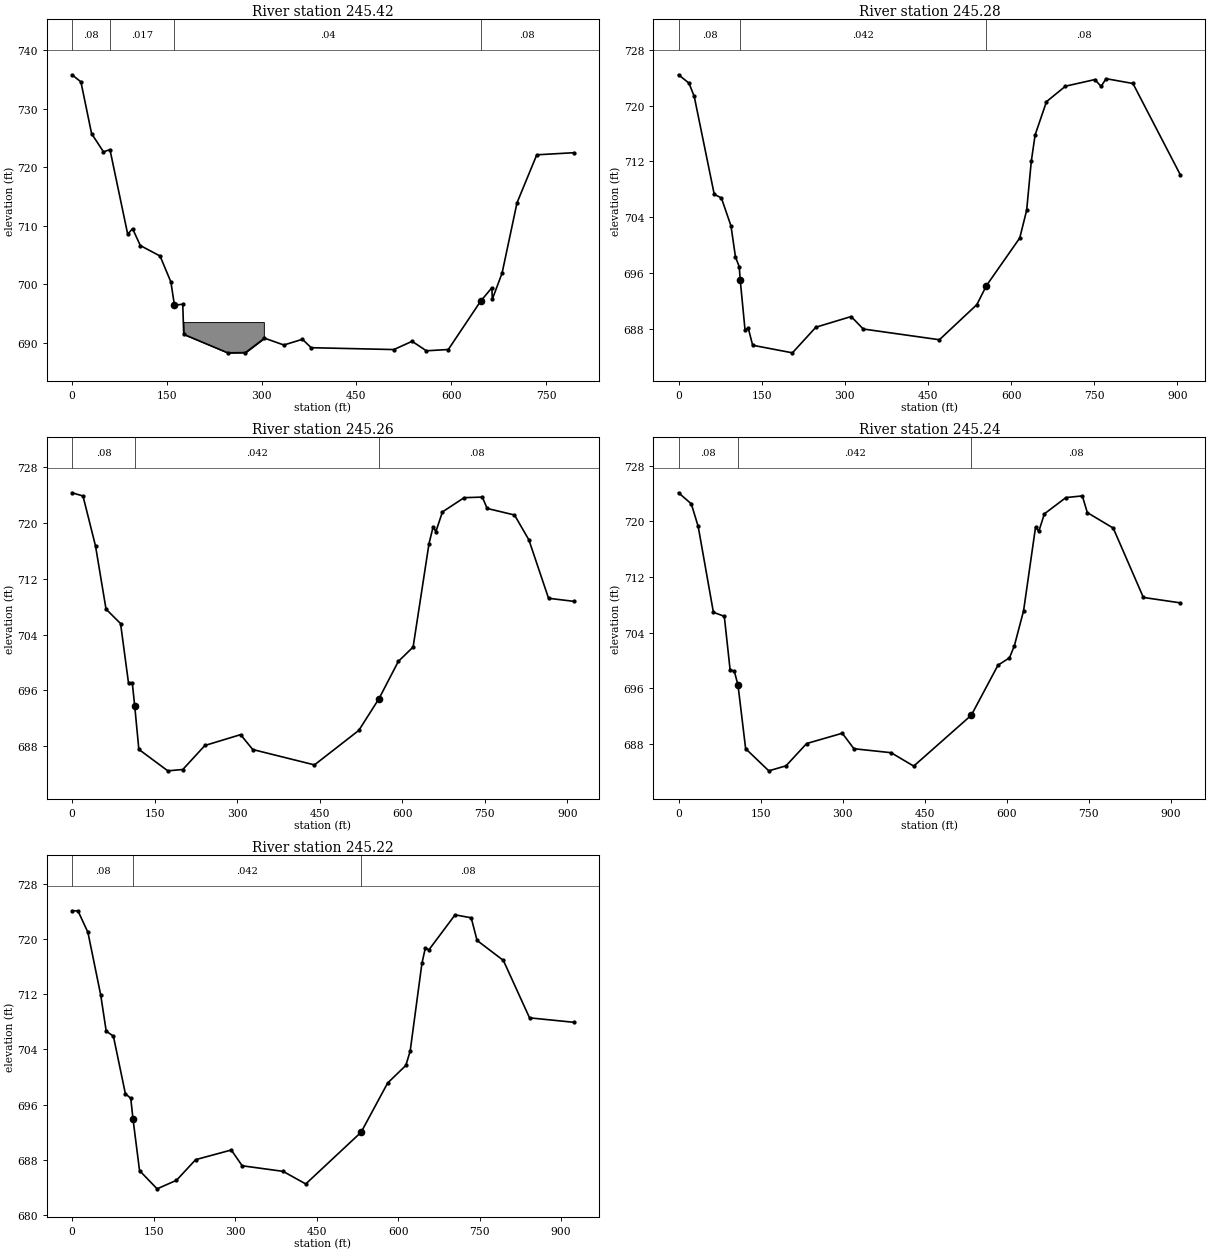
Type RM Length L Ch R = 1 ,245.42  ,755.6,402.5,22.2
XS GIS Cut Line= 6
      1825222.91       711355.31      1824672.33       711048.11
      1824492.65       710940.63       1824369.1       710857.66
      1824318.29       710813.84      1824273.83       710763.52
#Sta/Elev= 30
       0   735.8  14.029  734.58  30.893  725.73  49.717  722.62  59.956     723
  88.063  708.52  95.707  709.49 108.003  706.59 139.251   704.8  156.37  700.36
 162.019  696.38 175.157  696.56 176.692   691.4 246.391  688.24 274.421  688.28
 304.501  690.75 335.204  689.58 364.605  690.56  378.33  689.12 509.188   688.8
 538.094  690.21 560.665  688.59 595.391  688.81 646.515  697.07 664.362  699.38
 664.977   697.4  680.47  701.87 704.102   713.9 735.377  722.11 794.067  722.47
#Mann= 4 ,-1 , 0
       0     .08       0  59.956    .017       0 162.019     .04       0
 646.515     .08       0
#Block Obstruct= 2 , 0
       0   303.5   693.5   428.7       0   693.5
Bank Sta=162.019,646.515
XS Rating Curve= 0 ,0
Skew Angle= 45
Exp/Cntr=0.3,0.1

Type RM Length L Ch R = 1 ,245.28  ,18.5,18.5,31.5
XS GIS Cut Line= 4
      1824962.49       710516.15      1824633.18       710547.14
      1824309.49       710577.61      1824072.24        710654.7
#Sta/Elev= 30
       0  724.44   18.86  723.24   28.31  721.33   64.42  707.28    77.3  706.76
   94.65  702.74  102.72  698.29  109.52  696.88  111.34  694.94  119.97  687.81
  125.84  688.05  133.72  685.61  205.49  684.52   247.8   688.2  311.45  689.73
  333.33  687.94  470.66   686.4  538.22  691.44  555.51  694.17  615.59     701
   628.1  704.99  636.43     712  643.33   715.8  663.87  720.58  698.06   722.8
  751.11  723.75  762.39  722.77  771.42  723.88  819.85  723.19  905.35  710.08
#Mann= 3 ,-1 , 0
       0     .08       0  111.34    .042       0  555.51     .08       0
Bank Sta=111.34,555.51
XS Rating Curve= 0 ,0
Exp/Cntr=0.3,0.1

Type RM Length L Ch R = 1 ,245.26  ,18.5,18.5,31.5
XS GIS Cut Line= 4
      1824958.46       710497.65      1824631.42       710528.43
      1824307.58       710558.91       1824058.6       710626.41
#Sta/Elev= 30
       0  724.29   19.84  723.83   42.65  716.66   61.69  707.64   88.12  705.57
  102.54  697.06  109.38  697.11  113.82  693.77  121.35  687.56  173.95  684.49
  201.17  684.68  241.33  688.12  306.21  689.67  328.27  687.54  440.42  685.34
  521.02  690.28  557.73  694.83  592.76  700.15  619.66  702.21  648.56  717.02
  656.13  719.44  660.95  718.72  672.95  721.55  712.38  723.59  745.46  723.67
  754.14  722.05  803.87  721.11  830.01  717.55  865.74  709.19  911.73  708.75
#Mann= 3 ,-1 , 0
       0     .08       0  113.82    .042       0  557.73     .08       0
Bank Sta=113.82,557.73
XS Rating Curve= 0 ,0
Exp/Cntr=0.3,0.1

Type RM Length L Ch R = 1 ,245.24  ,18.5,18.5,23
XS GIS Cut Line= 4
      1824954.51       710479.49      1824629.69       710510.07
       1824305.4       710540.59      1824045.85       710597.34
#Sta/Elev= 30
       0  724.13   23.31  722.54   35.95  719.28   63.74  706.94    83.7  706.35
   94.31  698.66     102  698.45  108.73  696.47  122.71  687.31  165.08  684.12
  196.54  684.84  234.25  688.05  299.47  689.53  320.78   687.3  388.68  686.73
  430.12   684.8  535.48  692.13  584.17  699.32  605.23  700.38  614.25  702.14
  631.03  707.16  652.93  719.21  658.81  718.58  669.09   721.1   708.4  723.44
  738.49  723.68  747.52  721.28  794.95  719.05  850.07  709.07  917.66  708.29
#Mann= 3 ,-1 , 0
       0     .08       0  108.73    .042       0  535.48     .08       0
Bank Sta=108.73,535.48
XS Rating Curve= 0 ,0
Exp/Cntr=0.3,0.1

Type RM Length L Ch R = 1 ,245.22  ,785,973.5,1273
XS GIS Cut Line= 4
      1824950.77       710461.49      1824627.98       710491.87
      1824303.25       710522.44      1824034.03       710567.49
#Sta/Elev= 30
       0  724.14   10.85  724.13   29.15  721.01   52.74  711.89   62.81  706.66
   76.04  705.93   98.09  697.57  107.96   696.9  112.19  693.85  124.16   686.4
  156.47  683.75  192.13  684.99  227.41  687.99  292.96  689.39  313.07   687.1
  388.24  686.29  430.02  684.46  531.83  691.97  580.69  699.12   614.2  701.68
  622.15  703.76  643.75  716.49  650.14  718.77  656.46  718.45  704.77  723.55
  734.47  723.12  745.24  719.83  793.63  716.93  841.78  708.59  923.35  707.94
#Mann= 3 ,-1 , 0
       0     .08       0  112.19    .042       0  531.83     .08       0
Bank Sta=112.19,531.83
XS Rating Curve= 0 ,0
Exp/Cntr=0.3,0.1

--- FRA-70-1321R.g05 (geometry) ---

Geom Title=Corrected Effective / PreProject_Stantec
Program Version=4.10
BEGIN GEOM DESCRIPTION:
Vertical Datum = NAVD 88
Projection = State Plane Ohio South
END GEOM DESCRIPTION:

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
River Reach=SciotoRiver     ,SciotoRiver

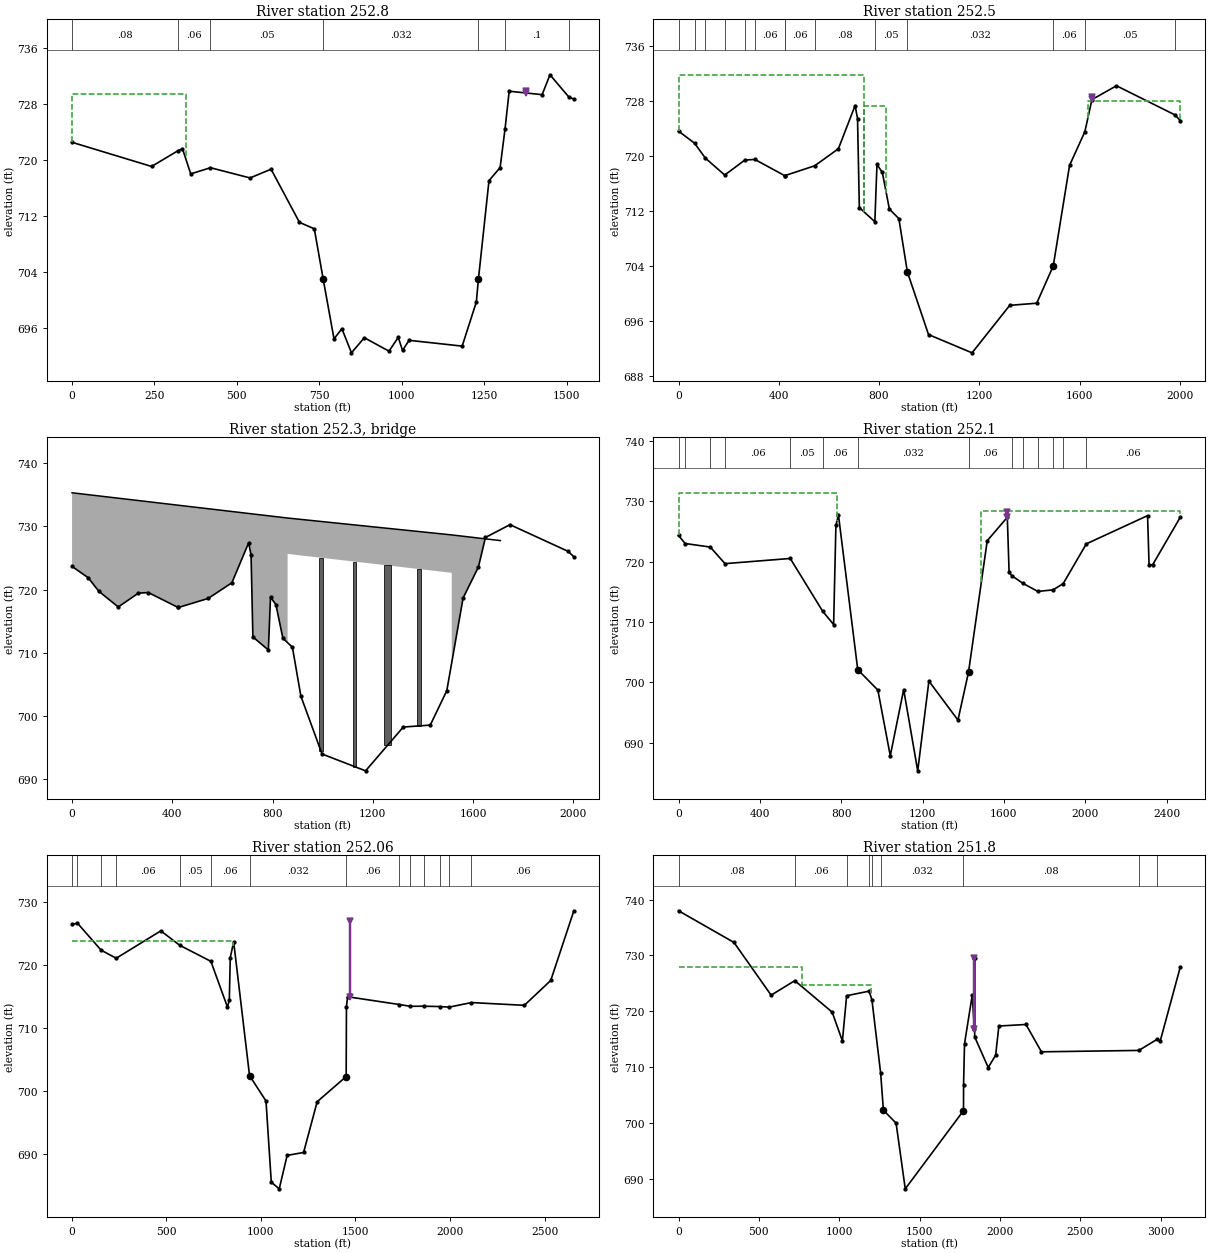
Type RM Length L Ch R = 1 ,252.8   ,816.3,590.47,312.21
BEGIN DESCRIPTION:
Overbank geometry from 2011 City of Columbus LiDAR data.  Channel geometry from 2011 hydrographic survey by Resource International.
END DESCRIPTION:
XS GIS Cut Line= 3
1825059.28161752716827.0005937671825102.24511428715305.381917849
 1825102.2453968715305.371912071
#Sta/Elev= 30
       0  722.55  241.21   719.1  319.94  721.31  334.94  721.64  359.94  718.04
  419.93  718.92   539.9  717.46  603.64  718.71  689.87  711.11  734.87  710.19
  761.84  702.99  794.59  694.47  818.58  695.91  847.56  692.47  886.54  694.63
   961.5  692.71  989.49  694.68 1002.48  692.82 1022.47  694.26 1183.39  693.43
 1226.37  699.73 1232.69  702.99 1264.77  717.07 1298.52  718.94 1313.51  724.49
 1326.01  729.85    1426  729.36 1449.74   732.2 1507.23  729.01 1522.23  728.73
#Mann= 7 ,-1 , 0
       0     .08       0  319.94     .06       0  419.93     .05       0
  761.84    .032       0 1232.69     .04       0 1313.51      .1       0
 1507.23     .05       0
Levee=0,,,-1,1377,729.9,,
#XS Ineff= 2 , 0
       0   344.3   729.5               0
Permanent Ineff=
       F       F
Bank Sta=761.84,1232.69
XS Rating Curve= 0 ,0
Exp/Cntr=0.5,0.3

Type RM Length L Ch R = 1 ,252.5   ,194.58,195.03,226.52
BEGIN DESCRIPTION:
Overbank geometry from 2011 City of Columbus LiDAR data.  Channel geometry from 2011 hydrographic survey by Resource International.
END DESCRIPTION:
Node Name=AK
XS GIS Cut Line= 3
   1826550.36066   716753.121805   1825271.62404   715427.642828
   1825112.98591   715273.159541
#Sta/Elev= 30
       0  723.64  64.253  721.87 106.693  719.72 184.279  717.24 264.299  719.42
 304.304  719.52 423.116  717.16  424.33  717.16 543.142  718.59 637.707  721.07
 704.396  727.37  714.09  725.47 721.366   712.5 783.194  710.44 791.664  718.78
 813.002  717.63  841.14  712.29 878.981  710.89 912.932  703.13 997.338     694
1170.992  691.341321.359  698.261429.042  698.571495.012  704.011560.013  718.65
1621.132  723.561649.261  728.231747.066  730.25 1980.19  726.012001.924  725.17
#Mann= 14 ,-1 , 0
       0     .08       0  64.253     .06       0 106.693     .08       0
 184.279     .06       0 264.299     .05       0 304.304     .06       0
 423.116     .05       0  424.33     .06       0 543.142     .08       0
 783.194     .05       0 912.932    .032       01495.012     .06       0
1621.132     .05       0 1980.19     .06       0
Levee=0,,,-1,1650.25,728.6,,
#XS Ineff= 3 ,-1
       0  741.41  731.85  741.41 828.637  727.371633.2652132.122  728.08
Permanent Ineff=
       F       F       F
Bank Sta=912.932,1495.012
XS Rating Curve= 0 ,0
Skew Angle= 14
Exp/Cntr=0.5,0.3

Type RM Length L Ch R = 3 ,252.3   ,,,
BEGIN DESCRIPTION:
Norfolk Southern Railroad Bridge
Geometry from plans provided by Norfolk Southern.  Top chord elevations adjusted using 2011 City of Columbus LiDAR data.
END DESCRIPTION:
Bridge Culvert--1,0,-1,-1, 0
Deck Dist Width WeirC Skew NumUp NumDn MinLoCord MaxHiCord MaxSubmerge Is_Ogee
118,29.5,2.6,14, 6, 8, , , 0.98, 0, 0,0,,
       0 859.866 859.8661514.8161514.8161708.876
  735.29   731.3   731.3  728.63  728.63  727.73
             680  725.63  722.64     680
-196.762  57.429 810.789 810.7891457.6341457.6342084.1262321.029
  736.03  734.84   731.3   731.3  728.63  728.63  725.69  724.58
                     680  725.63  722.64     680
Pier Skew= 14
Pier Skew, UpSta & Num, DnSta & Num=  ,993.282, 2 ,953.644, 2 , 0 , 0 , 0 ,,
    14.9   11.98
     690   725.2
    14.9   11.98
     690   725.2
Pier Skew, UpSta & Num, DnSta & Num=  ,1126.696, 2 ,1087.057, 2 , 0 , 0 , 0 ,,
    14.9   11.98
     690  724.55
    14.9   11.98
     690  724.55
Pier Skew, UpSta & Num, DnSta & Num=  ,1260.113, 5 ,1220.474, 5 , 0 , 0 , 0 ,,
   28.48   28.48   16.84   16.12   12.96
     690  704.84  706.67  721.32  724.02
   28.48   28.48   16.84   16.12   12.96
     690  704.84  706.67  721.32  724.02
Pier Skew, UpSta & Num, DnSta & Num=  ,1383.825, 2 ,1344.185, 2 , 0 , 0 , 0 ,,
    14.9   11.98
     690  723.26
    14.9   11.98
     690  723.26
BR Coef=-1 , 1 , 1 ,1.25, 0 ,,,0.8,-1,2,1,
WSPro=,,,, 1 ,,,, 0 ,,,, 0 ,,,,-1 ,-1 ,-1 , 0 , 0 , 0 , 0 , 0
BC Design=,, 0 ,, 0 ,,,,,,
BC Use User HTab Curves=0
BC User HTab FreeFlow(D)= 0

Type RM Length L Ch R = 1 ,252.1   ,224.67,252.61,290.84
BEGIN DESCRIPTION:
Overbank geometry from 2011 City of Columbus LiDAR data.  Channel geometry from 2011 hydrographic survey by Resource International.
END DESCRIPTION:
XS GIS Cut Line= 6
   1826762.92421   716582.237304   1826292.09083   716142.654193
   1826143.30143   716056.178645   1825606.04922   715544.772187
   1824970.63252   714894.0428461824903.85249717714825.653519359
#Sta/Elev= 30
       0  724.35   32.46  723.02  156.04  722.43  228.45  719.68  549.27  720.54
  708.99  711.78  762.61  709.59  773.83  726.03  786.39  727.73  881.24  702.11
  980.17  698.72 1041.15  687.83 1107.13   698.81176.109  685.33 1231.09  700.21
 1374.05  693.74 1426.03  701.71 1518.03  723.49 1616.71  727.36 1625.45  718.29
 1637.95   717.7 1694.17   716.4 1766.63  715.08 1841.59  715.33 1891.57  716.37
 2005.26  722.96 2306.33  727.642313.821  719.49 2331.31  719.49 2467.48  727.39
#Mann= 14 ,-1 , 0
       0     .08       0   32.46     .06       0  156.04     .05       0
  228.45     .06       0  549.27     .05       0  708.99     .06       0
  881.24    .032       0 1426.03     .06       0 1637.95     .08       0
 1694.17     .06       0 1766.63     .08       0 1841.59     .06       0
 1891.57     .08       0 2005.26     .06       0
Levee=0,,,-1,1616.71,728.3,,
#XS Ineff= 2 , 0
       0  779.29  731.43 1489.13       0  728.47
Permanent Ineff=
       F       F
Bank Sta=881.24,1426.03
XS Rating Curve= 0 ,0
Exp/Cntr=0.5,0.3

Type RM Length L Ch R = 1 ,252.06  ,371.37,352.86,335.57
BEGIN DESCRIPTION:
Overbank geometry from 2011 City of Columbus LiDAR data.  Channel geometry from 2011 hydrographic survey by Resource International.
END DESCRIPTION:
XS GIS Cut Line= 5
   1826944.72995   716557.711762   1826205.14645   715813.961937
   1825680.14652   715222.295142   1825513.47986   715024.378543
    1825000.9799   714807.711981
#Sta/Elev= 30
    1.25  726.39   29.97  726.59  154.83  722.32  234.75  721.04  470.75  725.38
  570.64  723.09  735.46  720.55  822.87  713.32  832.86  714.37  837.85  721.13
   855.9  723.64  939.89  702.44 1026.88  698.43 1054.87  685.56 1096.82  684.51
 1138.77  689.81 1225.66  690.27 1297.57  698.31 1450.88   702.3 1452.38  713.36
 1458.37  714.94 1732.42  713.71  1789.9  713.43 1862.39  713.44 1944.88  713.39
 1996.13   713.3 2113.61  714.02 2393.07  713.58  2532.8  717.52 2655.07  728.56
#Mann= 14 ,-1 , 0
    1.25     .08       0   29.97     .06       0  154.83     .05       0
  234.75     .06       0  570.64     .05       0  735.46     .06       0
  939.89    .032       0 1450.88     .06       0 1732.42     .08       0
  1789.9     .06       0 1862.39     .08       0 1944.88     .06       0
 1996.13     .08       0 2113.61     .06       0
Levee=0,,,-1,1472.36,727,,
#XS Ineff= 2 , 0
       0   850.9  723.79               0
Permanent Ineff=
       F       F
Bank Sta=939.89,1450.88
XS Rating Curve= 0 ,0
Exp/Cntr=0.3,0.1

Type RM Length L Ch R = 1 ,251.8   ,433.64,366.02,306.26
BEGIN DESCRIPTION:
Overbank geometry from 2011 City of Columbus LiDAR data.  Channel geometry from 2011 hydrographic survey by Resource International.
END DESCRIPTION:
XS GIS Cut Line= 4
1827472.38998027716511.9359351841825733.71924503714878.126866847
1825008.25645711714749.1487783491825008.19732577714749.138265546
#Sta/Elev= 30
       0  738.01  344.94  732.34  576.16  722.89  723.63  725.49  956.09  719.85
 1019.83  714.68 1046.08  722.79 1186.06  723.61 1203.55  722.04 1257.91  708.89
 1274.91  702.28 1353.91  699.96  1410.9  688.19 1773.38   702.2 1773.88  706.88
 1779.71  714.18 1827.47  722.84    1841  716.85    1841  729.55    1843  729.55
    1843  715.41 1927.19  709.93 1973.43  712.13 1993.43  717.36 2162.15  717.64
 2258.38  712.74  2864.2  712.99  2976.6  714.95 2997.83   714.7 3122.73  727.96
#Mann= 9 ,-1 , 0
       0     .08       0  723.63     .06       0 1046.08     .08       0
 1186.06     .05       0 1203.55     .06       0 1257.91    .032       0
 1773.38     .08       0  2864.2     .06       0  2976.6     .08       0
Levee=0,,,-1,1841,729.55,,
#XS Ineff= 2 ,-1
       0  765.67   727.9  765.67 1195.56  724.69
Permanent Ineff=
       F       F
Bank Sta=1274.91,1773.38
XS Rating Curve= 0 ,0
Exp/Cntr=0.3,0.1