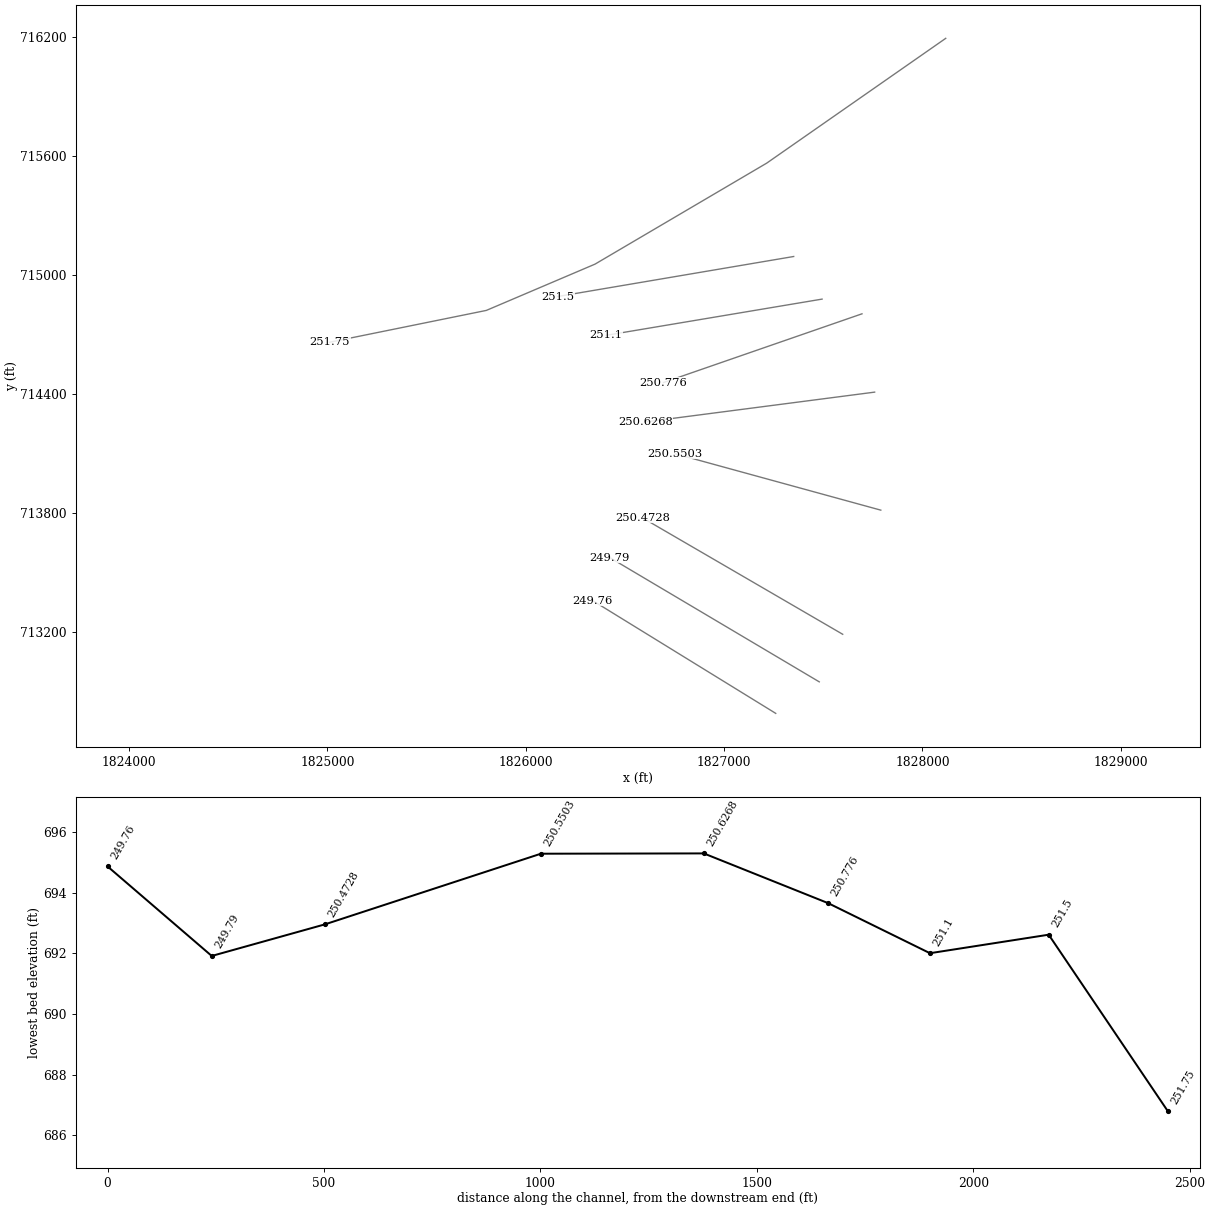
HEC-RAS study FRA-70-1321R.prj: FRA-70-1321R

--- FRA-70-1321R.g05 (geometry) --- (continued)

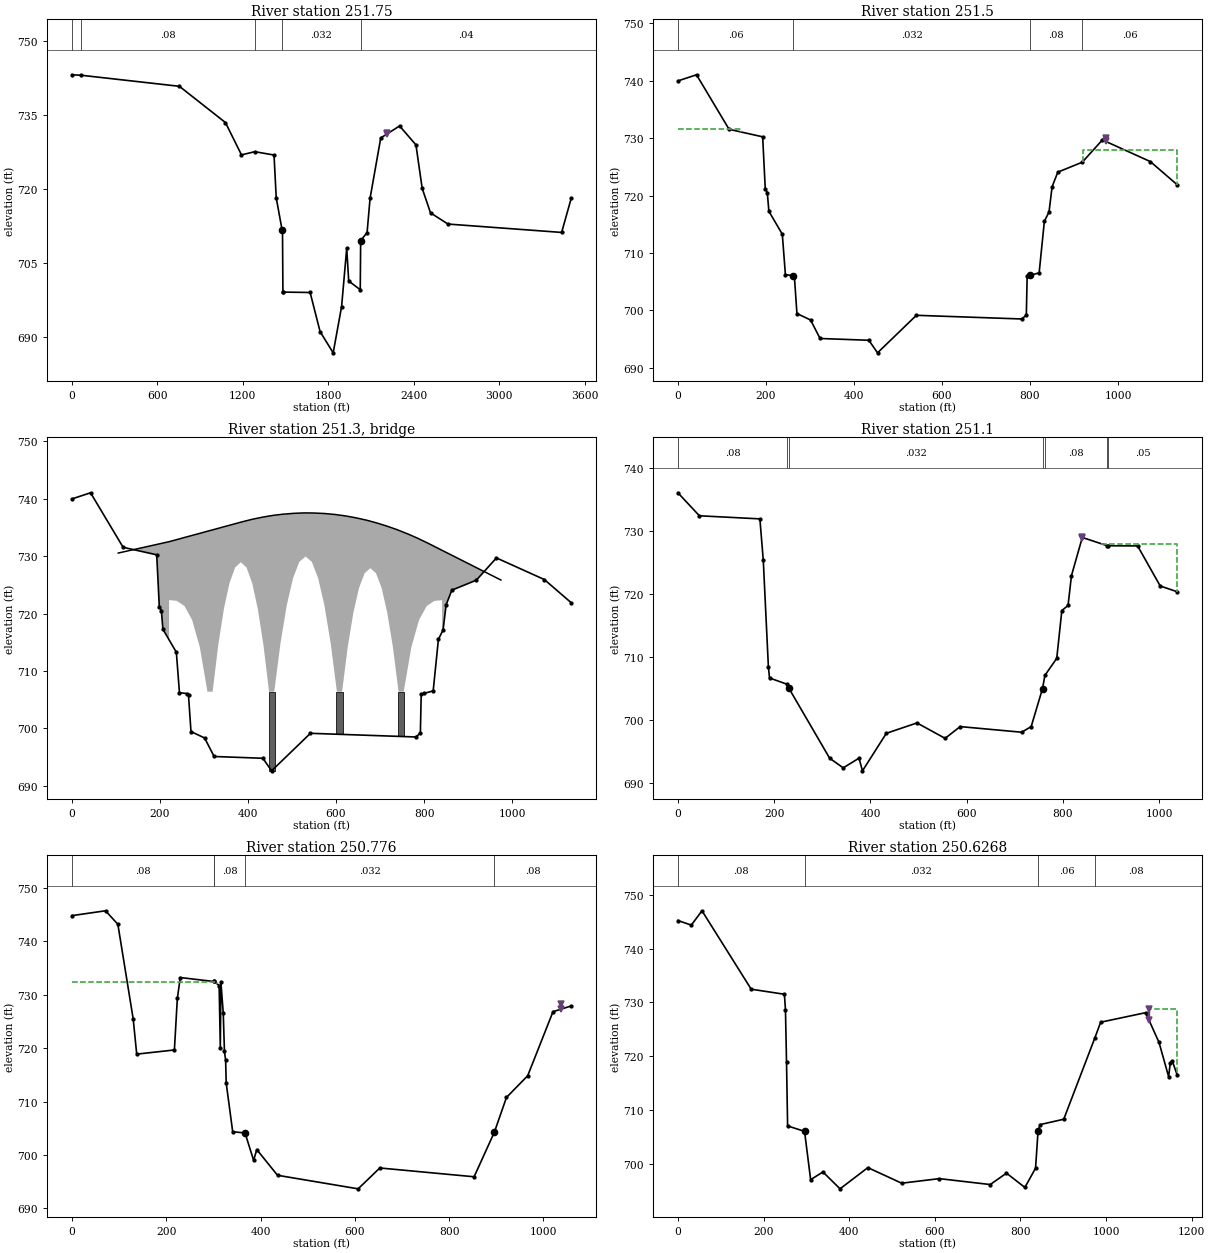
Type RM Length L Ch R = 1 ,251.75  ,405.37,275.3,167.66
BEGIN DESCRIPTION:
Overbank geometry from 2011 City of Columbus LiDAR data.  Channel geometry from 2011 hydrographic survey by Resource International.
END DESCRIPTION:
XS GIS Cut Line= 5
1828117.20168278716194.0865052641827214.42396078715564.746228516
1826348.89649236 715055.628480361825800.97993727714822.295285597
 1825011.3965427714661.878611684
#Sta/Elev= 30
       0  743.23    66.2  743.13  754.48  740.89    1078  733.53 1190.42  726.97
 1284.09  727.62 1418.98  726.94 1434.43  718.26 1475.42  711.75 1478.42  711.66
 1481.42  699.22 1482.42  699.12 1672.41  699.04 1742.41   691.1  1834.4  686.79
  1893.4  696.18  1929.4  707.99 1943.39  701.37 2024.39   699.6 2027.39  709.58
 2072.39  711.19 2093.42  718.17 2168.34  730.41 2300.69  732.84 2415.56     729
 2459.26  720.18 2517.94   715.2  2640.3  712.93 3438.48  711.23 3505.94  718.18
#Mann= 5 ,-1 , 0
       0     .06       0    66.2     .08       0 1284.09     .05       0
 1475.42    .032       0 2027.39     .04       0
Levee=0,,,-1,2210,731.4,,
Bank Sta=1475.42,2027.39
XS Rating Curve= 0 ,0
Exp/Cntr=0.5,0.3

Type RM Length L Ch R = 1 ,251.5   ,243.88,274.25,267.45
BEGIN DESCRIPTION:
Overbank geometry from 2011 City of Columbus LiDAR data.  Channel geometry from 2011 hydrographic survey by Resource International.
END DESCRIPTION:
Node Name=AJ
XS GIS Cut Line= 2
1827350.66056494 715094.145463691826160.55402127714892.372245193
#Sta/Elev= 30
       0  739.99  42.267  741.06 116.249  731.56 192.571  730.25 198.444  721.23
 203.143  720.51 206.667  717.28 237.188  713.28 244.236  706.23 261.525  706.07
 264.796  705.75 270.425  699.46 301.416  698.33  323.01  695.11 433.809   694.8
 453.533  692.61 541.799  699.15 781.232  698.51 791.559  699.19 793.439  705.95
 800.017706.1002 820.671  706.55 832.521  715.52 843.092  717.16  850.14  721.55
 863.051  724.09 918.737 725.833 964.331  729.711073.242  725.941134.294   721.9
#Mann= 4 ,-1 , 0
       0     .06       0 261.525    .032       0 800.017     .08       0
 918.737     .06       0
Levee=0,,,-1,972.22,730.08,,
#XS Ineff= 2 , 0
       0 142.242  731.57 919.311       0     728
Permanent Ineff=
       F       F
Bank Sta=261.525,800.017
XS Rating Curve= 0 ,0
Skew Angle= 20
Exp/Cntr=0.5,0.3

Type RM Length L Ch R = 3 ,251.3   ,,,
BEGIN DESCRIPTION:
Broad Street Bridge
Geometry from plans provided by the Franklin County Engineer's Office.
END DESCRIPTION:
Bridge Culvert--1,0,-1,-1, 0
Deck Dist Width WeirC Skew NumUp NumDn MinLoCord MaxHiCord MaxSubmerge Is_Ogee
70,98,2.6,20, 80, 79, , , 0.98, 0, 0,0,,
 105.226 199.196 220.677 220.677 222.688 238.109 246.181  255.54 269.673 272.971
 290.403 293.165 307.834 316.657  319.58 332.406  340.15 345.233  358.06 363.643
 370.887 383.714 387.135 396.541 409.367 410.627 422.194 434.119 435.021 447.848
 457.612 459.594  473.83 481.104 488.067 502.303 504.596  516.54 528.088 530.776
 545.013 551.581 559.248 573.485 575.074 587.721 598.565 601.958 613.703 622.058
  626.53 639.357  645.55 652.184 665.011 669.043 677.838 690.664 692.534 703.491
 716.027 716.318 729.145 739.519 741.972 753.718 763.012  771.15 786.503 788.581
 806.012 809.996 823.444 833.489 840.875 840.875 853.354 856.981 880.474 974.443
  730.56  732.17  732.54  732.54  732.58   732.9  733.07  733.27  733.56  733.63
  733.99  734.05  734.36  734.54   734.6  734.87  735.03  735.14   735.4  735.52
  735.67  735.94  736.01  736.19  736.44  736.46  736.64  736.83  736.84  737.01
  737.13  737.15  737.28  737.34  737.38  737.47  737.48  737.52  737.55  737.55
  737.54  737.53   737.5  737.45  737.44  737.35  737.27  737.23  737.11  737.02
  736.96  736.78  736.69  736.58  736.36  736.29  736.11  735.84   735.8  735.54
  735.24  735.23  734.89  734.61  734.53  734.17  733.89  733.62   733.1  733.02
  732.38  732.23  731.71  731.32  731.03  731.03  730.55  730.41   729.5  725.86
                     690  722.36  722.35  722.23  721.82  721.34  719.37  718.91
  714.19  712.96   706.4   706.4   706.4  714.53  718.34  720.84  725.35  726.53
  728.06  728.96  728.72  728.06  725.35  724.91  720.84  714.97  714.53   706.4
   706.4   706.4  714.87  718.24  721.47  726.19  726.65  729.02  729.78  729.96
  729.02  727.71  726.19  721.47  720.73  714.87  708.42   706.4   706.4  711.46
  714.17  720.17  722.25  724.48  727.06  727.33  727.92  727.06  726.68  724.48
  720.27  720.17  714.17  707.89   706.4   706.4  710.55  714.18  718.34   718.9
  721.33  721.53  722.22  722.29  722.35     690
 168.571 183.682 183.682 185.693 201.113 209.184 218.545 232.677 235.976 253.407
  256.17 270.839 279.662 282.584 295.411 303.155 308.238 321.065 326.646 333.891
 346.718 350.139 359.545 372.372 373.631 385.199 397.124 398.026 410.853 420.615
 422.599 436.835 444.108 451.072 465.308 467.601 479.544 491.093  493.78 508.017
 514.585 522.253  536.49 538.077 550.726  561.57 564.961 576.708 585.062 589.535
 602.362 608.554 615.188 628.015 632.046 640.842 653.669 655.539 666.496 679.032
 679.323  692.15 702.523 704.976 716.723 726.016 734.154 749.508 751.584 769.016
 773.001 786.447 796.493 803.878 803.878 816.358 819.985 843.477 937.447
  732.28  732.54  732.54  732.58   732.9  733.07  733.27  733.56  733.63  733.99
  734.05  734.36  734.54   734.6  734.87  735.03  735.14   735.4  735.52  735.67
  735.94  736.01  736.19  736.44  736.46  736.64  736.83  736.84  737.01  737.13
  737.15  737.28  737.34  737.38  737.47  737.48  737.52  737.55  737.55  737.54
  737.53   737.5  737.45  737.44  737.35  737.27  737.23  737.11  737.02  736.96
  736.78  736.69  736.58  736.36  736.29  736.11  735.84   735.8  735.54  735.24
  735.23  734.89  734.61  734.53  734.17  733.89  733.62   733.1  733.02  732.38
  732.23  731.71  731.32  731.03  731.03  730.55  730.41   729.5  725.86
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Pier Skew, UpSta & Num, DnSta & Num=  ,313.707, 4 ,276.711, 4 , 3 , 3 , 0 ,,
       7       7      14      14
     690   699.4   699.4   706.4
       7       7      14      14
     690   699.4   699.4   706.4
Pier Skew, UpSta & Num, DnSta & Num=  ,453.722, 4 ,416.725, 4 , 3 , 3 , 0 ,,
       7       7      14      14
     690   699.4   699.4   706.4
       7       7      14      14
     690   699.4   699.4   706.4
Pier Skew, UpSta & Num, DnSta & Num=  ,607.831, 4 ,570.835, 4 , 3 , 3 , 0 ,,
       7       7      14      14
     690   699.4   699.4   706.4
       7       7      14      14
     690   699.4   699.4   706.4
Pier Skew, UpSta & Num, DnSta & Num=  ,747.845, 4 ,710.849, 4 , 3 , 3 , 0 ,,
       7       7      14      14
     690   699.4   699.4   706.4
       7       7      14      14
     690   699.4   699.4   706.4
BR Coef=-1 , 1 , 1 ,0.9, 0 ,,,0.8,-1,1.33,1,
WSPro=,,,, 1 ,,,, 0 ,,,, 0 ,,,,-1 ,-1 ,-1 , 0 , 0 , 0 , 0 , 0
BC Design=,, 0 ,, 0 ,,,,,,
BC Use User HTab Curves=0
BC User HTab FreeFlow(D)= 0

Type RM Length L Ch R = 1 ,251.1   ,179.49,235.17,283.09
BEGIN DESCRIPTION:
Overbank geometry from 2011 City of Columbus LiDAR data.  Channel geometry from 2011 hydrographic survey by Resource International.
END DESCRIPTION:
XS GIS Cut Line= 3
1827493.87156461 714879.32863611 1826405.4665892714696.734513104
1826405.45671739714696.732856979
#Sta/Elev= 30
       0     736  44.626  732.36   170.3  731.87 177.348  725.32  187.92   708.5
 190.269   706.7 226.889705.6979 230.224  705.11 315.164     694  343.41  692.47
 376.131     694 383.385     692 432.954  697.94 496.543  699.58 555.077  697.14
 586.303     699 714.101  698.11 733.796     699 757.327  705.02 762.297707.1105
 786.899   709.8  797.47  717.37 810.382  718.17 817.429  722.88 839.972  728.93
 891.571727.6287 892.699727.6191  954.85  727.591001.825  721.251037.064  720.34
#Mann= 7 ,-1 , 0
       0     .08       0 226.889    .035       0 230.224    .032       0
 757.327    .035       0 762.297     .08       0 891.571     .06       0
 892.699     .05       0
Levee=0,,,-1,839.74,729.04,,
#XS Ineff= 2 , 0
       0  107.95  731.34  879.61       0  727.86
Permanent Ineff=
       F       F
Bank Sta=230.224,757.327
XS Rating Curve= 0 ,0
Skew Angle= 20
Exp/Cntr=0.5,0.3

Type RM Length L Ch R = 1 ,250.776 ,322.81,287.31,216.99
BEGIN DESCRIPTION:
Overbank geometry from 2011 City of Columbus LiDAR data.  Channel geometry from 2011 hydrographic survey by Resource International.
END DESCRIPTION:
XS GIS Cut Line= 2
1827694.99091302714805.1440731881826694.41936781714458.718250939
#Sta/Elev= 30
       0  744.84   71.17  745.75   97.39  743.22  129.86   725.5  137.35  718.89
  217.27  719.67  223.51  729.32  229.75  733.24  300.92   732.5  302.17   732.5
  312.16  731.73  314.66     720  315.91  732.32   320.9  726.57   323.4  719.41
   325.9  717.77  327.15  713.47  340.88  704.35   367.1  704.12  385.23     699
  392.05     701  435.94  696.19  606.92  693.65  652.91  697.56  852.88  695.91
   895.8  704.26   921.5  710.78  966.45  714.83 1020.14  726.84 1058.85  727.92
#Mann= 5 ,-1 , 0
       0     .08       0  300.92    .035       0  302.17     .08       0
   367.1    .032       0   895.8     .08       0
Levee=0,,,-1,1036.68,728.31,,
#XS Ineff= 2 , 0
          307.43  732.45
Permanent Ineff=
       F       F
Bank Sta=367.1,895.8
XS Rating Curve= 0 ,0
Exp/Cntr=0.3,0.1

Type RM Length L Ch R = 1 ,250.6268,445.39,376.26,241.66
BEGIN DESCRIPTION:
Overbank geometry from 2011 City of Columbus LiDAR data.  Channel geometry from 2011 hydrographic survey by Resource International.
END DESCRIPTION:
XS GIS Cut Line= 2
1827758.81230769 714410.312185691826602.38220586 714259.94043918
#Sta/Elev= 30
       0  745.24   31.25  744.38   56.25  747.05  171.24  732.45  248.73  731.51
  251.23  728.63  253.73  718.81  256.23     707  295.82  705.99  310.02     697
  338.76  698.43  378.73  695.29  443.68  699.24  522.63  696.34  610.56  697.19
  729.48  696.09  767.45  698.21  810.42  695.55  835.37  699.14  841.19  706.08
  846.19  707.25  901.18  708.25  973.68  723.35  987.43  726.31 1092.42  728.08
 1123.67  722.56 1146.16  716.17 1149.91  718.69 1154.91  719.05 1166.16  716.49
#Mann= 4 ,-1 , 0
       0     .08       0  295.82    .032       0  841.19     .06       0
  973.68     .08       0
Levee=0,,,-1,1099.68,728.71,,
#XS Ineff= 2 , 0
       0                 1099.68       0  728.71
Permanent Ineff=
       F       F
Bank Sta=295.82,841.19
XS Rating Curve= 0 ,0
Exp/Cntr=0.3,0.1

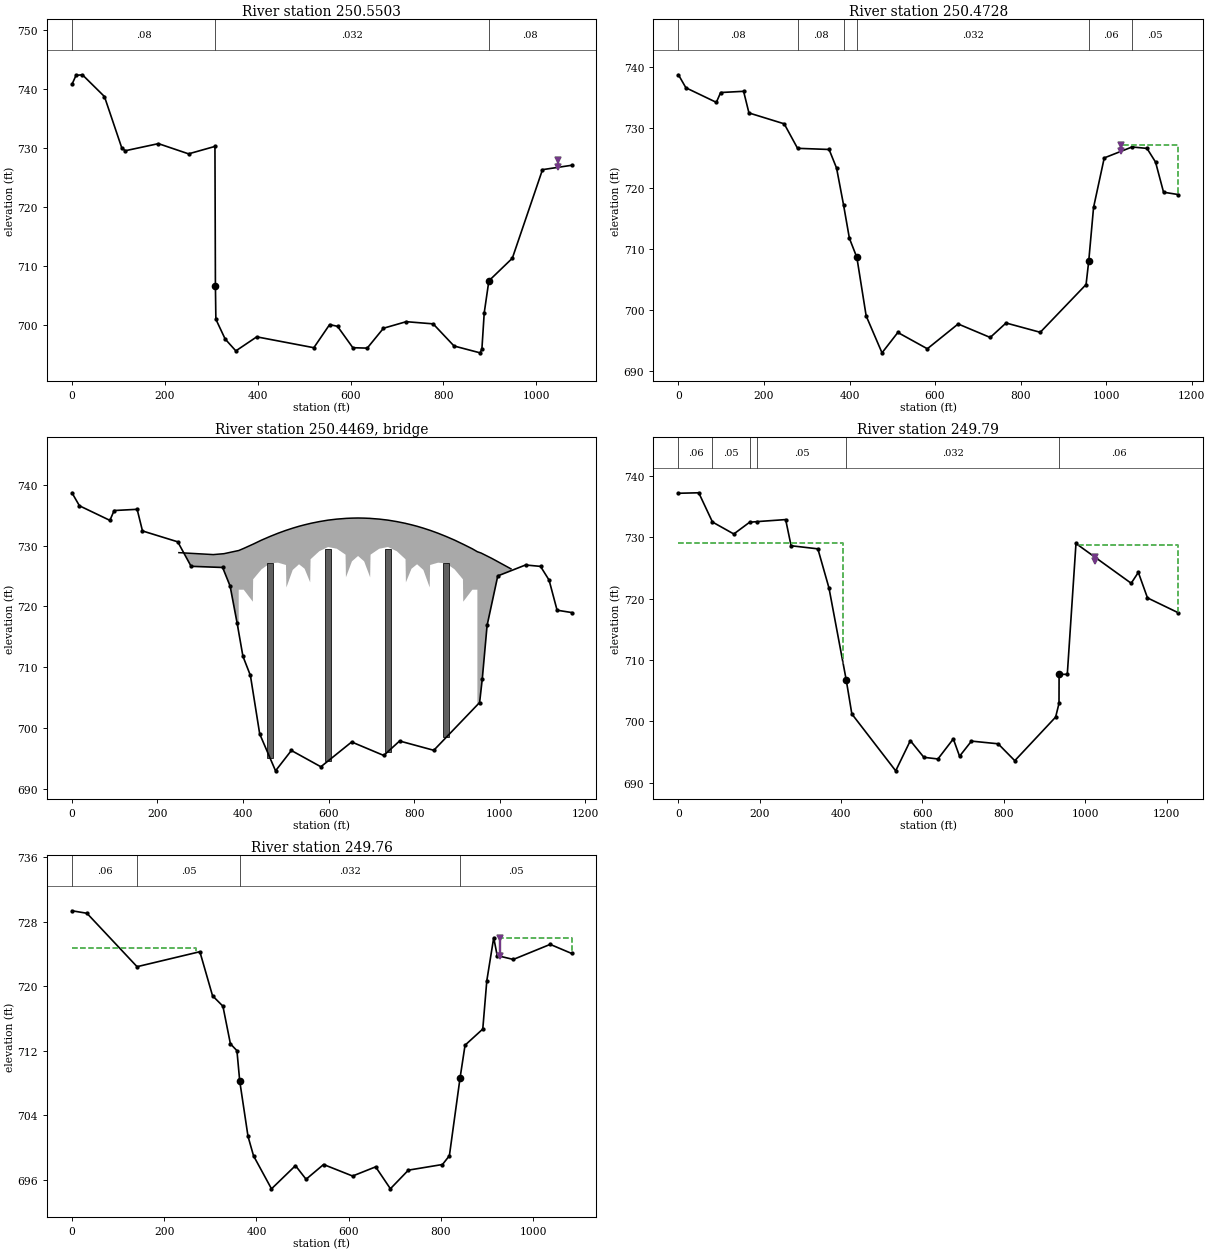
Type RM Length L Ch R = 1 ,250.5503,536.12,499.14,418.07
BEGIN DESCRIPTION:
Overbank geometry from 2011 City of Columbus LiDAR data.  Channel geometry from 2011 hydrographic survey by Resource International.
END DESCRIPTION:
Node Name=AI
XS GIS Cut Line= 2
   1827789.82406   713815.278271   1826752.47114   714099.776389
#Sta/Elev= 30
       0  740.77    8.75   742.3   22.49   742.4   69.96  738.71  107.44  729.97
  114.94  729.53  186.15  730.73  251.11     729   307.9  730.26   308.9  706.63
   309.9  700.97  329.89  697.62  352.89  695.61  397.87  697.99  520.83  696.15
  554.82  700.07  571.82  699.77  604.81  696.15   635.8  696.08  670.78  699.45
  719.77  700.56  777.75  700.19  822.73  696.44  878.72  695.28  882.71  695.92
  887.71  702.05  897.71  707.48  948.23  711.31 1013.19  726.32 1075.66  727.06
#Mann= 3 ,-1 , 0
       0     .08       0   308.9    .032       0  897.71     .08       0
Levee=0,,,-1,1045.87,728,,
Bank Sta=308.9,897.71
XS Rating Curve= 0 ,0
Exp/Cntr=0.5,0.3

Type RM Length L Ch R = 1 ,250.4728,263.74,261.23,259.9
BEGIN DESCRIPTION:
Overbank geometry from 2011 City of Columbus LiDAR data.  Channel geometry from 2011 hydrographic survey by Resource International.
END DESCRIPTION:
XS GIS Cut Line= 2
1827597.69976902713189.4370027631826588.06104028713776.602823183
#Sta/Elev= 30
       0   738.7   17.49  736.56   88.69  734.16   98.68  735.78   152.4  735.98
  164.89  732.42  247.33  730.63  278.56   726.6  352.26  726.41  369.75  723.35
  385.99  717.32  399.73   711.8  417.22  708.64 438.949699.0211  475.99  692.95
  512.98   696.3  581.98  693.62  653.98   697.7  728.98  695.48  765.98  697.86
  845.97  696.33   953.1  704.19  959.35  708.07  970.59  716.87  995.57  725.02
 1060.53  726.82  1095.5  726.59 1115.49  724.34 1134.23  719.38 1167.96     719
#Mann= 6 ,-1 , 0
       0     .08       0  278.56     .08       0  385.99     .04       0
  417.22    .032       0  959.35     .06       0 1060.53     .05       0
Levee=0,,,-1,1033.78,727.2,,
#XS Ineff= 2 , 0
       0  210.89  731.25 1033.78       0   727.2
Permanent Ineff=
       F       F
Bank Sta=417.22,959.35
XS Rating Curve= 0 ,0
Exp/Cntr=0.5,0.3

Type RM Length L Ch R = 3 ,250.4469,,,
BEGIN DESCRIPTION:
Rich Street Bridge
Geometry from HEC-RAS model prepared by DLZ and provided by the City of Columbus and from construction plans provided by the City of Columbus, Transportation Division.
END DESCRIPTION:
Bridge Culvert--1,0,-1,-1, 0
Deck Dist Width WeirC Skew NumUp NumDn MinLoCord MaxHiCord MaxSubmerge Is_Ogee
179,60,2.6,0, 52, 53, , , 0.98, 0, 0,0,,
     250   305.4   330.4 355.401   380.4  389.89  389.89  401.64  422.95  423.64
 443.139  462.89  481.64  500.39  501.36 516.139  530.89 543.891  557.01  557.89
  578.39 598.889  619.39  639.64 640.581  654.64  668.89  683.14   697.2 698.139
 718.391  738.89  759.39  779.89  780.77  793.89  806.89  821.64  836.42  837.39
 856.139 874.891  894.64  914.14  914.83  936.14 947.889 947.889  956.52  981.52
 1006.52 1026.52
  728.85  728.63  728.53  728.68  729.06   729.2   729.2  729.55  730.23  730.25
  730.91  731.51  732.04  732.52  732.54  732.88  733.19  733.43  733.65  733.67
  733.96   734.2  734.37  734.48  734.49  734.53  734.55  734.53  734.49  734.48
  734.37   734.2  733.96  733.67  733.65  733.43  733.19  732.88  732.54  732.52
  732.04  731.51  730.91  730.25  730.23  729.48     729     729  728.79  727.91
  726.95  726.18
                                             690  722.75  722.75  720.78  724.46
   726.1  727.09   727.2  726.82  723.12     726  726.94  726.21  723.96  727.76
  729.09  729.78  729.49  728.52  724.79  727.42   728.3  727.42  724.79  728.52
  729.49  729.78  729.09  727.76  723.96  726.21  726.94     726  723.12  726.82
   727.2  727.09   726.1  724.46  720.78  722.75  722.75     690
  275.11 330.509  355.51  380.51  405.51     415     415  426.75  448.06  448.75
  468.25     488  506.75   525.5  526.47  541.25     556     569  582.12     583
   603.5     624   644.5  664.75  665.69  679.75     694  708.25  722.31  723.25
   743.5     764 784.501     805  805.88     819     832  846.75  861.53   862.5
  881.25     900  919.75  939.25 939.939  961.25     973     973  981.63 1006.63
 1031.63 1056.63  1073.9
  728.85  728.63  728.53  728.68  729.06   729.2   729.2  729.55  730.23  730.25
  730.91  731.51  732.04  732.52  732.54  732.88  733.19  733.43  733.65  733.67
  733.96   734.2  734.37  734.48  734.49  734.53  734.55  734.53  734.49  734.48
  734.37   734.2  733.96  733.67  733.65  733.43  733.19  732.88  732.54  732.52
  732.04  731.51  730.91  730.25  730.23  729.48     729     729  728.79  727.91
  726.95  725.99  724.47
                                             690  722.75  722.75  720.78  724.46
   726.1  727.09   727.2  726.82  723.12     726  726.94  726.21  723.96  727.76
  729.09  729.78  729.49  728.52  724.79  727.42   728.3  727.42  724.79  728.52
  729.49  729.78  729.09  727.76  723.96  726.21  726.94     726  723.12  726.82
   727.2  727.09   726.1  724.46  720.78  722.75  722.75     690
Pier Skew, UpSta & Num, DnSta & Num=  ,462.89, 6 ,488, 6 , 3 , 3 , 0 ,,
     6.5     6.5       9       9      13      13
       0   700.9   700.9   705.9   705.9   729.4
     6.5     6.5       9       9      13      13
       0   700.9   700.9   705.9   705.9   729.4
Pier Skew, UpSta & Num, DnSta & Num=  ,598.889, 6 ,624, 6 , 3 , 3 , 0 ,,
     6.5     6.5       9       9      13      13
       0   700.9   700.9   705.9   705.9   729.4
     6.5     6.5       9       9      13      13
       0   700.9   700.9   705.9   705.9   729.4
Pier Skew, UpSta & Num, DnSta & Num=  ,738.89, 6 ,764, 6 , 3 , 3 , 0 ,,
     6.5     6.5       9       9      13      13
       0   700.9   700.9   705.9   705.9   729.4
     6.5     6.5       9       9      13      13
       0   700.9   700.9   705.9   705.9   729.4
Pier Skew, UpSta & Num, DnSta & Num=  ,874.891, 6 ,900, 6 , 3 , 3 , 0 ,,
     6.5     6.5       9       9      13      13
       0   700.9   700.9   705.9   705.9   729.4
     6.5     6.5       9       9      13      13
       0   700.9   700.9   705.9   705.9   729.4
BR Coef=-1 , 1 , 1 ,0.9, 0 ,,,0.8,-1,1.33,1,
WSPro=,,,, 1 ,,,, 0 ,,,, 0 ,,,,-1 ,-1 ,-1 , 0 , 0 , 0 , 0 , 0
BC Design=,, 0 ,, 0 ,,,,,,
BC Use User HTab Curves=0
BC User HTab FreeFlow(D)= 0

Type RM Length L Ch R = 1 ,249.79  ,243.01,240.57,234.78
BEGIN DESCRIPTION:
Overbank geometry from 2011 City of Columbus LiDAR data.  Channel geometry from 2011 hydrographic survey by Resource International.
END DESCRIPTION:
XS GIS Cut Line= 2
1827479.55039902712949.558217436 1826423.3681282713576.107161194
#Sta/Elev= 30
       0  737.17   49.97  737.25    83.7  732.48  136.17  730.53   174.9  732.44
  193.64  732.55   263.6  732.88  276.97 728.613  342.78 728.108  370.13 721.722
  412.47 706.743  426.31 701.188  534.13 691.909  570.12 696.829  603.38 694.116
  637.89 693.844  675.79 697.117  691.11 694.287  720.37 696.757  785.92  696.32
  826.87 693.563  927.28 700.675  935.58 702.907  935.79 707.641  955.96 707.648
  977.31 728.981 1113.02 722.497 1130.59  724.27 1153.08  720.11 1228.04  717.71
#Mann= 6 ,-1 , 0
       0     .06       0    83.7     .05       0   174.9     .06       0
  193.64     .05       0  412.47    .032       0  935.79     .06       0
Levee=0,,,-1,1024.4,726.13,,
#XS Ineff= 2 , 0
       0     405  729.05     983       0  728.74
Permanent Ineff=
       F       F
Bank Sta=412.47,935.79
XS Rating Curve= 0 ,0
Exp/Cntr=0.5,0.3

Type RM Length L Ch R = 1 ,249.76  ,150.75,205.87,256.95
BEGIN DESCRIPTION:
Overbank geometry from 2011 City of Columbus LiDAR data.  Channel geometry from 2011 hydrographic survey by Resource International.
END DESCRIPTION:
XS GIS Cut Line= 2
   1827260.08299   712790.621527   1826337.86075    713358.67715
#Sta/Elev= 30
       0  729.37   32.48  729.06  141.17  722.43  277.34  724.29  304.83  718.82
  327.31  717.53  343.55  712.86  357.71  712.01  363.71  708.26   381.7  701.38
  393.69  698.96  432.65  694.86  484.61  697.74  507.59  696.05  545.56  697.88
  608.51  696.45  658.47  697.59  690.45  694.87  729.42  697.18  803.36  697.88
  818.35  698.97  841.33  708.56  852.32  712.69  890.75  714.69  899.49  720.69
  914.49  726.03  921.98  723.81  956.96  723.33 1036.92   725.2 1083.14  724.08
#Mann= 4 ,-1 , 0
       0     .06       0  141.17     .05       0  363.71    .032       0
  841.33     .05       0
Levee=0,,,-1,929.12,726,,
#XS Ineff= 2 , 0
       0  269.97  724.73  929.12       0     726
Permanent Ineff=
       F       F
Bank Sta=363.71,841.33
XS Rating Curve= 0 ,0
Exp/Cntr=0.5,0.3