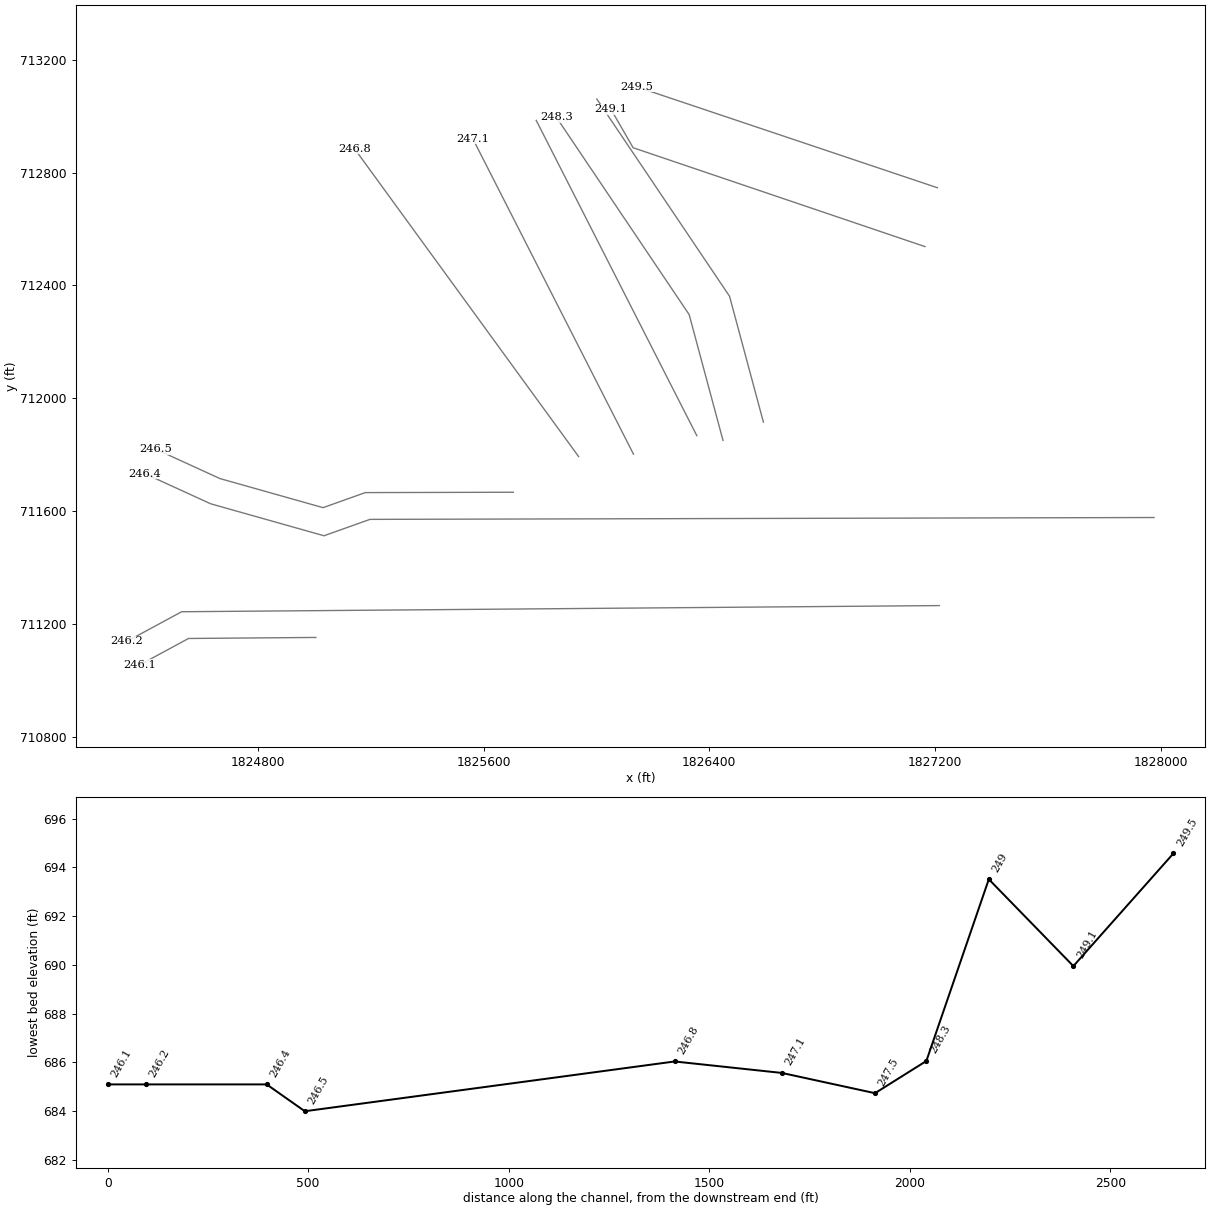
HEC-RAS study FRA-70-1321R.prj: FRA-70-1321R

--- FRA-70-1321R.g05 (geometry) --- (continued)

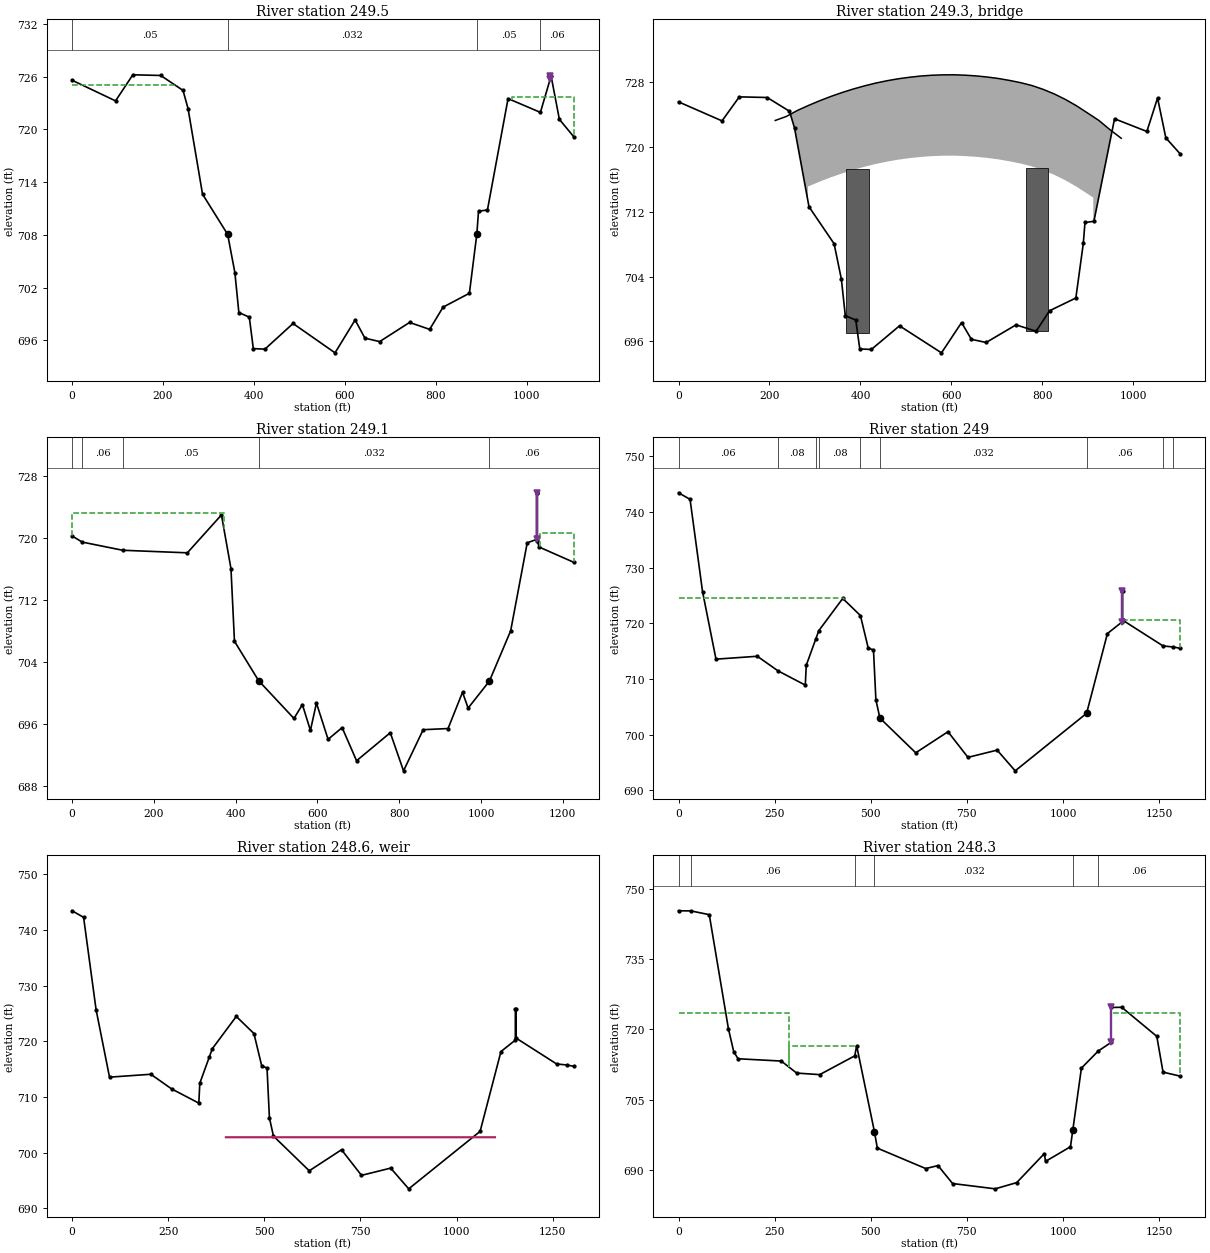
Type RM Length L Ch R = 1 ,249.5   ,235.08,249.49,252.77
BEGIN DESCRIPTION:
Overbank geometry from 2011 City of Columbus LiDAR data.  Channel geometry from 2011 hydrographic survey by Resource International.
END DESCRIPTION:
Node Name=AH
XS GIS Cut Line= 3
1827208.42298852712746.5258150991826142.91453844713104.247001041
1826142.90609069 713104.24983719
#Sta/Elev= 30
       0   725.6   95.62  723.25 133.619  726.22 194.922  726.14 243.954  724.44
 254.987  722.38 286.861  712.63 342.028  708.06  357.96  703.71  366.72  699.16
 389.696  698.63 398.531  695.05 424.043  694.99 485.886  697.91 578.159  694.57
 622.332  698.31 643.918  696.24 676.312  695.85 742.081  698.03 786.254  697.24
 815.703  699.77 873.609  701.35 890.002   708.1 893.683  710.69 913.296  710.83
 958.657  723.511029.766  721.941053.286  726.081071.446  721.151103.319  719.15
#Mann= 4 ,-1 , 0
       0     .05       0 342.028    .032       0 890.002     .05       0
1029.766     .06       0
Levee=0,,,-1,1051.32,726.08,,
#XS Ineff= 2 , 0
       0 229.639  725.01 966.929       0  723.66
Permanent Ineff=
       F       F
Bank Sta=342.028,890.002
XS Rating Curve= 0 ,0
Skew Angle= 11
Exp/Cntr=0.5,0.3

Type RM Length L Ch R = 3 ,249.3   ,,,
BEGIN DESCRIPTION:
Main Street Bridge.
Geometry from construction plans provided by the City of Columbus, Transportation Division.
END DESCRIPTION:
Bridge Culvert--1,0,-1,-1, 0
Deck Dist Width WeirC Skew NumUp NumDn MinLoCord MaxHiCord MaxSubmerge Is_Ogee
55,105,2.6,11, 36, 39, , , 0.98, 0, 0,0,,
 212.618 237.159   261.7 284.639 284.639 286.239  310.78 335.321 359.862 384.207
 408.943 433.484 458.025 482.565 507.106 531.647 556.188 580.727 605.268 629.809
  654.35  678.89 703.431 727.972 752.513 777.054 801.594 826.135 850.675 875.216
 899.756 911.929 911.929 924.297 948.838 973.379
   723.3   723.8  724.55  725.13  725.13  725.17  725.75  726.28  726.76  727.19
  727.58  727.92  728.21  728.45  728.64  728.79  728.89  728.94  728.95   728.9
  728.81  728.67  728.49  728.25  727.97  727.62  727.15  726.58   725.9  725.11
  724.21  723.76  723.76   723.3  722.15   721.1
                             680  715.13  715.17  715.75  716.28  716.76  717.19
  717.58  717.92  718.21  718.45  718.64  718.79  718.89  718.94  718.95   718.9
  718.81  718.67  718.49  718.25  717.97  717.62  717.15  716.58   715.9  715.11
  714.21  713.76     680
 332.762 371.918 396.459     421 443.941 443.941 445.541 470.082 494.622 519.163
 543.507 568.245 592.785 617.326 641.866 666.407 690.947 715.488 740.029  764.57
  789.11 813.651 838.192 862.733 887.274 911.813 936.354 960.895 985.4361009.976
1034.5171059.058 1071.23 1071.231083.5991108.139 1132.681181.7621224.178
   722.5   723.3   723.8  724.55  725.13  725.13  725.17  725.75  726.28  726.76
  727.19  727.58  727.92  728.21  728.45  728.64  728.79  728.89  728.94  728.95
   728.9  728.81  728.67  728.49  728.25  727.97  727.62  727.15  726.58   725.9
  725.11  724.21  723.76  723.76   723.3  722.15   721.1     719  717.19
                                     680  715.13  715.17  715.75  716.28  716.76
  717.19  717.58  717.92  718.21  718.45  718.64  718.79  718.89  718.94  718.95
   718.9  718.81  718.67  718.49  718.25  717.97  717.62  717.15  716.58   715.9
  715.11  714.21  713.76     680
Pier Skew, UpSta & Num, DnSta & Num=  ,393.574, 2 ,562.875, 2 , 0 , 0 , 0 ,,
   48.74   28.24
     680     718
   48.74   28.24
     680     718
Pier Skew, UpSta & Num, DnSta & Num=  ,787.324, 2 ,956.626, 2 , 0 , 0 , 0 ,,
   48.74   28.24
     680     718
   48.74   28.24
     680     718
BR Coef=-1 , 0 , 0 ,1.25, 0 ,,,0.8,-1,2,1,
WSPro=,,,, 1 ,,,, 0 ,,,, 0 ,,,,-1 ,-1 ,-1 , 0 , 0 , 0 , 0 , 0
BC Design=,, 0 ,, 0 ,,,,,,
BC Use User HTab Curves=0
BC User HTab FreeFlow(D)= 0

Type RM Length L Ch R = 1 ,249.1   ,377.23,210.84,63.5
BEGIN DESCRIPTION:
Overbank geometry from 2011 City of Columbus LiDAR data.  Channel geometry from 2011 hydrographic survey by Resource International.
END DESCRIPTION:
XS GIS Cut Line= 3
1827164.48606853712537.8261012731826129.67448986712888.366082609
1826051.02407532713024.735525452
#Sta/Elev= 30
       0  720.27  24.511  719.48 123.793  718.42 281.914  718.09 365.263  722.98
 388.548  716.06 397.127  706.67  456.28  701.58 542.624  696.71 563.228   698.5
 582.861  695.17 597.575   698.7 626.033  694.02  660.38  695.53 695.699  691.25
 778.126  694.87  810.51  689.95  858.59  695.26 919.431  695.41  954.75  700.09
 968.493  698.05  1020.5  701.531072.496  708.021112.969  719.381135.743  719.82
1135.743  725.841137.706  725.841137.706  719.561142.408  718.831227.034  716.86
#Mann= 5 ,-1 , 0
       0     .08       0  24.511     .06       0 123.793     .05       0
  456.28    .032       0  1020.5     .06       0
Levee=0,,,-1,1135.74,725.84,,
#XS Ineff= 2 , 0
       0 371.174  723.281143.997       0  720.62
Permanent Ineff=
       F       F
Bank Sta=456.28,1020.5
XS Rating Curve= 0 ,0
Skew Angle= 11
Exp/Cntr=0.5,0.3

Type RM Length L Ch R = 1 ,249     ,156.71,155.69,155.43
BEGIN DESCRIPTION:
Overbank geometry from 2011 City of Columbus LiDAR data.  Channel geometry from 2011 hydrographic survey by Resource International.
END DESCRIPTION:
XS GIS Cut Line= 4
1826591.64108561 711915.406414361826471.59965903712361.660115018
1826000.89521986713061.0957240161826000.89521986713061.095724017
#Sta/Elev= 30
       0  743.43   29.98  742.25   62.45  725.68   97.42  713.56  204.83  714.08
  258.88711.4537  329.73   708.9  332.22  712.46  356.89717.1614  364.93718.6832
  427.15  724.46  473.07721.3896  493.34  715.57  507.08   715.2  513.33  706.26
  523.74702.9878  616.95  696.75  700.86  700.53   752.8  695.93  828.72  697.23
  875.67  693.51 1061.36  703.83 1115.59  718.16    1153  720.21    1153  725.82
    1155  725.82    1155  720.57 1260.24715.9334 1286.31715.7479 1305.19  715.51
#Mann= 9 ,-1 , 0
       0     .06       0  258.88     .08       0  356.89     .06       0
  364.93     .08       0  473.07     .05       0  523.74    .032       0
 1061.36     .06       0 1260.24     .08       0 1286.31     .06       0
Levee=0,,,-1,1153,725.82,,
#XS Ineff= 2 , 0
       0   430.3  724.51 1156.65       0  720.58
Permanent Ineff=
       F       F
Bank Sta=523.74,1061.36
XS Rating Curve= 0 ,0
Exp/Cntr=0.5,0.3

Type RM Length L Ch R = 5 ,248.6   ,,,
BEGIN DESCRIPTION:
Main Street Dam
Crest elevation from survey performed by Resource International in September 2011.
END DESCRIPTION:
IW Pilot Flow=0
#Inline Weir SE= 2
     400  702.76    1100  702.77
IW Dist,WD,Coef,Skew,MaxSub,Min_El,Is_Ogee,SpillHt,DesHd
50,5,2.6,0,0.98,, 0 ,,,0,0.87,

Type RM Length L Ch R = 1 ,248.3   ,156.94,128.05,104.7
BEGIN DESCRIPTION:
Overbank geometry from 2011 City of Columbus LiDAR data.  Channel geometry from 2011 hydrographic survey by Resource International.
END DESCRIPTION:
XS GIS Cut Line= 4
1826448.43008594711850.4124498521826328.38865936712296.666150525
1825857.68389212712996.1017595231825857.67830347712996.110063883
#Sta/Elev= 30
       0  745.27   32.47  745.24   79.93  744.44  129.89  720.09  143.63  715.25
  154.87  713.76  267.28  713.27  307.25  710.71   367.2  710.38  458.37  714.38
  463.37  716.52  509.58  698.21  517.06  694.73  642.92  690.38  674.89  691.01
  712.84  687.19  823.72  686.06  879.66  687.39  951.59  693.57  954.58   691.9
 1019.51  695.03 1025.42  698.52 1047.91  711.77 1091.62   715.4    1125  717.23
    1125  724.68 1152.82  724.72    1244  718.53 1260.24  710.91  1305.2  710.05
#Mann= 6 ,-1 , 0
       0     .08       0   32.47     .06       0  458.37     .05       0
  509.58    .032       0 1025.42     .04       0 1091.62     .06       0
Levee=0,,,-1,1125,724.68,,
#XS Ineff= 3 ,-1
       0  286.74   723.6  286.74  463.47  716.52 1131.04    1400   723.6
Permanent Ineff=
       F       F       F
Bank Sta=509.58,1025.42
XS Rating Curve= 0 ,0
Exp/Cntr=0.5,0.3

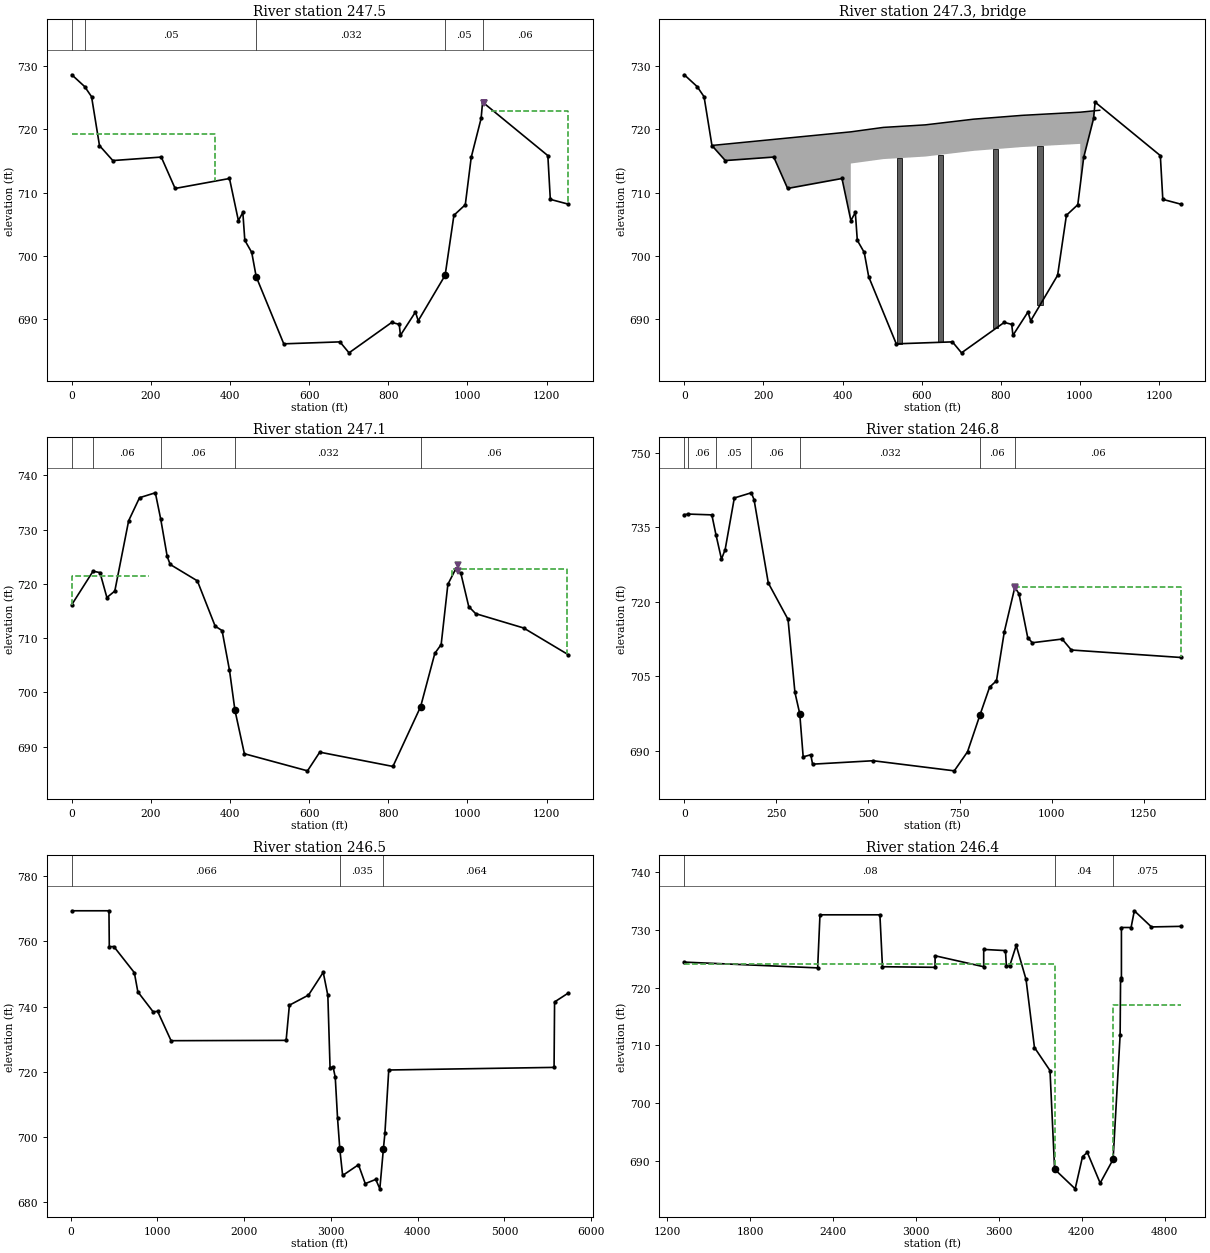
Type RM Length L Ch R = 1 ,247.5   ,235.21,232.14,230.24
BEGIN DESCRIPTION:
Overbank geometry from 2011 City of Columbus LiDAR data.  Channel geometry from 2011 hydrographic survey by Resource International.
END DESCRIPTION:
Node Name=AG
XS GIS Cut Line= 2
1826355.46078369711867.4403029381825786.08287978 712985.35215663
#Sta/Elev= 30
       0   728.6   32.49  726.74   49.98  725.14   69.98  717.43  103.71  715.07
  226.17  715.62  261.16  710.67  398.61  712.24  421.11   705.6  432.35  706.88
  437.35  702.49  454.84  700.58  466.16  696.74  535.82  686.16  677.77  686.47
  700.76  684.74  808.72  689.54  827.71  689.23  830.71   687.5   868.7  691.18
   875.7   689.8  943.67  696.97  965.92  706.44  994.66   708.1 1009.65  715.58
 1034.64  721.71 1038.39  724.29 1203.33  715.85 1209.58  708.95 1254.56   708.2
#Mann= 5 ,-1 , 0
       0     .08       0   32.49     .05       0  466.16    .032       0
  943.67     .05       0 1038.39     .06       0
Levee=0,,,-1,1042.49,724.2,,
#XS Ineff= 2 , 0
       0  362.95  719.22 1058.93       0  722.94
Permanent Ineff=
       F       F
Bank Sta=466.16,943.67
XS Rating Curve= 0 ,0
Exp/Cntr=0.5,0.3

Type RM Length L Ch R = 3 ,247.3   ,,,
BEGIN DESCRIPTION:
Norfolk Southern / CSX Shared Railroad Bridge
Geometry from plans provided by Norfolk Southern.  Top chord elevations adjusted using 2011 City of Columbus LiDAR data.
END DESCRIPTION:
Bridge Culvert--1,0,-1,-1, 0
Deck Dist Width WeirC Skew NumUp NumDn MinLoCord MaxHiCord MaxSubmerge Is_Ogee
58,70,2.6,0, 10, 10, , , 0.98, 0, 0,0,,
   74.32  420.95  420.95  503.09  609.09  731.42  853.75 1000.93 1000.93    1050
  717.48   719.6   719.6   720.3   720.7   721.6   722.2   722.7   722.7     723
             680   714.6   715.3   715.7   716.6   717.2   717.7     680
     300  377.68  377.68   457.3   563.3  685.63  807.96  959.11  959.11  976.83
   718.9   719.6   719.6   720.3   720.7   721.6   722.2   722.7   722.7  722.89
             680   714.6   715.3   715.7   716.6   717.2   717.7     680
Pier Skew, UpSta & Num, DnSta & Num=  ,543, 6 ,499.73, 6 , 0 , 0 , 0 ,,
   12.92   12.92   10.92   10.92    8.92    8.17
     683     688     688     694     694   715.5
   12.92   12.92   10.92   10.92    8.92    8.17
     683     688     688     694     694   715.5
Pier Skew, UpSta & Num, DnSta & Num=  ,647.12, 6 ,603.85, 6 , 0 , 0 , 0 ,,
   12.92   12.92   10.92   10.92    8.92    8.17
     683     688     688     694     694   715.9
   12.92   12.92   10.92   10.92    8.92    8.17
     683     688     688     694     694   715.9
Pier Skew, UpSta & Num, DnSta & Num=  ,787.58, 6 ,744.31, 6 , 0 , 0 , 0 ,,
   12.92   12.92   10.92   10.92    8.92    8.17
     683     688     688     694     694   716.9
   12.92   12.92   10.92   10.92    8.92    8.17
     683     688     688     694     694   716.9
Pier Skew, UpSta & Num, DnSta & Num=  ,899.28, 6 ,856.01, 6 , 0 , 0 , 0 ,,
   12.92   12.92   10.92   10.92    8.92    8.17
     683     688     688     694     694   717.4
   12.92   12.92   10.92   10.92    8.92    8.17
     683     688     688     694     694   717.4
BR Coef=-1 , 1 , 1 ,1.25, 0 ,,,0.8,-1,2,1,
WSPro=,,,, 1 ,,,, 0 ,,,, 0 ,,,,-1 ,-1 ,-1 , 0 , 0 , 0 , 0 , 0
BC Design=,, 0 ,, 0 ,,,,,,
BC Use User HTab Curves=0
BC User HTab FreeFlow(D)= 0

Type RM Length L Ch R = 1 ,247.1   ,230.39,267.48,301.97
BEGIN DESCRIPTION:
Overbank geometry from 2011 City of Columbus LiDAR data.  Channel geometry from 2011 hydrographic survey by Resource International.
END DESCRIPTION:
XS GIS Cut Line= 2
   1826130.98354   711801.668453   1825561.60115   712919.589117
#Sta/Elev= 30
       0  716.18   53.73  722.34   71.23  722.08   88.72  717.49  108.71  718.68
   143.7  731.63  171.19  735.87  211.18  736.78  224.92  731.88  241.17  725.05
  248.66  723.58  317.39  720.56  362.38  712.22  379.87   711.4  398.61   704.1
  412.36  696.74  436.27  688.72   595.8  685.57  626.78  689.01  811.72  686.38
  881.69  697.38  917.68  707.21  933.67  708.83  950.67  719.93  970.92  722.82
  983.41  721.96  1003.4  715.82  1020.9  714.52  1142.1  711.88 1254.56  706.98
#Mann= 5 ,-1 , 0
       0     .08       0   53.73     .06       0  224.92     .06       0
  412.36    .032       0  881.69     .06       0
Levee=0,,,-1,976.83,723.55,,
#XS Ineff= 3 ,-1
       0  196.12  721.42  196.12  320.32  719.21  961.02    1253  722.83
Permanent Ineff=
       F       F       F
Bank Sta=412.36,881.69
XS Rating Curve= 0 ,0
Exp/Cntr=0.5,0.3

Type RM Length L Ch R = 1 ,246.8   ,390.62,921.98,1377.54
BEGIN DESCRIPTION:
Overbank geometry from 2011 City of Columbus LiDAR data.  Channel geometry from 2011 hydrographic survey by Resource International.
END DESCRIPTION:
XS GIS Cut Line= 2
1825936.45013878711793.1277875161825141.63412822712885.105043387
#Sta/Elev= 30
       0  737.51   11.24  737.63   74.97  737.47   86.21  733.48   101.2  728.58
   111.2   730.5  136.19  740.87  182.42  741.91  189.91  740.51  228.64  723.78
  282.37  716.46  301.11  701.79  314.18  697.53  323.54  688.85  344.25  689.27
  349.11  687.38  513.86  688.07  734.79  686.04  770.78  689.87  804.13  697.16
  830.86  702.86   849.6  704.14  870.84  713.96  899.57  722.93  910.82  721.62
  934.56  712.82  947.05  711.78 1028.26  712.52 1053.25  710.32 1350.61  708.82
#Mann= 7 ,-1 , 0
       0     .08       0   11.24     .06       0   86.21     .05       0
  182.42     .06       0  314.18    .032       0  804.13     .06       0
  899.57     .06       0
Levee=0,,,-1,900.46,723.02,,
#XS Ineff= 2 , 0
       0                  900.46       0  723.04
Permanent Ineff=
       F       F
Bank Sta=314.18,804.13
XS Rating Curve= 0 ,0
Exp/Cntr=0.5,0.3

Type RM Length L Ch R = 1 ,246.5   ,95.04,95.04,95.04
XS GIS Cut Line= 5
  1825704.643843  711666.7176072 1825179.9345914  711665.4731871
 1825030.2006389  711612.0835301 1824664.6524855  711715.1840457
 1824436.8537285  711819.3885617
#Sta/Elev= 30
    14.6   769.4   442.8   769.4   446.7   758.4   499.4   758.4   735.3   750.4
   775.8   744.5   951.2   738.4    1004   738.5  1158.6   729.5  2484.4   729.6
  2521.9   740.4  2742.1   743.5  2911.9   750.5  2965.1   743.4  2990.5   721.2
  3025.6   721.4  3050.4   718.3  3076.7   705.8  3103.3   696.1  3135.4   688.1
  3318.1   691.4  3396.1   685.6  3517.2   686.9  3564.1     684  3604.9   696.2
  3622.5     701  3666.9   720.5  5571.9   721.3  5577.7   741.4  5733.7   744.1
#Mann= 3 , 0 , 0
    14.6    .066       0  3103.3    .035       0  3604.9    .064       0
#Block Obstruct= 2 , 0
                            3800
Bank Sta=3103.3,3604.9
XS Rating Curve= 0 ,0
Exp/Cntr=0.3,0.1

Type RM Length L Ch R = 1 ,246.4   ,301.5,301.5,301.5
BEGIN DESCRIPTION:
REPEATED section.  I-70 East/West Bridge - Upstream Section
END DESCRIPTION:
XS GIS Cut Line= 5
  1827976.925716  711577.1068941 1825196.4739284   711570.512091
 1825033.5707109  711512.4265772 1824631.8047821  711625.7422955
 1824397.3351067  711732.9983146
#Sta/Elev= 30
  1323.1   724.4  2288.7   723.4  2305.5   732.6  2739.4   732.6  2757.9   723.6
  3138.9   723.5  3138.9   725.5  3490.9   723.6  3490.9   726.6  3648.5   726.4
  3655.2   723.7  3678.6   723.7  3726.3   727.3  3797.5   721.4  3858.4   709.6
    3971   705.6  4004.3   688.5  4153.2   685.1  4206.6   690.7  4241.4   691.4
  4334.1   686.1  4427.7   690.2  4478.7   711.8  4481.8   721.3    4488   721.6
    4488   730.4    4558   730.4  4581.5   733.3  4705.3   730.5  4916.5   730.6
#Mann= 3 , 0 , 0
  1323.1     .08       0  4004.3     .04       0  4427.7    .075       0
#XS Ineff= 2 , 0
       0  4004.3     724  4427.7       0     717
Permanent Ineff=
       F       F
#Block Obstruct= 2 , 0
                            4600
Bank Sta=4004.3,4427.7
XS Rating Curve= 0 ,0
Exp/Cntr=0.3,0.1

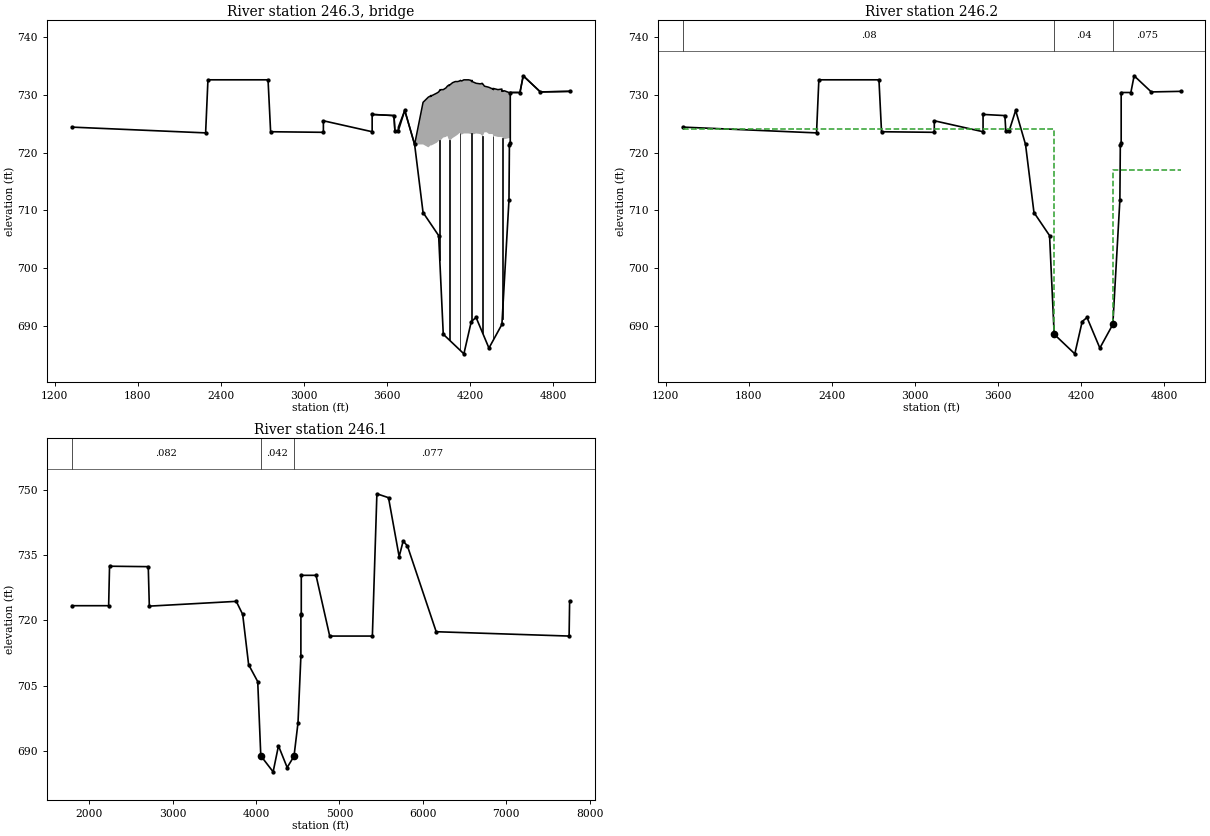
Type RM Length L Ch R = 3 ,246.3   ,,,
BEGIN DESCRIPTION:
Structure #5 Interstate 70/71 Bridge
END DESCRIPTION:
Bridge Culvert--1,0,-1,-1, 0
Deck Dist Width WeirC Skew NumUp NumDn MinLoCord MaxHiCord MaxSubmerge Is_Ogee
1,300,2.6,0, 69, 69, 734.4, , 0.95, 0, 0,0,,
  3490.9  3648.5  3655.2  3678.6  3679.9  3726.3  3797.5  3858.4  3896.5    3912
    3912  3915.9  3916.8  3957.8    3971  3976.4  3977.2  3981.1  3983.4  3988.8
  4004.3  4023.7  4033.8  4044.7  4044.7  4047.8  4050.9  4071.1  4091.2    4109
  4122.2    4123  4127.6  4128.4  4136.9  4153.2  4187.3  4205.1  4206.6  4208.2
  4212.8  4212.8  4241.4  4272.3  4285.5  4286.3  4289.3  4289.4  4301.6  4318.7
  4334.1  4361.9  4361.9  4366.6  4366.6  4399.1  4427.7  4427.9  4432.3  4432.3
  4445.5  4478.7  4481.8    4488    4488    4558  4581.5  4705.3  4916.5
   726.6   726.4   723.7   723.7   724.4   727.3   721.4   728.7   729.6   729.8
   729.7   729.9   729.8   730.3   730.5   730.7   730.7   730.9   730.8   730.9
   730.9   731.2   731.5   731.7   731.6   731.6   731.7   732.1   732.3   732.3
   732.4   732.4   732.5   732.5   732.4   732.6   732.6   732.5   732.4   732.3
   732.5   732.3     732   731.9     732   731.9   731.9   731.9   731.5   731.4
   731.3     731   731.1   730.9   731.1   730.9     731   730.6   730.7   730.6
   730.7   730.4   730.4   730.4   730.4   730.4   733.3   730.5   730.6
   726.6   726.4   723.7   723.7   724.4   727.3   721.4   721.4   720.9   721.2
   721.2   721.3   721.2   721.7     722   722.2   722.1   722.2   722.1   722.2
   722.6   722.7   722.9   722.2   722.4     722     722   722.5   722.8   723.1
   723.4   723.4   723.3   723.3   723.1   723.3   723.3   723.2   723.2   723.2
   723.5   723.1   723.3   723.2   722.9   722.9   722.8   722.8   723.5   723.5
   723.2   723.2   723.1   722.7   722.9   722.7   722.7   722.5   722.7   722.6
   722.3   722.5   722.5   722.5   730.4   730.4   733.3   730.5   730.6
  3490.9  3648.5  3655.2  3678.6  3679.9  3726.3  3797.5  3858.4  3896.5    3912
    3912  3915.9  3916.8  3957.8    3971  3976.4  3977.2  3981.1  3983.4  3988.8
  4004.3  4023.7  4033.8  4044.7  4044.7  4047.8  4050.9  4071.1  4091.2    4109
  4122.2    4123  4127.6  4128.4  4136.9  4153.2  4187.3  4205.1  4206.6  4208.2
  4212.8  4212.8  4241.4  4272.3  4285.5  4286.3  4289.3  4289.4  4301.6  4318.7
  4334.1  4361.9  4361.9  4366.6  4366.6  4399.1  4427.7  4427.9  4432.3  4432.3
  4445.5  4478.7  4481.8    4488    4488    4558  4581.5  4705.3  4916.5
   726.6   726.4   723.7   723.7   724.4   727.3   721.4   728.7   729.6   729.8
   729.7   729.9   729.8   730.3   730.5   730.7   730.7   730.9   730.8   730.9
   730.9   731.2   731.5   731.7   731.6   731.6   731.7   732.1   732.3   732.3
   732.4   732.4   732.5   732.5   732.4   732.6   732.6   732.5   732.4   732.3
   732.5   732.3     732   731.9     732   731.9   731.9   731.9   731.5   731.4
   731.3     731   731.1   730.9   731.1   730.9     731   730.6   730.7   730.6
   730.7   730.4   730.4   730.4   730.4   730.4   733.3   730.5   730.6
   726.6   726.4   723.7   723.7   724.4   727.3   721.4   721.4   720.9   721.2
   721.2   721.3   721.2   721.7     722   722.2   722.1   722.2   722.1   722.2
   722.6   722.7   722.9   722.2   722.4     722     722   722.5   722.8   723.1
   723.4   723.4   723.3   723.3   723.1   723.3   723.3   723.2   723.2   723.2
   723.5   723.1   723.3   723.2   722.9   722.9   722.8   722.8   723.5   723.5
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Pier Skew, UpSta & Num, DnSta & Num=  ,3914, 2 ,3914, 2 , 0 , 0 , 0 ,,
     4.8     3.9
   701.4   721.3
     4.8     3.9
   701.4   721.3
Pier Skew, UpSta & Num, DnSta & Num=  ,3979.2, 2 ,3979.2, 2 , 0 , 0 , 0 ,,
       7     3.9
   690.4   722.2
       7     3.9
   690.4   722.2
Pier Skew, UpSta & Num, DnSta & Num=  ,4046.3, 2 ,4046.3, 2 , 0 , 0 , 0 ,,
     6.2     3.1
   688.4   722.4
     6.2     3.1
   688.4   722.4
Pier Skew, UpSta & Num, DnSta & Num=  ,4125.3, 2 ,4125.3, 2 , 0 , 0 , 0 ,,
     6.2     4.6
   685.4   723.4
     6.2     4.6
   685.4   723.4
Pier Skew, UpSta & Num, DnSta & Num=  ,4210.5, 2 ,4210.5, 2 , 0 , 0 , 0 ,,
     6.2     4.6
   677.4   723.5
     6.2     4.6
   677.4   723.5
Pier Skew, UpSta & Num, DnSta & Num=  ,4287.8, 2 ,4287.8, 2 , 0 , 0 , 0 ,,
     3.9       3
   677.4   722.9
     3.9       3
   677.4   722.9
Pier Skew, UpSta & Num, DnSta & Num=  ,4364.3, 2 ,4364.3, 2 , 0 , 0 , 0 ,,
     4.7     4.7
   677.4   723.1
     4.7     4.7
   677.4   723.1
Pier Skew, UpSta & Num, DnSta & Num=  ,4430.1, 2 ,4430.1, 2 , 0 , 0 , 0 ,,
     4.6     4.4
   678.4   722.7
     4.6     4.4
   678.4   722.7
BR Coef=-1 , 0 , 0 ,, 0 ,,,0.8,-1,,0,
WSPro=,,,, 1 ,,,, 0 ,,,, 0 ,,,,-1 ,-1 ,-1 , 0 , 0 , 0 , 0 , 0
BC Design=,, 0 ,, 0 ,,,,,,
BC HTab HWMax=733.3
BC Use User HTab Curves=0
BC User HTab FreeFlow(D)= 0

Type RM Length L Ch R = 1 ,246.2   ,95.04,95.04,95.04
BEGIN DESCRIPTION:
I-70 East/West Bridge - Downstream Section
END DESCRIPTION:
XS GIS Cut Line= 3
  1827215.061426  711264.8230698 1824528.7206707  711242.9838746
 1824335.0471736   711138.166499
#Sta/Elev= 30
  1323.1   724.4  2288.7   723.4  2305.5   732.6  2739.4   732.6  2757.9   723.6
  3138.9   723.5  3138.9   725.5  3490.9   723.6  3490.9   726.6  3648.5   726.4
  3655.2   723.7  3678.6   723.7  3726.3   727.3  3797.5   721.4  3858.4   709.6
    3971   705.6  4004.3   688.5  4153.2   685.1  4206.6   690.7  4241.4   691.4
  4334.1   686.1  4427.7   690.2  4478.7   711.8  4481.8   721.3    4488   721.6
    4488   730.4    4558   730.4  4581.5   733.3  4705.3   730.5  4916.5   730.6
#Mann= 3 , 0 , 0
  1323.1     .08       0  4004.3     .04       0  4427.7    .075       0
#XS Ineff= 2 , 0
       0  4004.3     724  4427.7       0     717
Permanent Ineff=
       F       F
#Block Obstruct= 2 , 0
                            5645
Bank Sta=4004.3,4427.7
XS Rating Curve= 0 ,0
Exp/Cntr=0.3,0.1

Type RM Length L Ch R = 1 ,246.1   ,1671.92,1671.92,1671.92
BEGIN DESCRIPTION:
Taken from effective Model
END DESCRIPTION:
XS GIS Cut Line= 3
  1825004.674115  711151.8501986 1824553.1402413  711148.1792742
 1824380.2642747  711054.6174535
#Sta/Elev= 30
    1793   723.4  2233.9   723.4  2244.7   732.5  2708.8   732.4  2721.5   723.3
  3763.8   724.4  3840.6   721.4    3912   709.8    4021   705.9  4057.8   688.8
  4205.7   685.1  4269.7   691.1  4373.9   686.1    4456   688.7  4503.9   696.4
  4538.4   711.7  4538.5   721.5  4543.1   721.3  4543.1   730.4    4720   730.4
  4883.9   716.4  5395.4   716.4  5449.6   749.2  5588.9   748.3  5716.6   734.7
  5764.4   738.3  5815.2   737.2  6160.5   717.4  7753.8   716.4    7760   724.4
#Mann= 3 , 0 , 0
    1793    .082       0  4057.8    .042       0    4456    .077       0
#XS Ineff= 2 , 0
          4057.8   688.8    4456           688.7
Permanent Ineff=
       F       F
#Block Obstruct= 2 , 0
                            4710
Bank Sta=4057.8,4456
XS Rating Curve= 0 ,0
Exp/Cntr=0.3,0.1

--- FRA-70-1321R.g07 (geometry) ---

Geom Title=Prsd_Cndtn_3_Prfrrd_wo_dam_w_Crr_n
Program Version=4.10
BEGIN GEOM DESCRIPTION:
Vertical Datum = NAVD 88
Projection = State Plane Ohio South
END GEOM DESCRIPTION:

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
River Reach=SciotoRiver     ,SciotoRiver

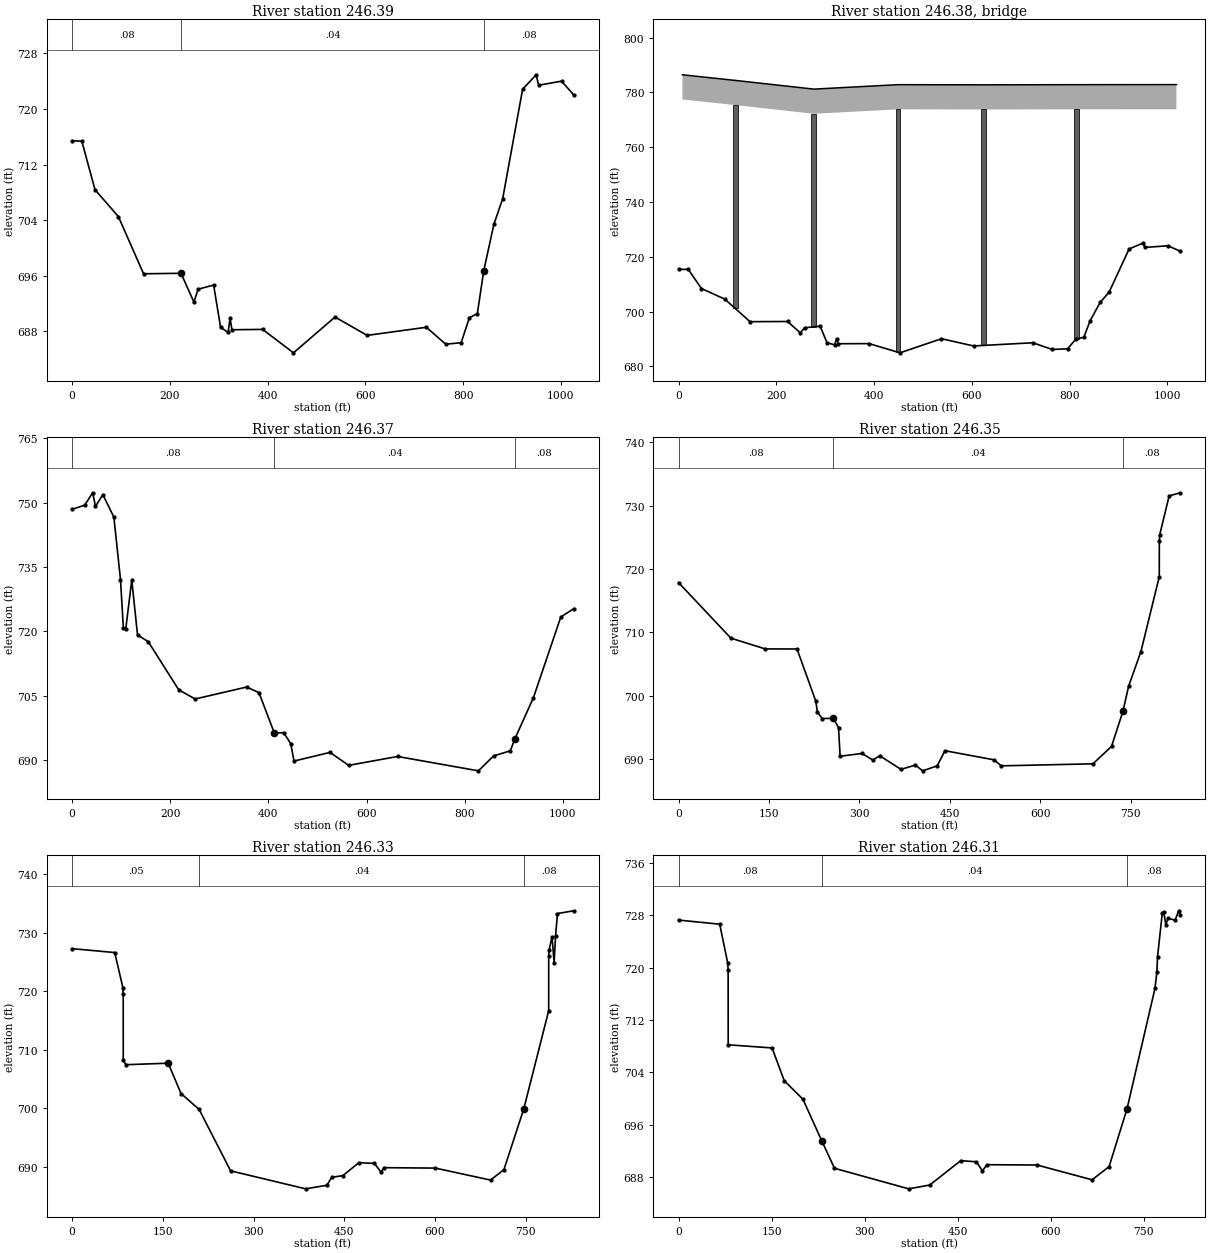
Type RM Length L Ch R = 1 ,246.39  ,65,113,110
XS GIS Cut Line= 6
      1825651.07       711942.18      1825563.07       711913.46
      1825121.78       711760.79      1824915.38       711693.74
       1824688.8       711625.07      1824434.68       711553.99
#Sta/Elev= 30
       0  715.42   19.96  715.36  46.921  708.38  94.743  704.52 146.286  696.29
  222.95  696.36 249.252  692.22 257.877  694.07  289.63  694.67 303.898  688.58
   319.3  687.85 323.279   689.9 327.138  688.24 389.854  688.29 453.046  684.92
 537.965  690.07 603.801  687.43 724.854   688.6 764.524  686.16   796.1  686.38
 812.908  689.97 829.194  690.57 842.289  696.71 862.964  703.39 881.027  707.08
 921.815  722.83 949.411  724.91 954.668  723.411001.477  723.991026.678     722
#Mann= 3 ,-1 , 0
       0     .08       0  222.95     .04       0 842.289     .08       0
Bank Sta=222.95,842.289
XS Rating Curve= 0 ,0
Skew Angle= 36.5
Exp/Cntr=0.3,0.1

Type RM Length L Ch R = 3 ,246.38  ,,,
BEGIN DESCRIPTION:
FRA-71-1503L I-71-SB
END DESCRIPTION:
Bridge Culvert--1,0,-1,-1, 0
Deck Dist Width WeirC Skew NumUp NumDn MinLoCord MaxHiCord MaxSubmerge Is_Ogee
1,109.5,2.6,36.5, 7, 7, , , 0.98, 0, 0,0,,
   8.033 116.043 276.814 448.985 623.473  813.821018.628
  786.41 784.353781.1778 782.801 782.738 782.801 782.829
  777.41 775.353772.1778 773.801 773.738 773.801 773.829
   8.045   166.6 327.372 500.092 678.103 877.1071014.403
  783.71 782.498 780.225 777.985 777.566779.2638781.5989
  774.71 773.498 771.225 768.985 768.566770.2639772.5989
Pier Skew, UpSta & Num, DnSta & Num=  ,116.043, 6 ,166.6, 6 , 0 , 0 , 0 ,,
      10      10      10      10       8       8
     650     693   695.2   700.2   700.2 775.353
      10      10      10      10       8       8
     650     693   695.2   700.2   700.2 773.498
Pier Skew, UpSta & Num, DnSta & Num=  ,276.814, 6 ,327.372, 6 , 0 , 0 , 0 ,,
      10      10      10      10       8       8
     650     693   695.2   700.2   700.2 772.178
      10      10      10      10       8       8
     650     693   695.2   700.2   700.2 771.225
Pier Skew, UpSta & Num, DnSta & Num=  ,448.985, 6 ,500.092, 6 , 0 , 0 , 0 ,,
      10      10      10      10       8       8
     650     693   695.2   700.2   700.2 773.801
      10      10      10      10       8       8
     650     693   695.2   700.2   700.2 768.985
Pier Skew, UpSta & Num, DnSta & Num=  ,623.473, 6 ,678.103, 6 , 0 , 0 , 0 ,,
      10      10      10      10       8       8
     650     693   695.2   700.2   700.2 773.738
      10      10      10      10       8       8
     650     693   695.2   700.2   700.2 768.566
Pier Skew, UpSta & Num, DnSta & Num=  ,813.82, 6 ,877.107, 6 , 0 , 0 , 0 ,,
      10      10      10      10       8       8
     650     693   695.2   700.2   700.2 773.801
      10      10      10      10       8       8
     650     693   695.2   700.2   700.2 770.264
BR Coef=-1 , 0 , 0 ,, 0 ,,,0.8,-1,,0,
WSPro=,,,, 1 ,,,, 0 ,,,, 0 ,,,,-1 ,-1 ,-1 , 0 , 0 , 0 , 0 , 0
BC Design=,, 0 ,, 0 ,,,,,,
BC Use User HTab Curves=0
BC User HTab FreeFlow(D)= 0

Type RM Length L Ch R = 1 ,246.37  ,25,79,66
XS GIS Cut Line= 6
      1825670.41       711880.14       1825573.3       711848.23
       1824747.1       711560.98      1824589.71       711502.83
       1824517.5       711472.18      1824473.41       711451.37
#Sta/Elev= 30
       0  748.46  25.699  749.43  41.961  752.32  47.717  749.15  62.741  751.88
  85.185  746.65  98.681  732.08 104.542  720.79 109.389  720.57  121.64  731.96
   133.4  719.15 155.152  717.61 217.339  706.36 250.795  704.23 355.715  707.01
 380.755  705.72 412.186  696.29 431.277  696.37 445.634  693.79 452.202  689.75
 525.626  691.77 563.648  688.75 663.286  690.82 827.948  687.47 858.977  690.96
 892.924  692.13 902.249  694.92 940.038  704.53 995.898  723.371022.458  725.29
#Mann= 3 ,-1 , 0
       0     .08       0 412.186     .04       0 902.249     .08       0
Bank Sta=412.186,902.249
XS Rating Curve= 0 ,0
Skew Angle= 36.5
Exp/Cntr=0.3,0.1

Type RM Length L Ch R = 1 ,246.35  ,76,89,68
XS GIS Cut Line= 6
      1825458.76       711781.91      1825331.26        711734.8
      1825027.19       711611.44      1824839.22       711536.51
      1824624.49       711454.18      1824449.47       711389.63
#Sta/Elev= 30
       0  717.86  86.895  709.07 143.781  707.37 196.562  707.36 227.816   699.1
 230.337  697.38 238.495  696.37 256.947   696.4  265.45  694.93 268.126  690.41
 304.554  690.85 322.421   689.8 333.808  690.49 369.106  688.33 393.001  689.02
 404.995   688.1 429.183  688.89 442.092  691.28 523.558  689.84 535.521  688.89
 687.698  689.21 718.498  691.97 737.465  697.54 746.891  701.51  767.22  706.95
 797.689  718.79 797.789  724.38 798.458  725.42 814.065  731.56 832.617  732.05
#Mann= 3 ,-1 , 0
       0     .08       0 256.947     .04       0 737.465     .08       0
Bank Sta=256.947,737.465
XS Rating Curve= 0 ,0
Skew Angle= 39.75
Exp/Cntr=0.3,0.1

Type RM Length L Ch R = 1 ,246.33  ,1.5,5,21.5
XS GIS Cut Line= 6
      1825430.43       711711.43      1825366.18       711687.23
      1825025.53       711549.27      1824810.24       711464.05
      1824603.22       711385.38        1824425.       711320.09
#Sta/Elev= 30
       0  727.31  70.526  726.64  83.958  720.65  84.542  719.57  84.642   708.2
   89.04  707.45 158.981  707.71 180.117  702.52 210.071   699.8 262.106  689.29
 386.243  686.21 421.302  686.82 429.229  688.19 447.581  688.46 474.145  690.69
 499.924  690.56 510.511   689.1 516.123  689.83 600.542  689.76 691.819  687.71
 713.946  689.49 746.715  699.87 787.948  716.68 788.009  726.03 788.593  727.02
 793.506  729.35 796.935  724.92 799.311  729.45 802.471  733.32  829.58  733.79
#Mann= 3 ,-1 , 0
       0     .05       0 210.071     .04       0 746.715     .08       0
Bank Sta=158.981,746.715
XS Rating Curve= 0 ,0
Skew Angle= 39.75
Exp/Cntr=0.3,0.1

Type RM Length L Ch R = 1 ,246.31  ,53,79.5,66
XS GIS Cut Line= 6
      1825427.66       711708.66      1825378.97       711690.29
      1825334.47       711673.05      1825289.29       711654.89
      1824490.33       711329.84      1824418.97       711299.53
#Sta/Elev= 30
       0  727.27  66.385  726.64  79.427  720.64  79.962  719.57  80.081  708.21
 150.762  707.73 170.448  702.72 200.575  699.89  230.91  693.53 251.428  689.34
 371.008   686.2  404.94  686.78 454.998  690.51  480.28  690.33 489.933  688.94
 496.986  689.89 577.996  689.84 666.705  687.58  694.12   689.6 723.058  698.44
 768.181  716.87 771.042  719.27 772.254   721.7 779.901  728.37 782.271  728.49
 785.534  726.55 789.004  727.56 800.538  727.25 806.223  728.69 808.943  727.99
#Mann= 3 ,-1 , 0
       0     .08       0  230.91     .04       0 723.058     .08       0
Bank Sta=230.91,723.058
XS Rating Curve= 0 ,0
Skew Angle= 42
Exp/Cntr=0.3,0.1

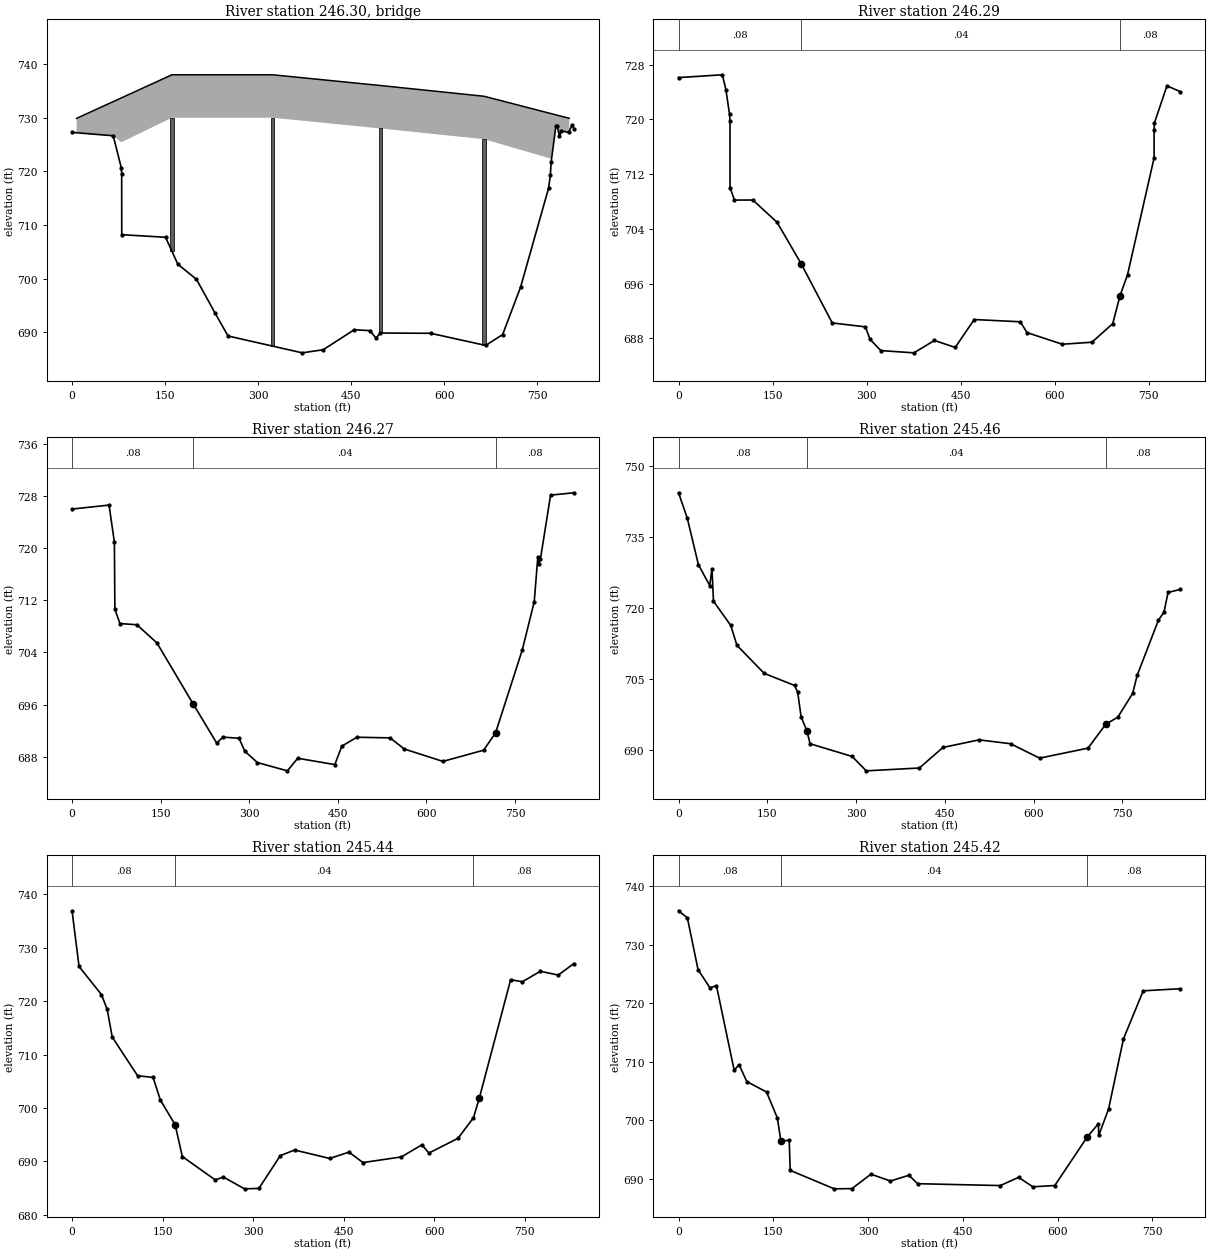
Type RM Length L Ch R = 3 ,246.30  ,,,
BEGIN DESCRIPTION:
FRA-70-1322L FRA-70-WB
END DESCRIPTION:
Bridge Culvert--1,0,-1,-1, 0
Deck Dist Width WeirC Skew NumUp NumDn MinLoCord MaxHiCord MaxSubmerge Is_Ogee
1,76.5,2.6,42, 6, 6, , , 0.98, 0, 0,0,,
   7.423 161.032 323.348 497.012 664.248 801.518
  729.89     738     738     736     734  729.89
  721.39     730     730     728     726  721.39
    7.44 163.496 325.811 499.475 660.804 792.804
  729.82     738     738     736     734  729.82
  721.32     730     730     728     726  721.32
Pier Skew, UpSta & Num, DnSta & Num=  ,161.032, 4 ,163.496, 4 , 0 , 0 , 0 ,,
     5.5     5.5       5       5
   649.5   697.2   697.2     730
     5.5     5.5       5       5
   649.5   697.2   697.2     730
Pier Skew, UpSta & Num, DnSta & Num=  ,323.348, 4 ,325.811, 4 , 0 , 0 , 0 ,,
     5.5     5.5       5       5
   648.5   697.2   697.2     730
     5.5     5.5       5       5
   648.5   697.2   697.2     730
Pier Skew, UpSta & Num, DnSta & Num=  ,497.012, 4 ,499.475, 4 , 0 , 0 , 0 ,,
     5.5     5.5       5       5
   645.5   697.2   697.2     728
     5.5     5.5       5       5
   645.5   697.2   697.2     728
Pier Skew, UpSta & Num, DnSta & Num=  ,664.248, 4 ,660.804, 4 , 0 , 0 , 0 ,,
     5.5     5.5       5       5
     645   697.2   697.2     726
     5.5     5.5       5       5
     645   697.2   697.2     726
BR Coef=-1 , 0 , 0 ,, 0 ,,,0.8,-1,,0,
WSPro=,,,, 1 ,,,, 0 ,,,, 0 ,,,,-1 ,-1 ,-1 , 0 , 0 , 0 , 0 , 0
BC Design=,, 0 ,, 0 ,,,,,,
BC Use User HTab Curves=0
BC User HTab FreeFlow(D)= 0

Type RM Length L Ch R = 1 ,246.29  ,6.5,42.5,56.5
XS GIS Cut Line= 6
      1825401.16       711642.22      1825312.85       711607.25
      1825197.97       711560.53      1824577.95       711308.34
      1824484.59       711269.97      1824404.37       711234.92
#Sta/Elev= 30
       0  726.12  69.885  726.53  75.726  724.28    81.3  720.75  82.043  719.78
  82.155  710.03  89.096  708.21 118.539  708.22 157.086  704.97 195.365  698.94
 245.163  690.25 297.964  689.68 305.351  687.87 322.495  686.21  375.31  685.88
 408.053  687.69  441.25  686.67 471.488  690.75 545.045  690.42 555.716  688.84
 611.957  687.14 659.273  687.43 692.455  690.15 704.145  694.26 716.013  697.29
 758.379  714.37 758.394  718.43 759.004  719.51 778.935  724.92 800.241  724.06
#Mann= 3 ,-1 , 0
       0     .08       0 195.365     .04       0 704.145     .08       0
Bank Sta=195.365,704.145
XS Rating Curve= 0 ,0
Skew Angle= 42
Exp/Cntr=0.3,0.1

Type RM Length L Ch R = 1 ,246.27  ,88.5,142.5,181
XS GIS Cut Line= 6
       1825385.5       711629.15      1825247.29       711574.58
      1825192.54       711551.32      1824984.67        711455.9
      1824558.31       711249.13      1824359.14       711147.47
#Sta/Elev= 30
       0  726.02  62.613  726.63  71.638  720.95  72.491  710.62  81.067  708.44
 109.789  708.26  143.68  705.47 204.997   696.1 244.856  690.09 255.439  691.01
 282.731  690.83 292.422  688.84  313.76   687.1 364.569  685.83  382.02  687.76
 444.842  686.79 456.668  689.62 482.268  690.99 538.507  690.89 562.466  689.18
 627.775  687.28 696.813     689 717.065  691.68 762.152  704.37 782.456   711.8
 788.538  718.66 790.096  717.65 792.927  718.34 810.145  728.16 849.541  728.52
#Mann= 3 ,-1 , 0
       0     .08       0 204.997     .04       0 717.065     .08       0
Bank Sta=204.997,717.065
XS Rating Curve= 0 ,0
Skew Angle= 41.5
Exp/Cntr=0.3,0.1

Type RM Length L Ch R = 1 ,245.46  ,37.5,93.5,6.5
XS GIS Cut Line= 6
      1825330.07       711512.21      1825008.91       711368.39
      1824651.57        711182.4      1824589.22       711147.61
      1824473.59       711072.51      1824342.96       710967.15
#Sta/Elev= 30
       0  744.42  14.777  739.05  33.546  729.22  52.719  724.77  56.509  728.37
  59.078  721.45  88.212  716.34   98.72  712.11 144.706  706.19 196.122  703.62
 201.334   702.2 207.109  696.98 216.755  694.07 222.245  691.29 293.366  688.59
 317.175  685.55 406.983  686.15 446.767   690.5 507.807  692.11  560.96  691.29
 610.092  688.24 691.983  690.36 721.881  695.43 742.118  696.89 767.328  701.95
 774.915  705.76 810.894  717.46 820.151  719.13 827.162  723.31 847.855  723.97
#Mann= 3 ,-1 , 0
       0     .08       0 216.755     .04       0 721.881     .08       0
Bank Sta=216.755,721.881
XS Rating Curve= 0 ,0
Skew Angle= 41.5
Exp/Cntr=0.3,0.1

Type RM Length L Ch R = 1 ,245.44  ,92.7,87.5,178.2
XS GIS Cut Line= 6
      1825257.45       711441.41       1824686.9       711126.91
      1824476.62       711015.64      1824341.26        710959.8
      1824278.08        710941.9      1824205.35       710928.08
#Sta/Elev= 30
       0  736.94  11.533  726.51  48.642  721.25  58.195  718.47  66.574  713.28
 108.541  706.05 134.273  705.73 146.187  701.52 170.759  696.87 182.667  690.92
 237.157  686.54 250.676  687.08 285.706  684.87 309.536  684.95 345.012  691.09
 368.636  692.14 426.852  690.56 458.799  691.74 481.893  689.79 545.632  690.85
 579.637  693.12 591.155  691.57 639.387  694.33 664.999  698.19 674.891  701.94
 726.588  724.03 745.962  723.65 775.845  725.61 805.515   724.9  831.31  727.06
#Mann= 3 ,-1 , 0
       0     .08       0 170.759     .04       0 664.999     .08       0
Bank Sta=170.759,674.891
XS Rating Curve= 0 ,0
Skew Angle= 45
Exp/Cntr=0.3,0.1

Type RM Length L Ch R = 1 ,245.42  ,755.6,402.5,22.2
XS GIS Cut Line= 6
      1825222.91       711355.31      1824672.33       711048.11
      1824492.65       710940.63       1824369.1       710857.66
      1824318.29       710813.84      1824273.83       710763.52
#Sta/Elev= 30
       0   735.8  14.029  734.58  30.893  725.73  49.717  722.62  59.956     723
  88.063  708.52  95.707  709.49 108.003  706.59 139.251   704.8  156.37  700.36
 162.019  696.38 175.157  696.56 176.692   691.4 246.391  688.24 274.421  688.28
 304.501  690.75 335.204  689.58 364.605  690.56  378.33  689.12 509.188   688.8
 538.094  690.21 560.665  688.59 595.391  688.81 646.515  697.07 664.362  699.38
 664.977   697.4  680.47  701.87 704.102   713.9 735.377  722.11 794.067  722.47
#Mann= 3 ,-1 , 0
       0     .08       0 162.019     .04       0 646.515     .08       0
Bank Sta=162.019,646.515
XS Rating Curve= 0 ,0
Skew Angle= 45
Exp/Cntr=0.3,0.1