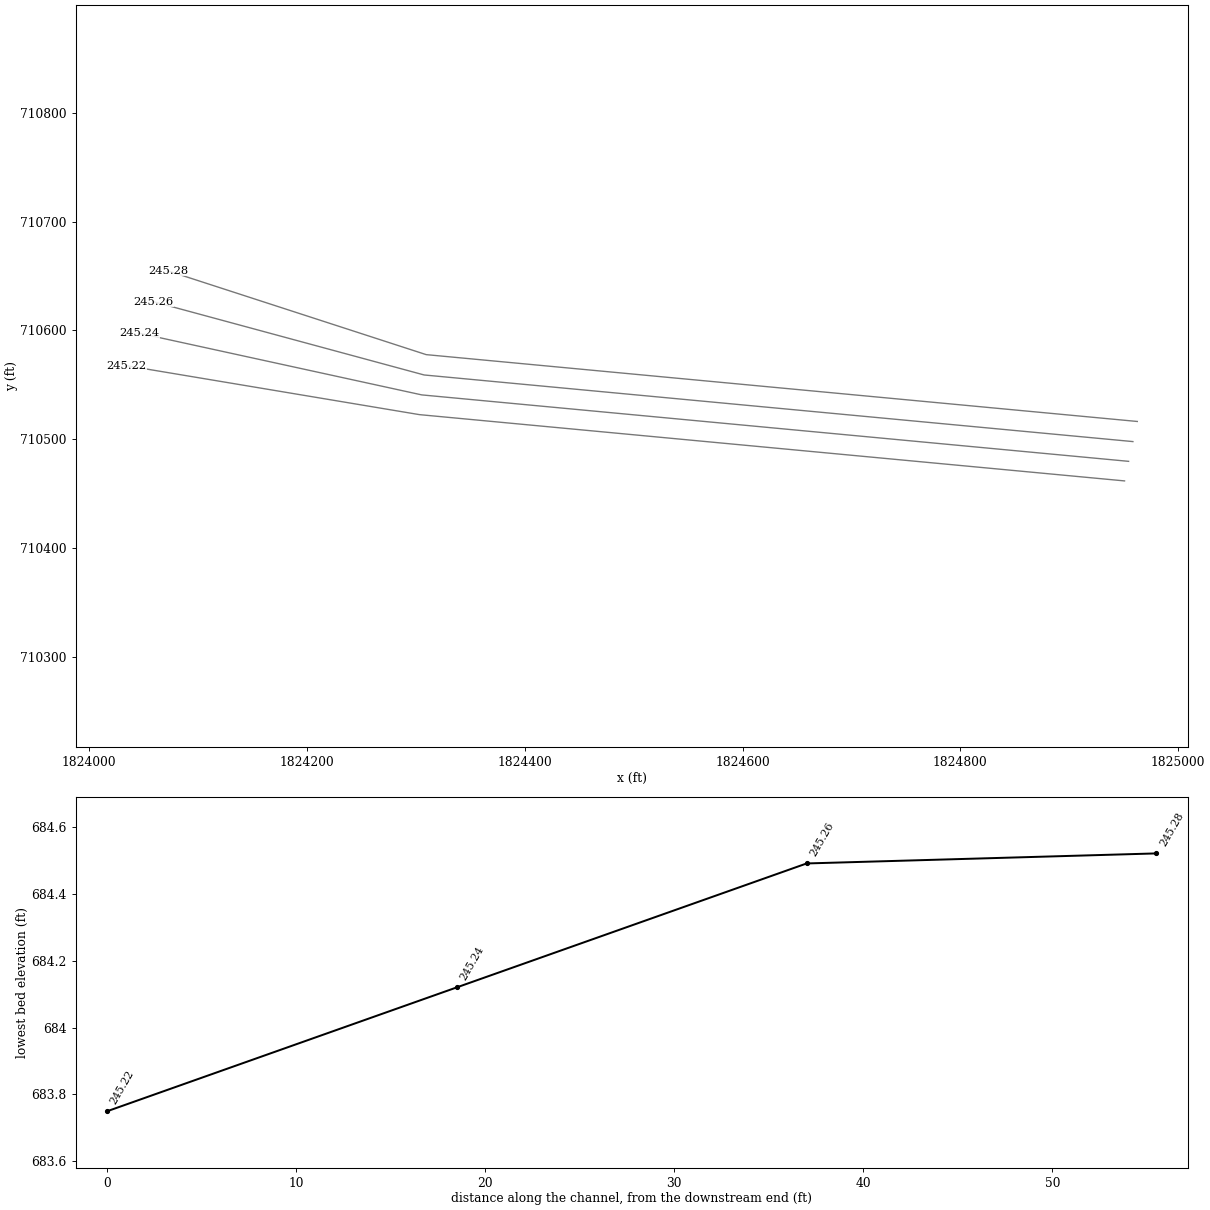
HEC-RAS study FRA-70-1321R.prj: FRA-70-1321R

--- FRA-70-1321R.g07 (geometry) --- (continued)

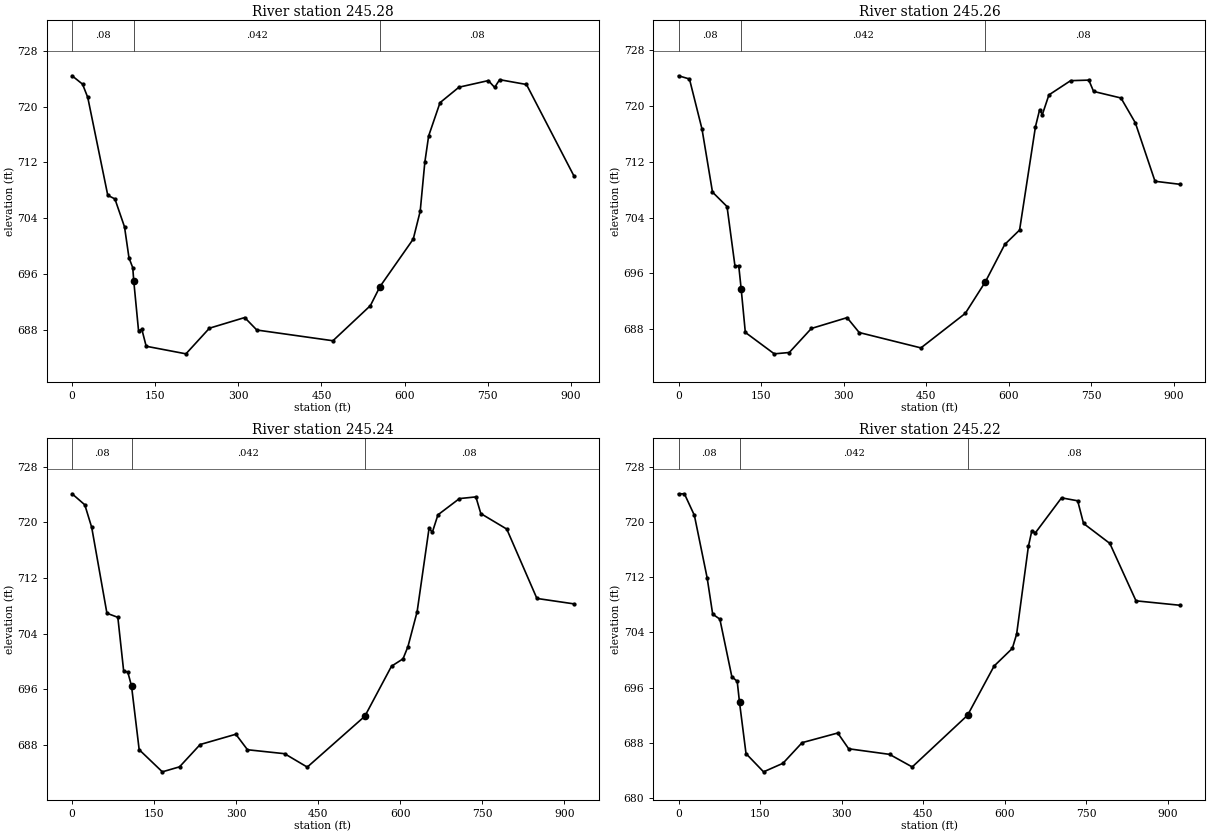
Type RM Length L Ch R = 1 ,245.28  ,18.5,18.5,31.5
XS GIS Cut Line= 4
      1824962.49       710516.15      1824633.18       710547.14
      1824309.49       710577.61      1824072.24        710654.7
#Sta/Elev= 30
       0  724.44   18.86  723.24   28.31  721.33   64.42  707.28    77.3  706.76
   94.65  702.74  102.72  698.29  109.52  696.88  111.34  694.94  119.97  687.81
  125.84  688.05  133.72  685.61  205.49  684.52   247.8   688.2  311.45  689.73
  333.33  687.94  470.66   686.4  538.22  691.44  555.51  694.17  615.59     701
   628.1  704.99  636.43     712  643.33   715.8  663.87  720.58  698.06   722.8
  751.11  723.75  762.39  722.77  771.42  723.88  819.85  723.19  905.35  710.08
#Mann= 3 ,-1 , 0
       0     .08       0  111.34    .042       0  555.51     .08       0
Bank Sta=111.34,555.51
XS Rating Curve= 0 ,0
Exp/Cntr=0.3,0.1

Type RM Length L Ch R = 1 ,245.26  ,18.5,18.5,31.5
XS GIS Cut Line= 4
      1824958.46       710497.65      1824631.42       710528.43
      1824307.58       710558.91       1824058.6       710626.41
#Sta/Elev= 30
       0  724.29   19.84  723.83   42.65  716.66   61.69  707.64   88.12  705.57
  102.54  697.06  109.38  697.11  113.82  693.77  121.35  687.56  173.95  684.49
  201.17  684.68  241.33  688.12  306.21  689.67  328.27  687.54  440.42  685.34
  521.02  690.28  557.73  694.83  592.76  700.15  619.66  702.21  648.56  717.02
  656.13  719.44  660.95  718.72  672.95  721.55  712.38  723.59  745.46  723.67
  754.14  722.05  803.87  721.11  830.01  717.55  865.74  709.19  911.73  708.75
#Mann= 3 ,-1 , 0
       0     .08       0  113.82    .042       0  557.73     .08       0
Bank Sta=113.82,557.73
XS Rating Curve= 0 ,0
Exp/Cntr=0.3,0.1

Type RM Length L Ch R = 1 ,245.24  ,18.5,18.5,23
XS GIS Cut Line= 4
      1824954.51       710479.49      1824629.69       710510.07
       1824305.4       710540.59      1824045.85       710597.34
#Sta/Elev= 30
       0  724.13   23.31  722.54   35.95  719.28   63.74  706.94    83.7  706.35
   94.31  698.66     102  698.45  108.73  696.47  122.71  687.31  165.08  684.12
  196.54  684.84  234.25  688.05  299.47  689.53  320.78   687.3  388.68  686.73
  430.12   684.8  535.48  692.13  584.17  699.32  605.23  700.38  614.25  702.14
  631.03  707.16  652.93  719.21  658.81  718.58  669.09   721.1   708.4  723.44
  738.49  723.68  747.52  721.28  794.95  719.05  850.07  709.07  917.66  708.29
#Mann= 3 ,-1 , 0
       0     .08       0  108.73    .042       0  535.48     .08       0
Bank Sta=108.73,535.48
XS Rating Curve= 0 ,0
Exp/Cntr=0.3,0.1

Type RM Length L Ch R = 1 ,245.22  ,785,973.5,1273
XS GIS Cut Line= 4
      1824950.77       710461.49      1824627.98       710491.87
      1824303.25       710522.44      1824034.03       710567.49
#Sta/Elev= 30
       0  724.14   10.85  724.13   29.15  721.01   52.74  711.89   62.81  706.66
   76.04  705.93   98.09  697.57  107.96   696.9  112.19  693.85  124.16   686.4
  156.47  683.75  192.13  684.99  227.41  687.99  292.96  689.39  313.07   687.1
  388.24  686.29  430.02  684.46  531.83  691.97  580.69  699.12   614.2  701.68
  622.15  703.76  643.75  716.49  650.14  718.77  656.46  718.45  704.77  723.55
  734.47  723.12  745.24  719.83  793.63  716.93  841.78  708.59  923.35  707.94
#Mann= 3 ,-1 , 0
       0     .08       0  112.19    .042       0  531.83     .08       0
Bank Sta=112.19,531.83
XS Rating Curve= 0 ,0
Exp/Cntr=0.3,0.1

--- FRA-70-1321R.g08 (geometry) ---

Geom Title=Prpsd_Cndtn_1_without_dam
Program Version=4.10
BEGIN GEOM DESCRIPTION:
Vertical Datum = NAVD 88
Projection = State Plane Ohio South
END GEOM DESCRIPTION:

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
River Reach=SciotoRiver     ,SciotoRiver

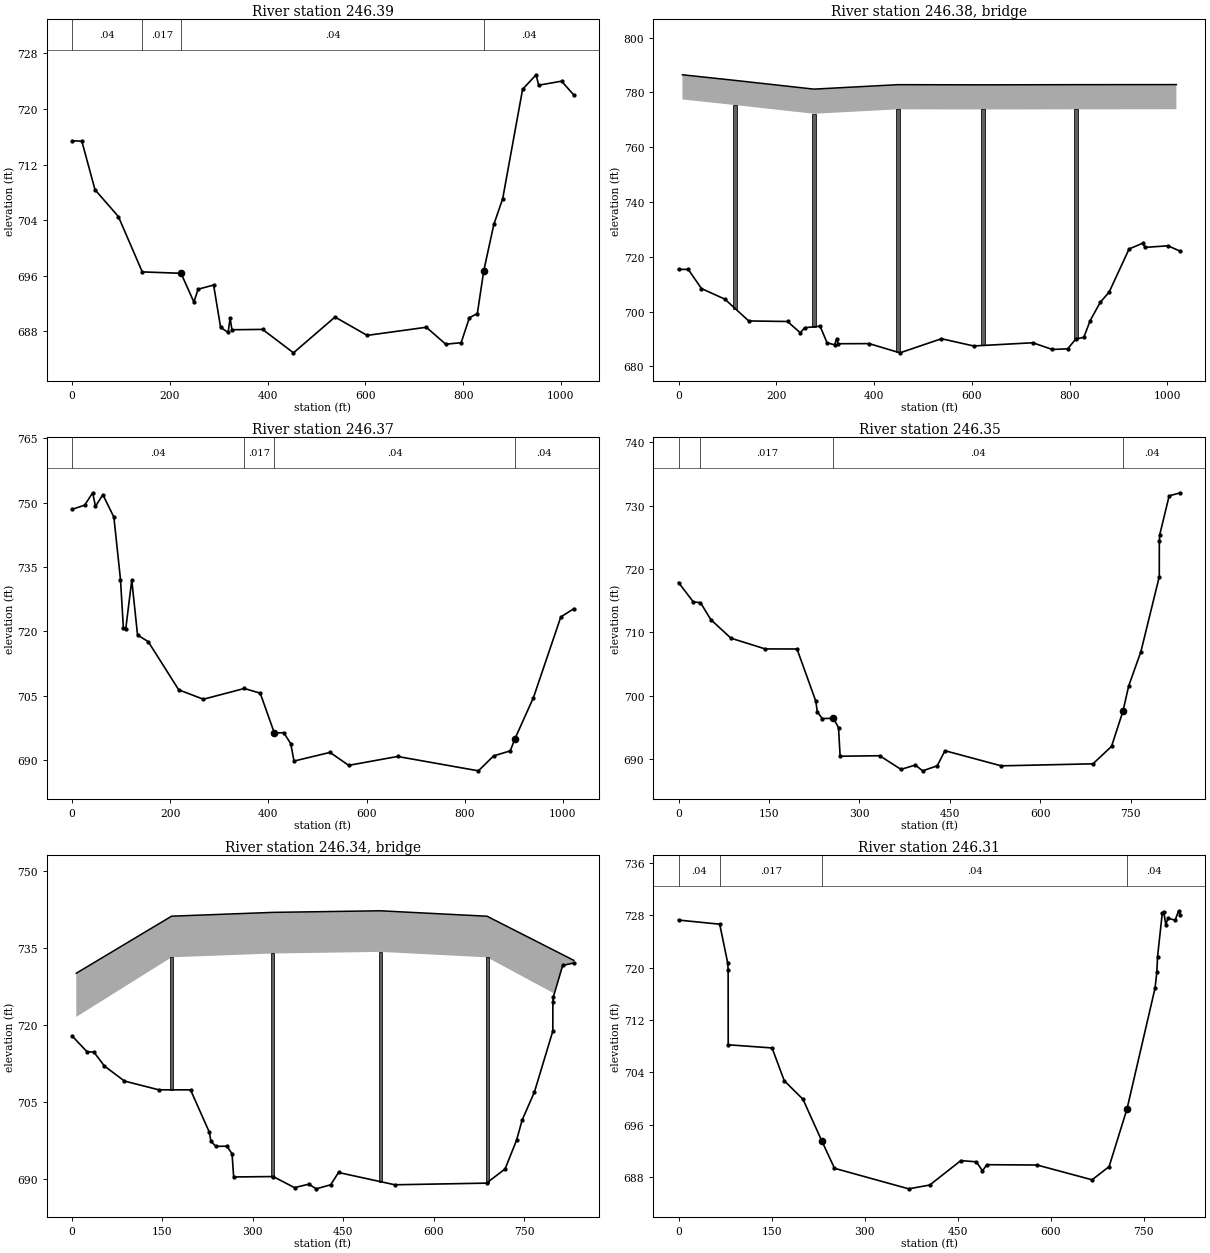
Type RM Length L Ch R = 1 ,246.39  ,65,113,110
XS GIS Cut Line= 6
      1825651.07       711942.18      1825563.07       711913.46
      1825121.78       711760.79      1824915.38       711693.74
       1824688.8       711625.07      1824434.68       711553.99
#Sta/Elev= 30
       0  715.42   19.96  715.36  46.921  708.38  94.743  704.52 143.617  696.56
  222.95  696.36 249.252  692.22 257.877  694.07  289.63  694.67 303.898  688.58
   319.3  687.85 323.279   689.9 327.138  688.24 389.854  688.29 453.046  684.92
 537.965  690.07 603.801  687.43 724.854   688.6 764.524  686.16   796.1  686.38
 812.908  689.97 829.194  690.57 842.289  696.71 862.964  703.39 881.027  707.08
 921.815  722.83 949.411  724.91 954.668  723.411001.477  723.991026.678     722
#Mann= 4 ,-1 , 0
       0     .04       0 143.617    .017       0  222.95     .04       0
 842.289     .04       0
#XS Ineff= 2 , 0
       0   8.473                       0
Permanent Ineff=
       T       F
Bank Sta=222.95,842.289
XS Rating Curve= 0 ,0
Skew Angle= 36.5
Exp/Cntr=0.3,0.1

Type RM Length L Ch R = 3 ,246.38  ,,,
BEGIN DESCRIPTION:
FRA-71-1503L (RC5) I-71-SB
END DESCRIPTION:
Bridge Culvert--1,0,-1,-1, 0
Deck Dist Width WeirC Skew NumUp NumDn MinLoCord MaxHiCord MaxSubmerge Is_Ogee
1,109.5,2.6,36.5, 7, 7, , , 0.98, 0, 0,0,,
   8.033 116.043 276.814 448.985 623.473  813.821018.628
  786.41 784.353781.1778 782.801 782.738 782.801 782.829
  777.41 775.353772.1778 773.801 773.738 773.801 773.829
   8.045   166.6 327.372 500.092 678.103 877.1071014.403
  783.71 782.498 780.225 777.985 777.566779.2638781.5989
  774.71 773.498 771.225 768.985 768.566770.2639772.5989
Pier Skew, UpSta & Num, DnSta & Num=  ,116.043, 4 ,166.6, 4 , 0 , 0 , 0 ,,
     7.5     7.5       7       7
     650   696.3   696.3 775.353
     7.5     7.5       7       7
     650   696.3   696.3 773.498
Pier Skew, UpSta & Num, DnSta & Num=  ,276.814, 4 ,327.372, 4 , 0 , 0 , 0 ,,
     7.5     7.5       7       7
     650   696.3   696.3 772.178
     7.5     7.5       7       7
     650   696.3   696.3 771.225
Pier Skew, UpSta & Num, DnSta & Num=  ,448.985, 4 ,500.092, 4 , 0 , 0 , 0 ,,
     7.5     7.5       7       7
     650   696.3   696.3 773.801
     7.5     7.5       7       7
     650   696.3   696.3 768.985
Pier Skew, UpSta & Num, DnSta & Num=  ,623.473, 4 ,678.103, 4 , 0 , 0 , 0 ,,
     7.5     7.5       7       7
     650   696.3   696.3 773.738
     7.5     7.5       7       7
     650   696.3   696.3 768.566
Pier Skew, UpSta & Num, DnSta & Num=  ,813.82, 4 ,877.107, 4 , 0 , 0 , 0 ,,
     7.5     7.5       7       7
     650   696.3   696.3 773.801
     7.5     7.5       7       7
     650   696.3   696.3 770.264
BR Coef=-1 , 0 , 0 ,, 0 ,,,0.8,-1,,0,
WSPro=,,,, 1 ,,,, 0 ,,,, 0 ,,,,-1 ,-1 ,-1 , 0 , 0 , 0 , 0 , 0
BC Design=,, 0 ,, 0 ,,,,,,
BC Use User HTab Curves=0
BC User HTab FreeFlow(D)= 0

Type RM Length L Ch R = 1 ,246.37  ,25,79,66
XS GIS Cut Line= 6
      1825670.41       711880.14       1825573.3       711848.23
       1824747.1       711560.98      1824589.71       711502.83
       1824517.5       711472.18      1824473.41       711451.37
#Sta/Elev= 30
       0  748.46  25.699  749.43  41.961  752.32  47.717  749.15  62.741  751.88
  85.185  746.65  98.681  732.08 104.542  720.79 109.389  720.57  121.64  731.96
   133.4  719.15 155.152  717.61 217.339  706.36 267.564  704.17  351.02  706.68
 383.391  705.58 412.186  696.29 431.277  696.37 445.634  693.79 452.202  689.75
 525.626  691.77 563.648  688.75 663.286  690.82 827.948  687.47 858.977  690.96
 892.924  692.13 902.249  694.92 940.038  704.53 995.898  723.371022.458  725.29
#Mann= 4 ,-1 , 0
       0     .04       0  351.02    .017       0 412.186     .04       0
 902.249     .04       0
Bank Sta=412.186,902.249
XS Rating Curve= 0 ,0
Skew Angle= 36.5
Exp/Cntr=0.3,0.1

Type RM Length L Ch R = 1 ,246.35  ,76,89,68
XS GIS Cut Line= 6
      1825458.76       711781.91      1825331.26        711734.8
      1825027.19       711611.44      1824839.22       711536.51
      1824624.49       711454.18      1824449.47       711389.63
#Sta/Elev= 30
       0  717.86  24.534   714.8   36.42  714.68  53.519  712.01  86.895  709.07
 143.781  707.37 196.562  707.36 227.816   699.1 230.337  697.38 238.495  696.37
 256.947   696.4  265.45  694.93 268.126  690.41 333.808  690.49 369.106  688.33
 393.001  689.02 404.995   688.1 429.183  688.89 442.092  691.28 535.521  688.89
 687.698  689.21 718.498  691.97 737.465  697.54 746.891  701.51  767.22  706.95
 797.689  718.79 797.789  724.38 798.458  725.42 814.065  731.56 832.617  732.05
#Mann= 4 ,-1 , 0
       0     .04       0   36.42    .017       0 256.947     .04       0
 737.465     .04       0
#XS Ineff= 2 , 0
       0       0                       0
Permanent Ineff=
       T       F
Bank Sta=256.947,737.465
XS Rating Curve= 0 ,0
Skew Angle= 39.75
Exp/Cntr=0.3,0.1

Type RM Length L Ch R = 3 ,246.34  ,,,
BEGIN DESCRIPTION:
FRA-70-1323C (RC4) Ramp D3
END DESCRIPTION:
Bridge Culvert--1,0,-1,-1, 0
Deck Dist Width WeirC Skew NumUp NumDn MinLoCord MaxHiCord MaxSubmerge Is_Ogee
1,86,2.6,39.75, 6, 6, , , 0.98, 0, 0,0,,
   6.995 165.108 333.036 511.631 688.573 832.614
  730.05  741.15  741.89   742.2  741.14 732.552
  721.55  733.15  733.89   734.2  733.14 724.052
   8.417 168.227 336.115 514.121 684.263  822.43
  729.98  741.15  741.89   742.2  741.14 734.306
  721.48  733.15  733.89   734.2  733.14 725.806
Pier Skew, UpSta & Num, DnSta & Num=  ,165.108, 4 ,168.227, 4 , 0 , 0 , 0 ,,
       5       5       4       4
     650   696.3   696.3  733.15
       5       5       4       4
     650   696.3   696.3  733.15
Pier Skew, UpSta & Num, DnSta & Num=  ,333.036, 4 ,336.115, 4 , 0 , 0 , 0 ,,
       5       5       4       4
     650   696.3   696.3  733.89
       5       5       4       4
     650   696.3   696.3  733.89
Pier Skew, UpSta & Num, DnSta & Num=  ,511.631, 4 ,514.121, 4 , 0 , 0 , 0 ,,
       5       5       4       4
     650   696.3   696.3   734.2
       5       5       4       4
     650   696.3   696.3   734.2
Pier Skew, UpSta & Num, DnSta & Num=  ,688.573, 4 ,684.263, 4 , 0 , 0 , 0 ,,
       5       5       4       4
     650   696.3   696.3  733.14
       5       5       4       4
     650     696   696.3  733.14
BR Coef=-1 , 0 , 0 ,, 0 ,,,0.8,-1,,0,
WSPro=,,,, 1 ,,,, 0 ,,,, 0 ,,,,-1 ,-1 ,-1 , 0 , 0 , 0 , 0 , 0
BC Design=,, 0 ,, 0 ,,,,,,
BC Use User HTab Curves=0
BC User HTab FreeFlow(D)= 0

Type RM Length L Ch R = 1 ,246.31  ,53,79.5,66
XS GIS Cut Line= 6
      1825427.66       711708.66      1825378.97       711690.29
      1825334.47       711673.05      1825289.29       711654.89
      1824490.33       711329.84      1824418.97       711299.53
#Sta/Elev= 30
       0  727.27  66.385  726.64  79.427  720.64  79.962  719.57  80.081  708.21
 150.762  707.73 170.448  702.72 200.575  699.89  230.91  693.53 251.428  689.34
 371.008   686.2  404.94  686.78 454.998  690.51  480.28  690.33 489.933  688.94
 496.986  689.89 577.996  689.84 666.705  687.58  694.12   689.6 723.058  698.44
 768.181  716.87 771.042  719.27 772.254   721.7 779.901  728.37 782.271  728.49
 785.534  726.55 789.004  727.56 800.538  727.25 806.223  728.69 808.943  727.99
#Mann= 4 ,-1 , 0
       0     .04       0  66.385    .017       0  230.91     .04       0
 723.058     .04       0
Bank Sta=230.91,723.058
XS Rating Curve= 0 ,0
Skew Angle= 42
Exp/Cntr=0.3,0.1

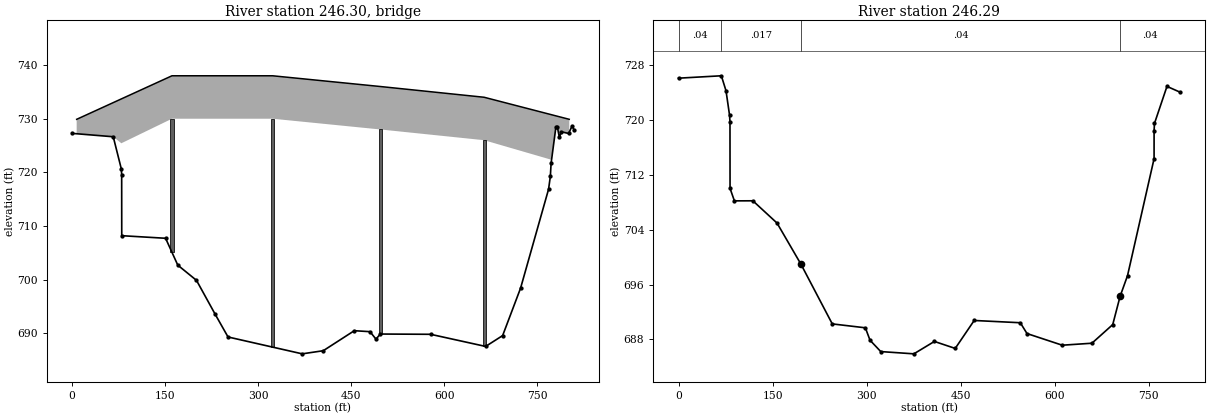
Type RM Length L Ch R = 3 ,246.30  ,,,
BEGIN DESCRIPTION:
FRA-70-1322L (RC3 ) I-70-WB
END DESCRIPTION:
Bridge Culvert--1,0,-1,-1, 0
Deck Dist Width WeirC Skew NumUp NumDn MinLoCord MaxHiCord MaxSubmerge Is_Ogee
1,76.5,2.6,42, 6, 6, , , 0.98, 0, 0,0,,
   7.423 161.032 323.348 497.012 664.248 801.518
  729.89     738     738     736     734  729.89
  721.39     730     730     728     726  721.39
    7.44 163.496 325.811 499.475 660.804 792.804
  729.82     738     738     736     734  729.82
  721.32     730     730     728     726  721.32
Pier Skew, UpSta & Num, DnSta & Num=  ,161.032, 4 ,163.496, 4 , 0 , 0 , 0 ,,
       5       5       4       4
     650   696.3   696.3     730
       5       5       4       4
     650   696.3   696.3     730
Pier Skew, UpSta & Num, DnSta & Num=  ,323.348, 4 ,325.811, 4 , 0 , 0 , 0 ,,
       5       5       4       4
     650   696.3   696.3     730
       5       5       4       4
     650   696.3   696.3     730
Pier Skew, UpSta & Num, DnSta & Num=  ,497.012, 4 ,499.475, 4 , 0 , 0 , 0 ,,
       5       5       4       4
     650   696.3   696.3     728
       5       5       4       4
     650   696.3   696.3     728
Pier Skew, UpSta & Num, DnSta & Num=  ,664.248, 4 ,660.804, 4 , 0 , 0 , 0 ,,
       5       5       4       4
     650   696.3   696.3     726
       5       5       4       4
     650   696.3   696.3     726
BR Coef=-1 , 0 , 0 ,, 0 ,,,0.8,-1,,0,
WSPro=,,,, 1 ,,,, 0 ,,,, 0 ,,,,-1 ,-1 ,-1 , 0 , 0 , 0 , 0 , 0
BC Design=,, 0 ,, 0 ,,,,,,
BC Use User HTab Curves=0
BC User HTab FreeFlow(D)= 0

Type RM Length L Ch R = 1 ,246.29  ,6.5,42.5,56.5
XS GIS Cut Line= 6
      1825401.16       711642.22      1825312.85       711607.25
      1825197.97       711560.53      1824577.95       711308.34
      1824484.59       711269.97      1824404.37       711234.92
#Sta/Elev= 30
       0  726.12  68.288  726.47  75.726  724.28    81.3  720.75  82.043  719.78
  82.155  710.03  89.096  708.21 118.539  708.22 157.086  704.97 195.365  698.94
 245.163  690.25 297.964  689.68 305.351  687.87 322.495  686.21  375.31  685.88
 408.053  687.69  441.25  686.67 471.488  690.75 545.045  690.42 555.716  688.84
 611.957  687.14 659.273  687.43 692.455  690.15 704.145  694.26 716.013  697.29
 758.379  714.37 758.394  718.43 759.004  719.51 778.935  724.92 800.241  724.06
#Mann= 4 ,-1 , 0
       0     .04       0  68.288    .017       0 195.365     .04       0
 704.145     .04       0
Bank Sta=195.365,704.145
XS Rating Curve= 0 ,0
Skew Angle= 42
Exp/Cntr=0.3,0.1