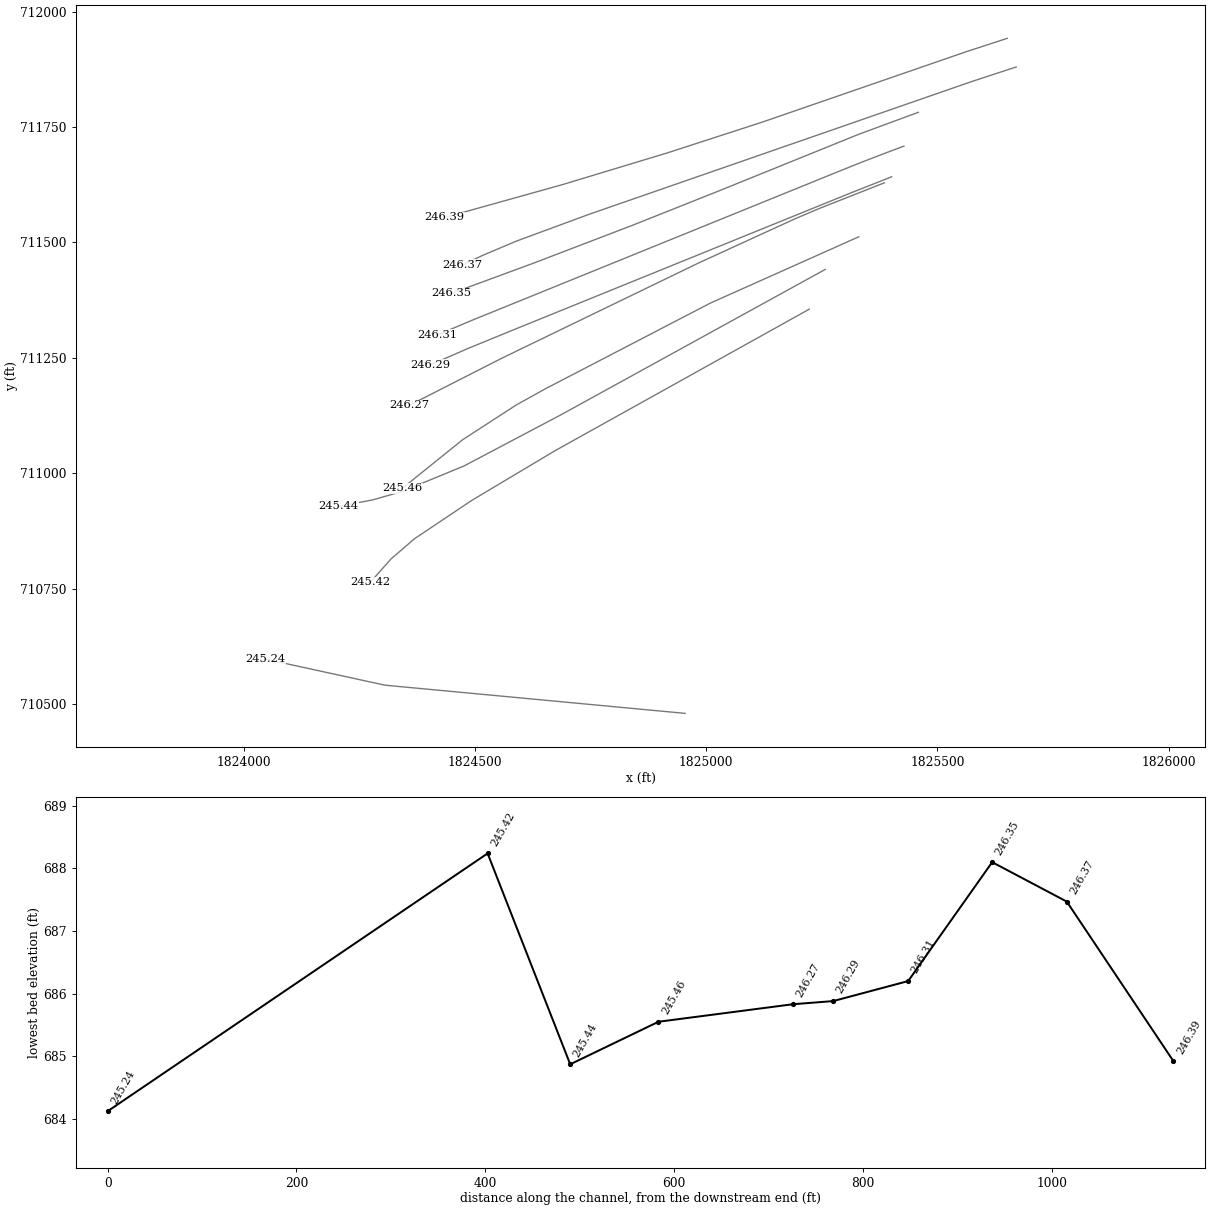
HEC-RAS study FRA-70-1321R.prj: FRA-70-1321R

--- FRA-70-1321R.g10 (geometry) --- (continued)

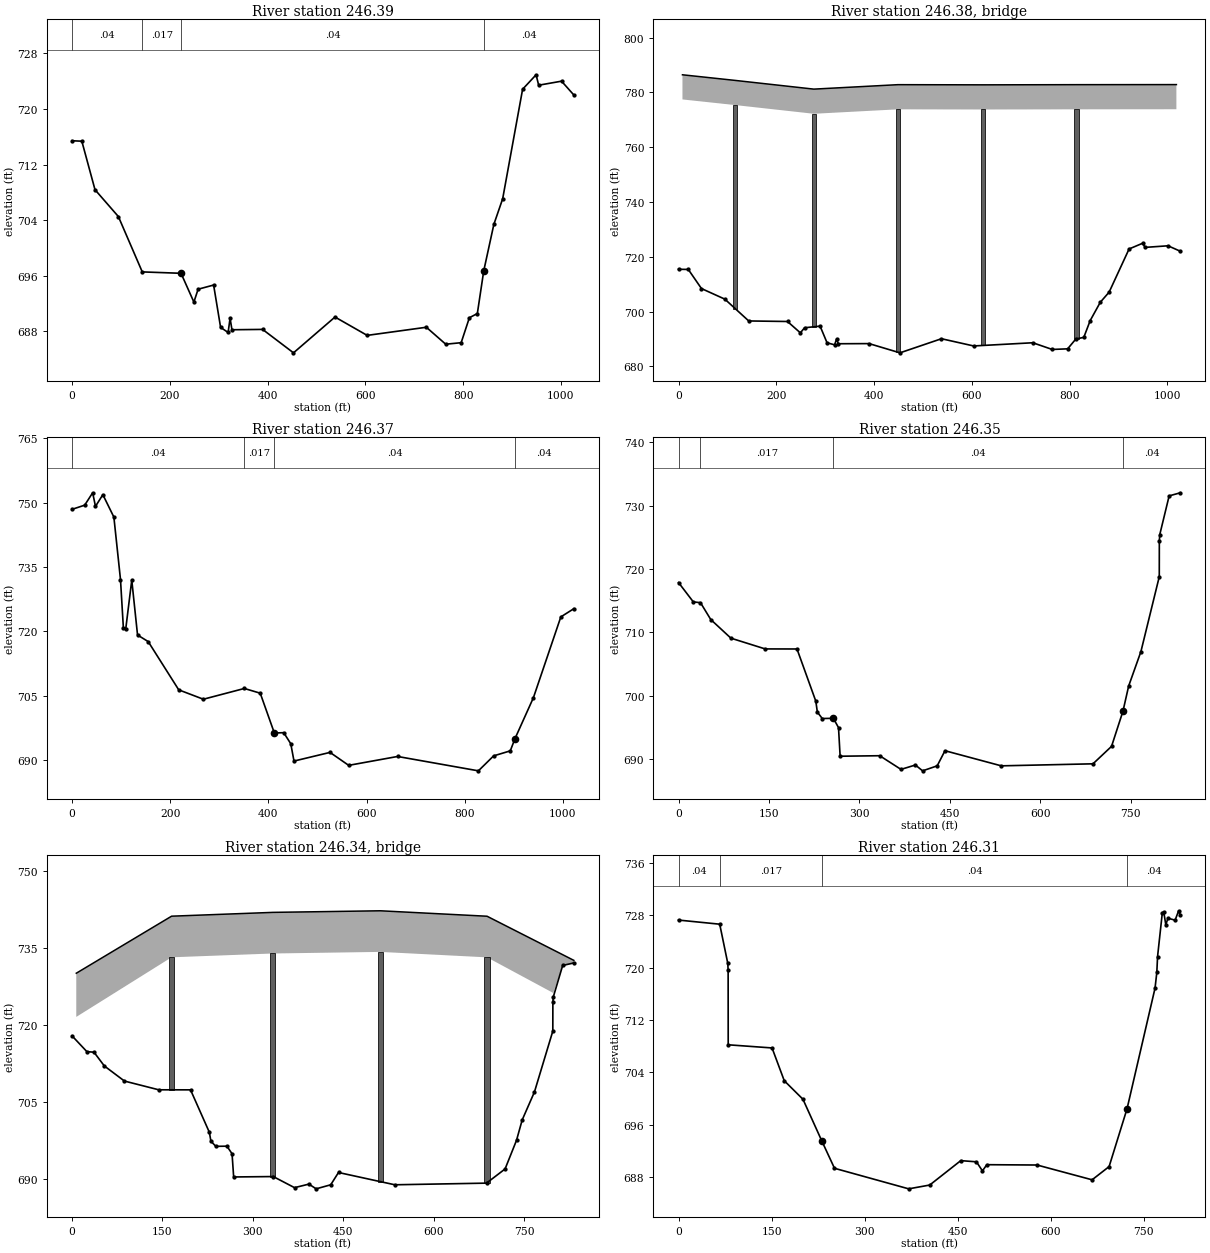
Type RM Length L Ch R = 1 ,246.39  ,65,113,110
XS GIS Cut Line= 6
      1825651.07       711942.18      1825563.07       711913.46
      1825121.78       711760.79      1824915.38       711693.74
       1824688.8       711625.07      1824434.68       711553.99
#Sta/Elev= 30
       0  715.42   19.96  715.36  46.921  708.38  94.743  704.52 143.617  696.56
  222.95  696.36 249.252  692.22 257.877  694.07  289.63  694.67 303.898  688.58
   319.3  687.85 323.279   689.9 327.138  688.24 389.854  688.29 453.046  684.92
 537.965  690.07 603.801  687.43 724.854   688.6 764.524  686.16   796.1  686.38
 812.908  689.97 829.194  690.57 842.289  696.71 862.964  703.39 881.027  707.08
 921.815  722.83 949.411  724.91 954.668  723.411001.477  723.991026.678     722
#Mann= 4 ,-1 , 0
       0     .04       0 143.617    .017       0  222.95     .04       0
 842.289     .04       0
#XS Ineff= 2 , 0
       0     7.5                       0
Permanent Ineff=
       T       F
Bank Sta=222.95,842.289
XS Rating Curve= 0 ,0
Skew Angle= 36.5
Exp/Cntr=0.3,0.1

Type RM Length L Ch R = 3 ,246.38  ,,,
BEGIN DESCRIPTION:
FRA-71-1503L I-71-SB
END DESCRIPTION:
Bridge Culvert--1,0,-1,-1, 0
Deck Dist Width WeirC Skew NumUp NumDn MinLoCord MaxHiCord MaxSubmerge Is_Ogee
1,109.5,2.6,36.5, 7, 7, , , 0.98, 0, 0,0,,
   8.033 116.043 276.814 448.985 623.473  813.821018.628
  786.41 784.353781.1778 782.801 782.738 782.801 782.829
  777.41 775.353772.1778 773.801 773.738 773.801 773.829
   8.045   166.6 327.372 500.092 678.103 877.1071014.403
  783.71 782.498 780.225 777.985 777.566779.2638781.5989
  774.71 773.498 771.225 768.985 768.566770.2639772.5989
Pier Skew, UpSta & Num, DnSta & Num=  ,116.043, 4 ,166.6, 4 , 0 , 0 , 0 ,,
     8.5     8.5       8       8
     650   697.2   697.2 775.353
     8.5     8.5       8       8
     650   697.2   697.2 773.498
Pier Skew, UpSta & Num, DnSta & Num=  ,276.814, 4 ,327.372, 4 , 0 , 0 , 0 ,,
     8.5     8.5       8       8
     650   697.2   697.2 772.178
     8.5     8.5       8       8
     650   697.2   697.2 771.225
Pier Skew, UpSta & Num, DnSta & Num=  ,448.985, 4 ,500.092, 4 , 0 , 0 , 0 ,,
     8.5     8.5       8       8
     650   697.2   697.2 773.801
     8.5     8.5       8       8
     650   697.2   697.2 768.985
Pier Skew, UpSta & Num, DnSta & Num=  ,623.473, 4 ,678.103, 4 , 0 , 0 , 0 ,,
     8.5     8.5       8       8
     650   697.2   697.2 773.738
     8.5     8.5       8       8
     650   697.2   697.2 768.566
Pier Skew, UpSta & Num, DnSta & Num=  ,813.82, 6 ,877.107, 6 , 0 , 0 , 0 ,,
      10      10      10      10       8       8
     680     693     693     698     698 773.801
      10      10      10      10       8       8
     680     693     693     698     698 770.264
BR Coef=-1 , 0 , 0 ,, 0 ,,,0.8,-1,,0,
WSPro=,,,, 1 ,,,, 0 ,,,, 0 ,,,,-1 ,-1 ,-1 , 0 , 0 , 0 , 0 , 0
BC Design=,, 0 ,, 0 ,,,,,,
BC Use User HTab Curves=0
BC User HTab FreeFlow(D)= 0

Type RM Length L Ch R = 1 ,246.37  ,25,79,66
XS GIS Cut Line= 6
      1825670.41       711880.14       1825573.3       711848.23
       1824747.1       711560.98      1824589.71       711502.83
       1824517.5       711472.18      1824473.41       711451.37
#Sta/Elev= 30
       0  748.46  25.699  749.43  41.961  752.32  47.717  749.15  62.741  751.88
  85.185  746.65  98.681  732.08 104.542  720.79 109.389  720.57  121.64  731.96
   133.4  719.15 155.152  717.61 217.339  706.36 267.564  704.17  351.02  706.68
 383.391  705.58 412.186  696.29 431.277  696.37 445.634  693.79 452.202  689.75
 525.626  691.77 563.648  688.75 663.286  690.82 827.948  687.47 858.977  690.96
 892.924  692.13 902.249  694.92 940.038  704.53 995.898  723.371022.458  725.29
#Mann= 4 ,-1 , 0
       0     .04       0  351.02    .017       0 412.186     .04       0
 902.249     .04       0
Bank Sta=412.186,902.249
XS Rating Curve= 0 ,0
Skew Angle= 36.5
Exp/Cntr=0.3,0.1

Type RM Length L Ch R = 1 ,246.35  ,76,89,68
XS GIS Cut Line= 6
      1825458.76       711781.91      1825331.26        711734.8
      1825027.19       711611.44      1824839.22       711536.51
      1824624.49       711454.18      1824449.47       711389.63
#Sta/Elev= 30
       0  717.86  24.534   714.8   36.42  714.68  53.519  712.01  86.895  709.07
 143.781  707.37 196.562  707.36 227.816   699.1 230.337  697.38 238.495  696.37
 256.947   696.4  265.45  694.93 268.126  690.41 333.808  690.49 369.106  688.33
 393.001  689.02 404.995   688.1 429.183  688.89 442.092  691.28 535.521  688.89
 687.698  689.21 718.498  691.97 737.465  697.54 746.891  701.51  767.22  706.95
 797.689  718.79 797.789  724.38 798.458  725.42 814.065  731.56 832.617  732.05
#Mann= 4 ,-1 , 0
       0     .04       0   36.42    .017       0 256.947     .04       0
 737.465     .04       0
#XS Ineff= 2 , 0
       0       0                       0
Permanent Ineff=
       T       F
Bank Sta=256.947,737.465
XS Rating Curve= 0 ,0
Skew Angle= 39.75
Exp/Cntr=0.3,0.1

Type RM Length L Ch R = 3 ,246.34  ,,,
BEGIN DESCRIPTION:
FRA-70-1323C Ramp D3
END DESCRIPTION:
Bridge Culvert--1,0,-1,-1, 0
Deck Dist Width WeirC Skew NumUp NumDn MinLoCord MaxHiCord MaxSubmerge Is_Ogee
1,86,2.6,39.75, 6, 6, , , 0.98, 0, 0,0,,
   6.995 165.108 333.036 511.631 688.573 832.614
  730.05  741.15  741.89   742.2  741.14 732.552
  721.55  733.15  733.89   734.2  733.14 724.052
   8.417 168.227 336.115 514.121 684.263  822.43
  729.98  741.15  741.89   742.2  741.14 734.306
  721.48  733.15  733.89   734.2  733.14 725.806
Pier Skew, UpSta & Num, DnSta & Num=  ,165.108, 4 ,168.227, 4 , 0 , 0 , 0 ,,
     8.5     8.5       8       8
     650   697.2   697.2  733.15
     8.5     8.5       8       8
     650   697.2   697.2  733.15
Pier Skew, UpSta & Num, DnSta & Num=  ,333.036, 4 ,336.115, 4 , 0 , 0 , 0 ,,
     8.5     8.5       8       8
     650   697.2   697.2  733.89
     8.5     8.5       8       8
     650   697.2   697.2  733.89
Pier Skew, UpSta & Num, DnSta & Num=  ,511.631, 4 ,514.121, 4 , 0 , 0 , 0 ,,
     8.5     8.5       8       8
     650   697.2   697.2   734.2
     8.5     8.5       8       8
     650   697.2   697.2   734.2
Pier Skew, UpSta & Num, DnSta & Num=  ,688.573, 4 ,684.263, 4 , 0 , 0 , 0 ,,
     8.5     8.5       8       8
     650   697.2   697.2  733.14
     8.5     8.5       8       8
     650   697.2   697.2  733.14
BR Coef=-1 , 0 , 0 ,, 0 ,,,0.8,-1,,0,
WSPro=,,,, 1 ,,,, 0 ,,,, 0 ,,,,-1 ,-1 ,-1 , 0 , 0 , 0 , 0 , 0
BC Design=,, 0 ,, 0 ,,,,,,
BC Use User HTab Curves=0
BC User HTab FreeFlow(D)= 0

Type RM Length L Ch R = 1 ,246.31  ,53,79.5,66
XS GIS Cut Line= 6
      1825427.66       711708.66      1825378.97       711690.29
      1825334.47       711673.05      1825289.29       711654.89
      1824490.33       711329.84      1824418.97       711299.53
#Sta/Elev= 30
       0  727.27  66.385  726.64  79.427  720.64  79.962  719.57  80.081  708.21
 150.762  707.73 170.448  702.72 200.575  699.89  230.91  693.53 251.428  689.34
 371.008   686.2  404.94  686.78 454.998  690.51  480.28  690.33 489.933  688.94
 496.986  689.89 577.996  689.84 666.705  687.58  694.12   689.6 723.058  698.44
 768.181  716.87 771.042  719.27 772.254   721.7 779.901  728.37 782.271  728.49
 785.534  726.55 789.004  727.56 800.538  727.25 806.223  728.69 808.943  727.99
#Mann= 4 ,-1 , 0
       0     .04       0  66.385    .017       0  230.91     .04       0
 723.058     .04       0
Bank Sta=230.91,723.058
XS Rating Curve= 0 ,0
Skew Angle= 42
Exp/Cntr=0.3,0.1

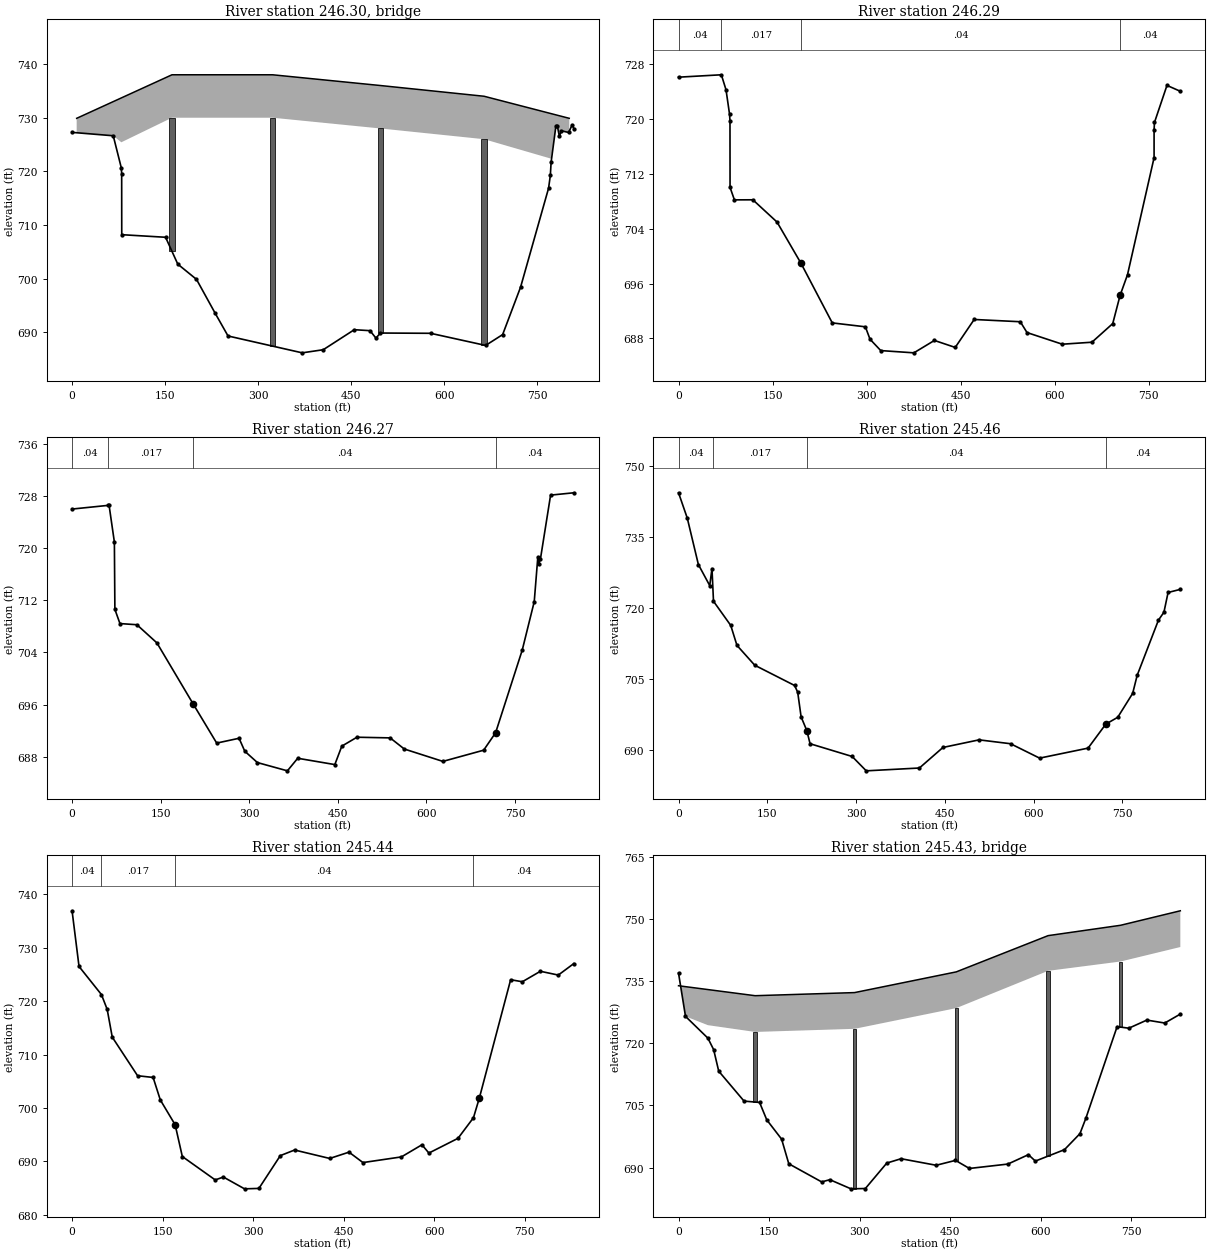
Type RM Length L Ch R = 3 ,246.30  ,,,
BEGIN DESCRIPTION:
FRA-70-1322L I-70-WB
END DESCRIPTION:
Bridge Culvert--1,0,-1,-1, 0
Deck Dist Width WeirC Skew NumUp NumDn MinLoCord MaxHiCord MaxSubmerge Is_Ogee
1,76.5,2.6,42, 6, 6, , , 0.98, 0, 0,0,,
   7.423 161.032 323.348 497.012 664.248 801.518
  729.89     738     738     736     734  729.89
  721.39     730     730     728     726  721.39
    7.44 163.496 325.811 499.475 660.804 792.804
  729.82     738     738     736     734  729.82
  721.32     730     730     728     726  721.32
Pier Skew, UpSta & Num, DnSta & Num=  ,161.032, 4 ,163.496, 4 , 0 , 0 , 0 ,,
     8.5     8.5       8       8
     650   697.2   697.2     730
     8.5     8.5       8       8
     650   697.2   697.2     730
Pier Skew, UpSta & Num, DnSta & Num=  ,323.348, 4 ,325.811, 4 , 0 , 0 , 0 ,,
     8.5     8.5       8       8
     650   697.2   697.2     730
     8.5     8.5       8       8
     650   697.2   697.2     730
Pier Skew, UpSta & Num, DnSta & Num=  ,497.012, 4 ,499.475, 4 , 0 , 0 , 0 ,,
     8.5     8.5       8       8
     650   697.2   697.2     728
     8.5     8.5       8       8
     650   697.2   697.2     728
Pier Skew, UpSta & Num, DnSta & Num=  ,664.248, 4 ,660.804, 4 , 0 , 0 , 0 ,,
     8.5     8.5       8       8
     650   697.2   697.2     726
     8.5     8.5       8       8
     650   697.2   697.2     726
BR Coef=-1 , 0 , 0 ,, 0 ,,,0.8,-1,,0,
WSPro=,,,, 1 ,,,, 0 ,,,, 0 ,,,,-1 ,-1 ,-1 , 0 , 0 , 0 , 0 , 0
BC Design=,, 0 ,, 0 ,,,,,,
BC Use User HTab Curves=0
BC User HTab FreeFlow(D)= 0

Type RM Length L Ch R = 1 ,246.29  ,6.5,42.5,56.5
XS GIS Cut Line= 6
      1825401.16       711642.22      1825312.85       711607.25
      1825197.97       711560.53      1824577.95       711308.34
      1824484.59       711269.97      1824404.37       711234.92
#Sta/Elev= 30
       0  726.12  68.288  726.47  75.726  724.28    81.3  720.75  82.043  719.78
  82.155  710.03  89.096  708.21 118.539  708.22 157.086  704.97 195.365  698.94
 245.163  690.25 297.964  689.68 305.351  687.87 322.495  686.21  375.31  685.88
 408.053  687.69  441.25  686.67 471.488  690.75 545.045  690.42 555.716  688.84
 611.957  687.14 659.273  687.43 692.455  690.15 704.145  694.26 716.013  697.29
 758.379  714.37 758.394  718.43 759.004  719.51 778.935  724.92 800.241  724.06
#Mann= 4 ,-1 , 0
       0     .04       0  68.288    .017       0 195.365     .04       0
 704.145     .04       0
Bank Sta=195.365,704.145
XS Rating Curve= 0 ,0
Skew Angle= 42
Exp/Cntr=0.3,0.1

Type RM Length L Ch R = 1 ,246.27  ,88.5,142.5,181
XS GIS Cut Line= 6
       1825385.5       711629.15      1825247.29       711574.58
      1825192.54       711551.32      1824984.67        711455.9
      1824558.31       711249.13      1824359.14       711147.47
#Sta/Elev= 30
       0  726.02  61.377  726.59  62.613  726.63  71.638  720.95  72.491  710.62
  81.067  708.44 109.789  708.26  143.68  705.47 204.997   696.1 244.856  690.09
 282.731  690.83 292.422  688.84  313.76   687.1 364.569  685.83  382.02  687.76
 444.842  686.79 456.668  689.62 482.268  690.99 538.507  690.89 562.466  689.18
 627.775  687.28 696.813     689 717.065  691.68 762.152  704.37 782.456   711.8
 788.538  718.66 790.096  717.65 792.927  718.34 810.145  728.16 849.541  728.52
#Mann= 4 ,-1 , 0
       0     .04       0  61.377    .017       0 204.997     .04       0
 717.065     .04       0
Bank Sta=204.997,717.065
XS Rating Curve= 0 ,0
Skew Angle= 41.5
Exp/Cntr=0.3,0.1

Type RM Length L Ch R = 1 ,245.46  ,37.5,93.5,6.5
XS GIS Cut Line= 6
      1825330.07       711512.21      1825008.91       711368.39
      1824651.57        711182.4      1824589.22       711147.61
      1824473.59       711072.51      1824342.96       710967.15
#Sta/Elev= 30
       0  744.42  14.777  739.05  33.546  729.22  52.719  724.77  56.509  728.37
  59.078  721.45  88.212  716.34   98.72  712.11  128.76  707.91 196.122  703.62
 201.334   702.2 207.109  696.98 216.755  694.07 222.245  691.29 293.366  688.59
 317.175  685.55 406.983  686.15 446.767   690.5 507.807  692.11  560.96  691.29
 610.092  688.24 691.983  690.36 721.881  695.43 742.118  696.89 767.328  701.95
 774.915  705.76 810.894  717.46 820.151  719.13 827.162  723.31 847.855  723.97
#Mann= 4 ,-1 , 0
       0     .04       0  59.078    .017       0 216.755     .04       0
 721.881     .04       0
Bank Sta=216.755,721.881
XS Rating Curve= 0 ,0
Skew Angle= 41.5
Exp/Cntr=0.3,0.1

Type RM Length L Ch R = 1 ,245.44  ,92.7,87.5,178.2
XS GIS Cut Line= 6
      1825257.45       711441.41       1824686.9       711126.91
      1824476.62       711015.64      1824341.26        710959.8
      1824278.08        710941.9      1824205.35       710928.08
#Sta/Elev= 30
       0  736.94  11.533  726.51  48.642  721.25  58.195  718.47  66.574  713.28
 108.541  706.05 134.273  705.73 146.187  701.52 170.759  696.87 182.667  690.92
 237.157  686.54 250.676  687.08 285.706  684.87 309.536  684.95 345.012  691.09
 368.636  692.14 426.852  690.56 458.799  691.74 481.893  689.79 545.632  690.85
 579.637  693.12 591.155  691.57 639.387  694.33 664.999  698.19 674.891  701.94
 726.588  724.03 745.962  723.65 775.845  725.61 805.515   724.9  831.31  727.06
#Mann= 4 ,-1 , 0
       0     .04       0  48.642    .017       0 170.759     .04       0
 664.999     .04       0
Bank Sta=170.759,674.891
XS Rating Curve= 0 ,0
Skew Angle= 45
Exp/Cntr=0.3,0.1

Type RM Length L Ch R = 3 ,245.43  ,,,
BEGIN DESCRIPTION:
FRA-70-1321A (RC5)
Assumed high water from record plans: 695.9
END DESCRIPTION:
Bridge Culvert--1,0,-1,-1, 0
Deck Dist Width WeirC Skew NumUp NumDn MinLoCord MaxHiCord MaxSubmerge Is_Ogee
1,84,2.6,45, 7, 7, , , 0.98, 0, 0,0,,
       0 126.865 291.613 460.107 612.254   732.3 831.314
 733.902   731.5  732.25  737.25     746   748.5     752
 725.402  722.75   723.5   728.5   737.5  739.75  743.25
       0 131.106 285.748 446.454 597.346 724.847 794.059
 731.593   731.5  733.25  739.25   748.5 753.137     755
 723.093  722.75   724.5   730.5  739.75 744.637  746.25
Pier Skew, UpSta & Num, DnSta & Num=  ,126.865, 4 ,131.106, 4 , 0 , 0 , 0 ,,
     5.5     5.5       5       5
   652.2   697.2   697.2     723
     5.5     5.5       5       5
   652.2   697.2   697.2  722.75
Pier Skew, UpSta & Num, DnSta & Num=  ,291.613, 4 ,285.748, 4 , 0 , 0 , 0 ,,
     5.5     5.5       5       5
   647.4   697.2   697.2   723.5
     5.5     5.5       5       5
   647.4   697.2   697.2   724.5
Pier Skew, UpSta & Num, DnSta & Num=  ,460.107, 4 ,446.454, 4 , 0 , 0 , 0 ,,
     5.5     5.5       5       5
   643.8   697.2   697.2   728.5
     5.5     5.5       5       5
   643.8   697.2   697.2   730.5
Pier Skew, UpSta & Num, DnSta & Num=  ,612.254, 4 ,597.346, 4 , 0 , 0 , 0 ,,
     5.5     5.5       5       5
   645.3   697.2   697.2   737.5
     5.5     5.5       5       5
   645.3   697.2   697.2  739.75
Pier Skew, UpSta & Num, DnSta & Num=  ,732.3, 4 ,724.847, 4 , 0 , 0 , 0 ,,
     5.5     5.5       5       5
     680   696.9   696.9  742.05
     5.5     5.5       5       5
     680   696.9   696.9 744.637
BR Coef=-1 , 0 , 0 ,, 0 ,,,0.8,-1,,0,
WSPro=,,,, 1 ,,,, 0 ,,,, 0 ,,,,-1 ,-1 ,-1 , 0 , 0 , 0 , 0 , 0
BC Design=,, 0 ,, 0 ,,,,,,
BC Use User HTab Curves=0
BC User HTab FreeFlow(D)= 0

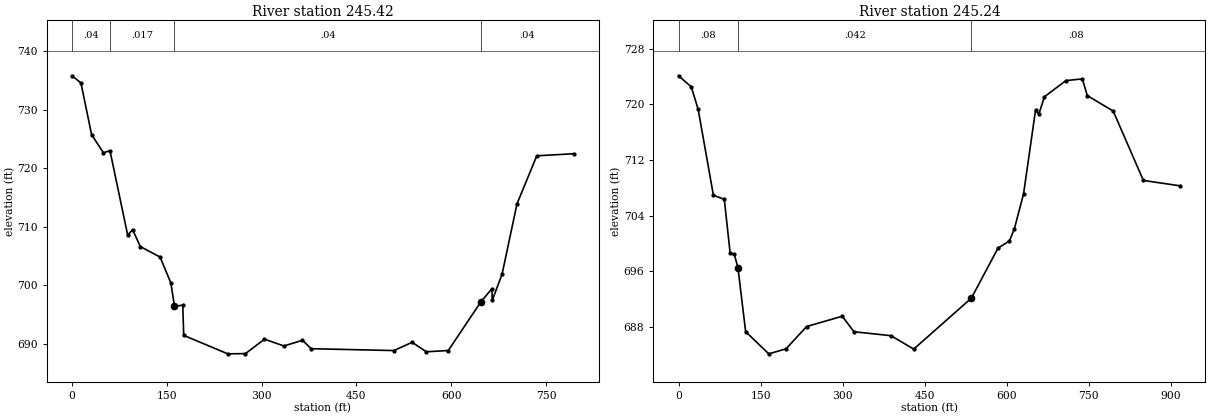
Type RM Length L Ch R = 1 ,245.42  ,755.6,402.5,22.2
XS GIS Cut Line= 6
      1825222.91       711355.31      1824672.33       711048.11
      1824492.65       710940.63       1824369.1       710857.66
      1824318.29       710813.84      1824273.83       710763.52
#Sta/Elev= 30
       0   735.8  14.029  734.58  30.893  725.73  49.717  722.62  59.956     723
  88.063  708.52  95.707  709.49 108.003  706.59 139.251   704.8  156.37  700.36
 162.019  696.38 175.157  696.56 176.692   691.4 246.391  688.24 274.421  688.28
 304.501  690.75 335.204  689.58 364.605  690.56  378.33  689.12 509.188   688.8
 538.094  690.21 560.665  688.59 595.391  688.81 646.515  697.07 664.362  699.38
 664.977   697.4  680.47  701.87 704.102   713.9 735.377  722.11 794.067  722.47
#Mann= 4 ,-1 , 0
       0     .04       0  59.956    .017       0 162.019     .04       0
 646.515     .04       0
Bank Sta=162.019,646.515
XS Rating Curve= 0 ,0
Skew Angle= 45
Exp/Cntr=0.3,0.1

Type RM Length L Ch R = 1 ,245.24  ,18.5,18.5,23
XS GIS Cut Line= 4
      1824954.51       710479.49      1824629.69       710510.07
       1824305.4       710540.59      1824045.85       710597.34
#Sta/Elev= 30
       0  724.13   23.31  722.54   35.95  719.28   63.74  706.94    83.7  706.35
   94.31  698.66     102  698.45  108.73  696.47  122.71  687.31  165.08  684.12
  196.54  684.84  234.25  688.05  299.47  689.53  320.78   687.3  388.68  686.73
  430.12   684.8  535.48  692.13  584.17  699.32  605.23  700.38  614.25  702.14
  631.03  707.16  652.93  719.21  658.81  718.58  669.09   721.1   708.4  723.44
  738.49  723.68  747.52  721.28  794.95  719.05  850.07  709.07  917.66  708.29
#Mann= 3 ,-1 , 0
       0     .08       0  108.73    .042       0  535.48     .08       0
#XS Ineff= 2 , 0
       0                   708.4       0
Permanent Ineff=
       F       T
Bank Sta=108.73,535.48
XS Rating Curve= 0 ,0
Exp/Cntr=0.3,0.1