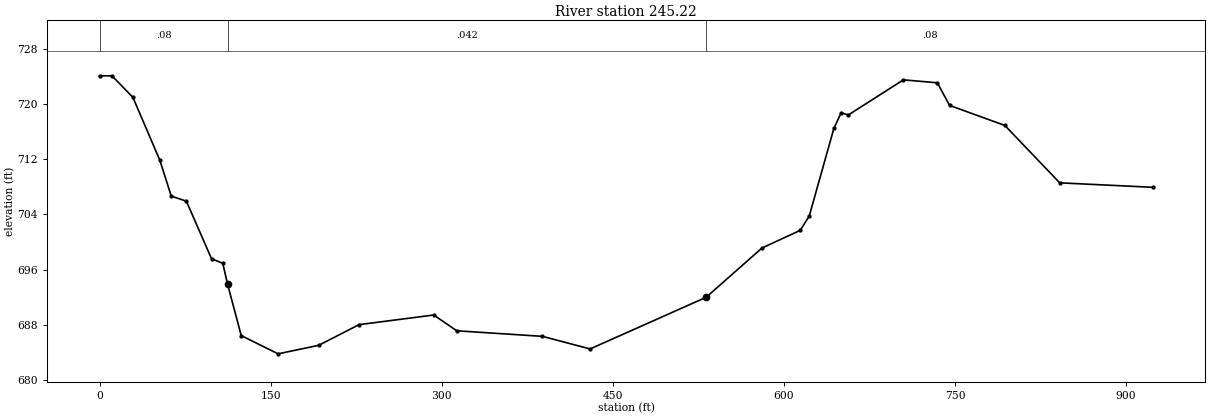
HEC-RAS study FRA-70-1321R.prj: FRA-70-1321R

--- FRA-70-1321R.g10 (geometry) --- (continued)

Type RM Length L Ch R = 1 ,245.22  ,785,973.5,1273
XS GIS Cut Line= 4
      1824950.77       710461.49      1824627.98       710491.87
      1824303.25       710522.44      1824034.03       710567.49
#Sta/Elev= 30
       0  724.14   10.85  724.13   29.15  721.01   52.74  711.89   62.81  706.66
   76.04  705.93   98.09  697.57  107.96   696.9  112.19  693.85  124.16   686.4
  156.47  683.75  192.13  684.99  227.41  687.99  292.96  689.39  313.07   687.1
  388.24  686.29  430.02  684.46  531.83  691.97  580.69  699.12   614.2  701.68
  622.15  703.76  643.75  716.49  650.14  718.77  656.46  718.45  704.77  723.55
  734.47  723.12  745.24  719.83  793.63  716.93  841.78  708.59  923.35  707.94
#Mann= 3 ,-1 , 0
       0     .08       0  112.19    .042       0  531.83     .08       0
#XS Ineff= 2 , 0
       0                  703.46       0
Permanent Ineff=
       F       T
Bank Sta=112.19,531.83
XS Rating Curve= 0 ,0
Exp/Cntr=0.3,0.1

--- FRA-70-1321R.g11 (geometry) ---

Geom Title=Prpsd_Cndtn_3_Prfrrd_with_dam
Program Version=4.10
BEGIN GEOM DESCRIPTION:
Vertical Datum = NAVD 88
Projection = State Plane Ohio South
END GEOM DESCRIPTION:

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
River Reach=SciotoRiver     ,SciotoRiver
Reach XY= 2
      1825011.68       711724.57      1824948.51         711631.

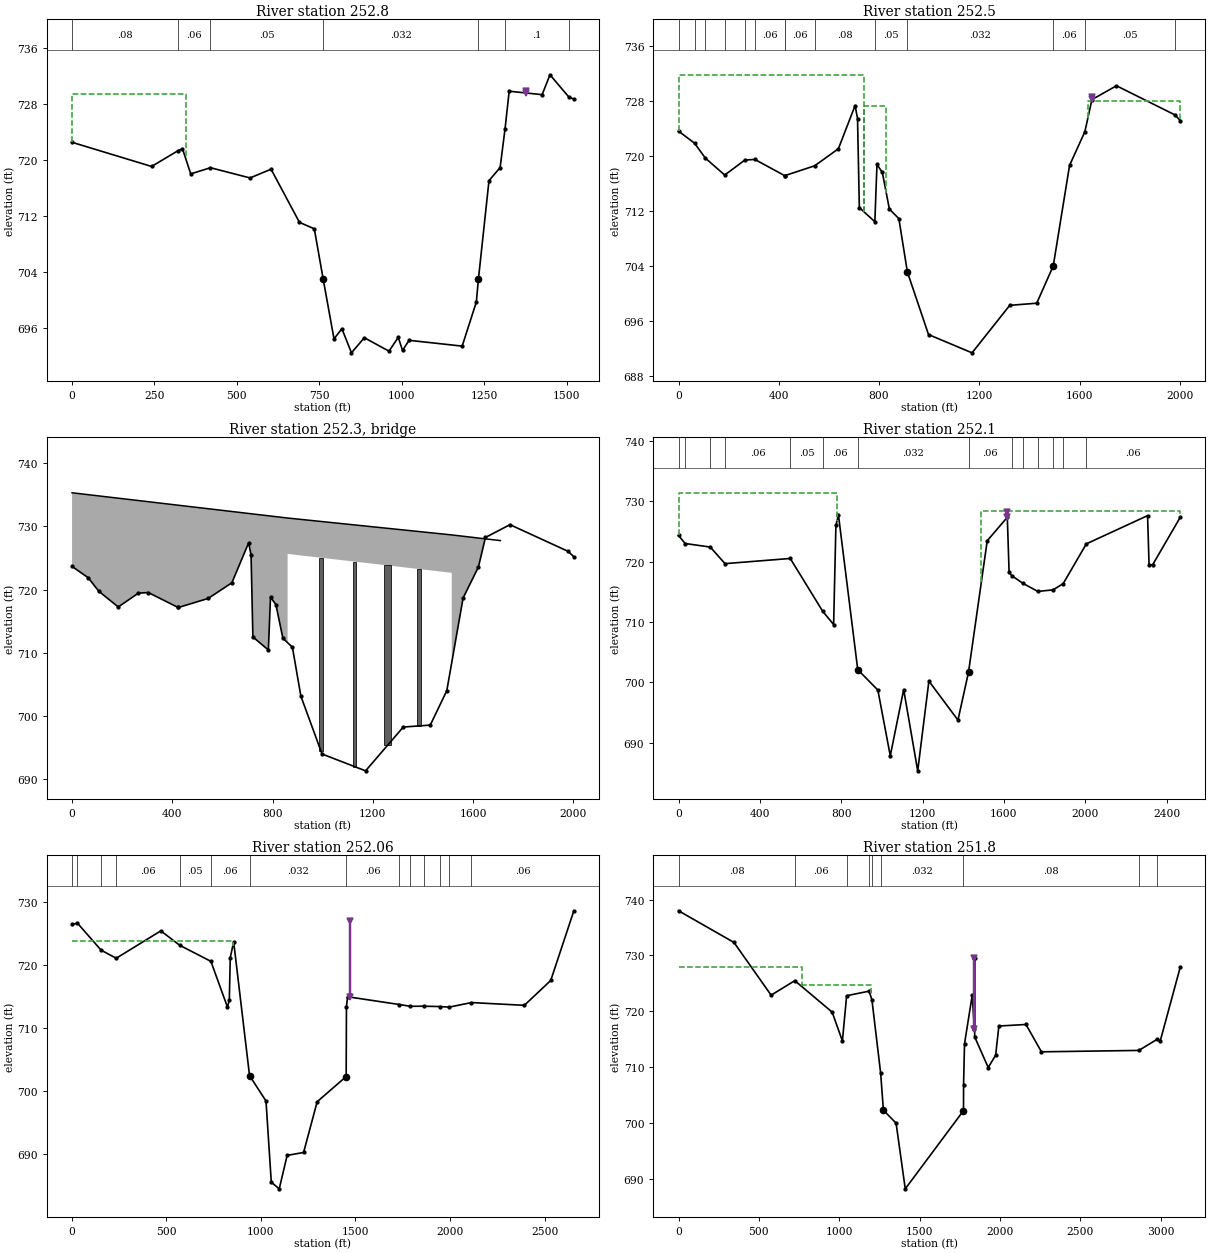
Type RM Length L Ch R = 1 ,252.8   ,816.3,590.47,312.21
BEGIN DESCRIPTION:
Overbank geometry from 2011 City of Columbus LiDAR data.  Channel geometry from 2011 hydrographic survey by Resource International.
END DESCRIPTION:
XS GIS Cut Line= 3
1825059.28161752716827.0005937671825102.24511428715305.381917849
 1825102.2453968715305.371912071
#Sta/Elev= 30
       0  722.55  241.21   719.1  319.94  721.31  334.94  721.64  359.94  718.04
  419.93  718.92   539.9  717.46  603.64  718.71  689.87  711.11  734.87  710.19
  761.84  702.99  794.59  694.47  818.58  695.91  847.56  692.47  886.54  694.63
   961.5  692.71  989.49  694.68 1002.48  692.82 1022.47  694.26 1183.39  693.43
 1226.37  699.73 1232.69  702.99 1264.77  717.07 1298.52  718.94 1313.51  724.49
 1326.01  729.85    1426  729.36 1449.74   732.2 1507.23  729.01 1522.23  728.73
#Mann= 7 ,-1 , 0
       0     .08       0  319.94     .06       0  419.93     .05       0
  761.84    .032       0 1232.69     .04       0 1313.51      .1       0
 1507.23     .05       0
Levee=0,,,-1,1377,729.9,,
#XS Ineff= 2 , 0
       0   344.3   729.5               0
Permanent Ineff=
       F       F
Bank Sta=761.84,1232.69
XS Rating Curve= 0 ,0
Exp/Cntr=0.5,0.3

Type RM Length L Ch R = 1 ,252.5   ,194.58,195.03,226.52
BEGIN DESCRIPTION:
Overbank geometry from 2011 City of Columbus LiDAR data.  Channel geometry from 2011 hydrographic survey by Resource International.
END DESCRIPTION:
Node Name=AK
XS GIS Cut Line= 3
   1826550.36066   716753.121805   1825271.62404   715427.642828
   1825112.98591   715273.159541
#Sta/Elev= 30
       0  723.64  64.253  721.87 106.693  719.72 184.279  717.24 264.299  719.42
 304.304  719.52 423.116  717.16  424.33  717.16 543.142  718.59 637.707  721.07
 704.396  727.37  714.09  725.47 721.366   712.5 783.194  710.44 791.664  718.78
 813.002  717.63  841.14  712.29 878.981  710.89 912.932  703.13 997.338     694
1170.992  691.341321.359  698.261429.042  698.571495.012  704.011560.013  718.65
1621.132  723.561649.261  728.231747.066  730.25 1980.19  726.012001.924  725.17
#Mann= 14 ,-1 , 0
       0     .08       0  64.253     .06       0 106.693     .08       0
 184.279     .06       0 264.299     .05       0 304.304     .06       0
 423.116     .05       0  424.33     .06       0 543.142     .08       0
 783.194     .05       0 912.932    .032       01495.012     .06       0
1621.132     .05       0 1980.19     .06       0
Levee=0,,,-1,1650.25,728.6,,
#XS Ineff= 3 ,-1
       0  741.41  731.85  741.41 828.637  727.371633.2652132.122  728.08
Permanent Ineff=
       F       F       F
Bank Sta=912.932,1495.012
XS Rating Curve= 0 ,0
Skew Angle= 14
Exp/Cntr=0.5,0.3

Type RM Length L Ch R = 3 ,252.3   ,,,
BEGIN DESCRIPTION:
Norfolk Southern Railroad Bridge
Geometry from plans provided by Norfolk Southern.  Top chord elevations adjusted using 2011 City of Columbus LiDAR data.
END DESCRIPTION:
Bridge Culvert--1,0,-1,-1, 0
Deck Dist Width WeirC Skew NumUp NumDn MinLoCord MaxHiCord MaxSubmerge Is_Ogee
118,29.5,2.6,14, 6, 8, , , 0.98, 0, 0,0,,
       0 859.866 859.8661514.8161514.8161708.876
  735.29   731.3   731.3  728.63  728.63  727.73
             680  725.63  722.64     680
-196.762  57.429 810.789 810.7891457.6341457.6342084.1262321.029
  736.03  734.84   731.3   731.3  728.63  728.63  725.69  724.58
                     680  725.63  722.64     680
Pier Skew= 14
Pier Skew, UpSta & Num, DnSta & Num=  ,993.282, 2 ,953.644, 2 , 0 , 0 , 0 ,,
    14.9   11.98
     690   725.2
    14.9   11.98
     690   725.2
Pier Skew, UpSta & Num, DnSta & Num=  ,1126.696, 2 ,1087.057, 2 , 0 , 0 , 0 ,,
    14.9   11.98
     690  724.55
    14.9   11.98
     690  724.55
Pier Skew, UpSta & Num, DnSta & Num=  ,1260.113, 5 ,1220.474, 5 , 0 , 0 , 0 ,,
   28.48   28.48   16.84   16.12   12.96
     690  704.84  706.67  721.32  724.02
   28.48   28.48   16.84   16.12   12.96
     690  704.84  706.67  721.32  724.02
Pier Skew, UpSta & Num, DnSta & Num=  ,1383.825, 2 ,1344.185, 2 , 0 , 0 , 0 ,,
    14.9   11.98
     690  723.26
    14.9   11.98
     690  723.26
BR Coef=-1 , 1 , 1 ,1.25, 0 ,,,0.8,-1,2,1,
WSPro=,,,, 1 ,,,, 0 ,,,, 0 ,,,,-1 ,-1 ,-1 , 0 , 0 , 0 , 0 , 0
BC Design=,, 0 ,, 0 ,,,,,,
BC Use User HTab Curves=0
BC User HTab FreeFlow(D)= 0

Type RM Length L Ch R = 1 ,252.1   ,224.67,252.61,290.84
BEGIN DESCRIPTION:
Overbank geometry from 2011 City of Columbus LiDAR data.  Channel geometry from 2011 hydrographic survey by Resource International.
END DESCRIPTION:
XS GIS Cut Line= 6
   1826762.92421   716582.237304   1826292.09083   716142.654193
   1826143.30143   716056.178645   1825606.04922   715544.772187
   1824970.63252   714894.0428461824903.85249717714825.653519359
#Sta/Elev= 30
       0  724.35   32.46  723.02  156.04  722.43  228.45  719.68  549.27  720.54
  708.99  711.78  762.61  709.59  773.83  726.03  786.39  727.73  881.24  702.11
  980.17  698.72 1041.15  687.83 1107.13   698.81176.109  685.33 1231.09  700.21
 1374.05  693.74 1426.03  701.71 1518.03  723.49 1616.71  727.36 1625.45  718.29
 1637.95   717.7 1694.17   716.4 1766.63  715.08 1841.59  715.33 1891.57  716.37
 2005.26  722.96 2306.33  727.642313.821  719.49 2331.31  719.49 2467.48  727.39
#Mann= 14 ,-1 , 0
       0     .08       0   32.46     .06       0  156.04     .05       0
  228.45     .06       0  549.27     .05       0  708.99     .06       0
  881.24    .032       0 1426.03     .06       0 1637.95     .08       0
 1694.17     .06       0 1766.63     .08       0 1841.59     .06       0
 1891.57     .08       0 2005.26     .06       0
Levee=0,,,-1,1616.71,728.3,,
#XS Ineff= 2 , 0
       0  779.29  731.43 1489.13       0  728.47
Permanent Ineff=
       F       F
Bank Sta=881.24,1426.03
XS Rating Curve= 0 ,0
Exp/Cntr=0.5,0.3

Type RM Length L Ch R = 1 ,252.06  ,371.37,352.86,335.57
BEGIN DESCRIPTION:
Overbank geometry from 2011 City of Columbus LiDAR data.  Channel geometry from 2011 hydrographic survey by Resource International.
END DESCRIPTION:
XS GIS Cut Line= 5
   1826944.72995   716557.711762   1826205.14645   715813.961937
   1825680.14652   715222.295142   1825513.47986   715024.378543
    1825000.9799   714807.711981
#Sta/Elev= 30
    1.25  726.39   29.97  726.59  154.83  722.32  234.75  721.04  470.75  725.38
  570.64  723.09  735.46  720.55  822.87  713.32  832.86  714.37  837.85  721.13
   855.9  723.64  939.89  702.44 1026.88  698.43 1054.87  685.56 1096.82  684.51
 1138.77  689.81 1225.66  690.27 1297.57  698.31 1450.88   702.3 1452.38  713.36
 1458.37  714.94 1732.42  713.71  1789.9  713.43 1862.39  713.44 1944.88  713.39
 1996.13   713.3 2113.61  714.02 2393.07  713.58  2532.8  717.52 2655.07  728.56
#Mann= 14 ,-1 , 0
    1.25     .08       0   29.97     .06       0  154.83     .05       0
  234.75     .06       0  570.64     .05       0  735.46     .06       0
  939.89    .032       0 1450.88     .06       0 1732.42     .08       0
  1789.9     .06       0 1862.39     .08       0 1944.88     .06       0
 1996.13     .08       0 2113.61     .06       0
Levee=0,,,-1,1472.36,727,,
#XS Ineff= 2 , 0
       0   850.9  723.79               0
Permanent Ineff=
       F       F
Bank Sta=939.89,1450.88
XS Rating Curve= 0 ,0
Exp/Cntr=0.3,0.1

Type RM Length L Ch R = 1 ,251.8   ,433.64,366.02,306.26
BEGIN DESCRIPTION:
Overbank geometry from 2011 City of Columbus LiDAR data.  Channel geometry from 2011 hydrographic survey by Resource International.
END DESCRIPTION:
XS GIS Cut Line= 4
1827472.38998027716511.9359351841825733.71924503714878.126866847
1825008.25645711714749.1487783491825008.19732577714749.138265546
#Sta/Elev= 30
       0  738.01  344.94  732.34  576.16  722.89  723.63  725.49  956.09  719.85
 1019.83  714.68 1046.08  722.79 1186.06  723.61 1203.55  722.04 1257.91  708.89
 1274.91  702.28 1353.91  699.96  1410.9  688.19 1773.38   702.2 1773.88  706.88
 1779.71  714.18 1827.47  722.84    1841  716.85    1841  729.55    1843  729.55
    1843  715.41 1927.19  709.93 1973.43  712.13 1993.43  717.36 2162.15  717.64
 2258.38  712.74  2864.2  712.99  2976.6  714.95 2997.83   714.7 3122.73  727.96
#Mann= 9 ,-1 , 0
       0     .08       0  723.63     .06       0 1046.08     .08       0
 1186.06     .05       0 1203.55     .06       0 1257.91    .032       0
 1773.38     .08       0  2864.2     .06       0  2976.6     .08       0
Levee=0,,,-1,1841,729.55,,
#XS Ineff= 2 ,-1
       0  765.67   727.9  765.67 1195.56  724.69
Permanent Ineff=
       F       F
Bank Sta=1274.91,1773.38
XS Rating Curve= 0 ,0
Exp/Cntr=0.3,0.1

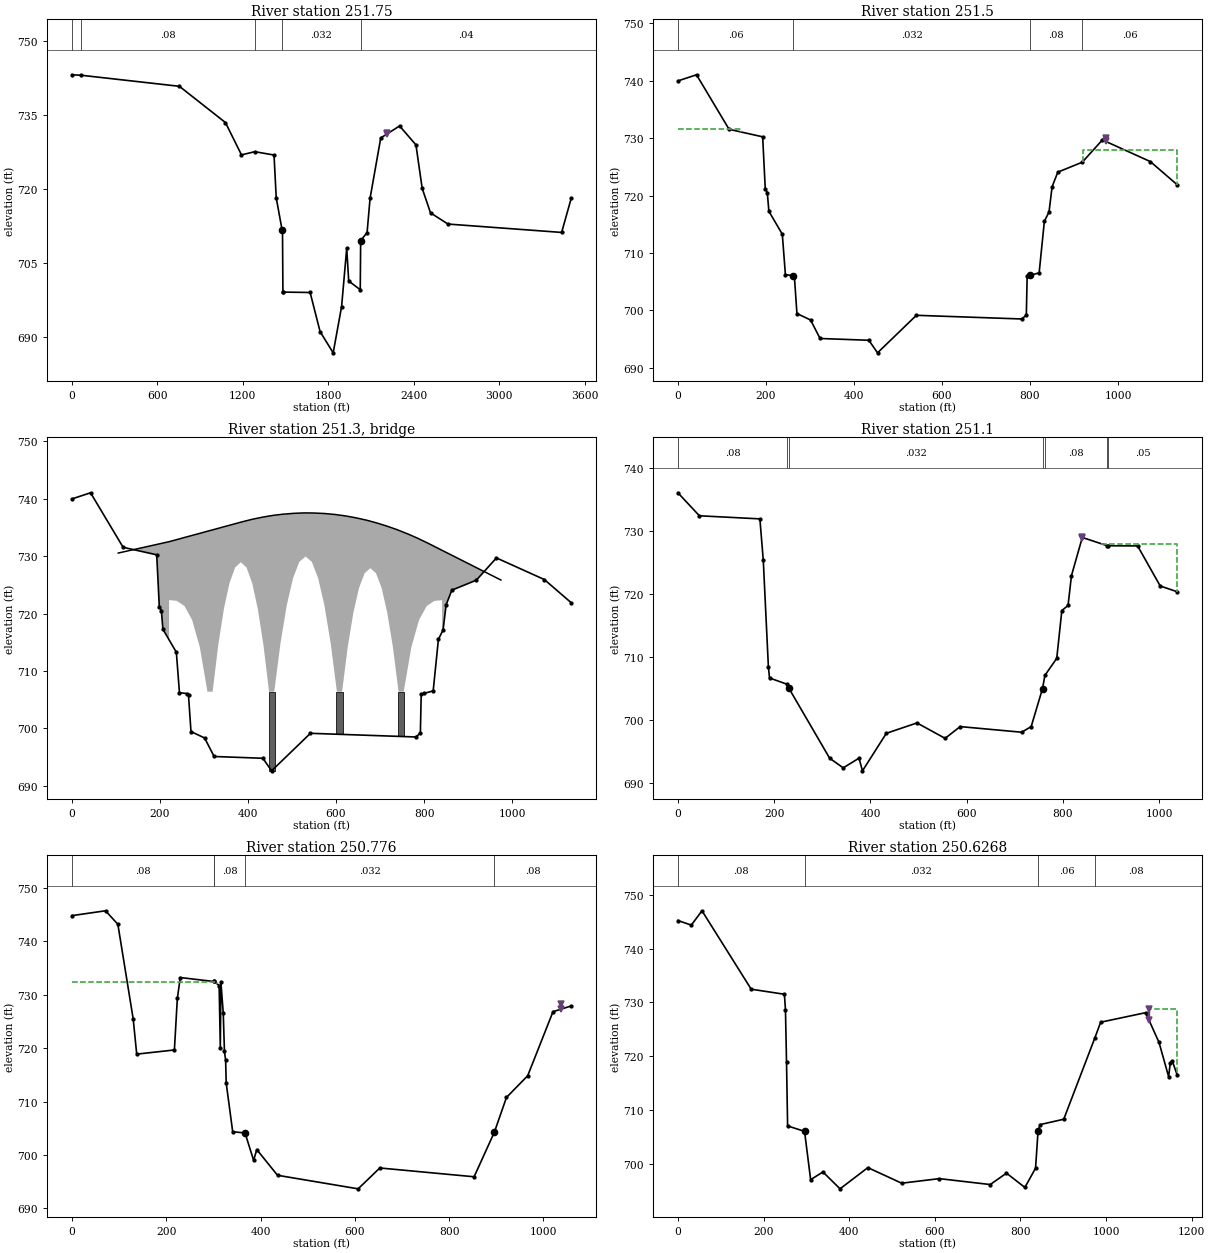
Type RM Length L Ch R = 1 ,251.75  ,405.37,275.3,167.66
BEGIN DESCRIPTION:
Overbank geometry from 2011 City of Columbus LiDAR data.  Channel geometry from 2011 hydrographic survey by Resource International.
END DESCRIPTION:
XS GIS Cut Line= 5
1828117.20168278716194.0865052641827214.42396078715564.746228516
1826348.89649236 715055.628480361825800.97993727714822.295285597
 1825011.3965427714661.878611684
#Sta/Elev= 30
       0  743.23    66.2  743.13  754.48  740.89    1078  733.53 1190.42  726.97
 1284.09  727.62 1418.98  726.94 1434.43  718.26 1475.42  711.75 1478.42  711.66
 1481.42  699.22 1482.42  699.12 1672.41  699.04 1742.41   691.1  1834.4  686.79
  1893.4  696.18  1929.4  707.99 1943.39  701.37 2024.39   699.6 2027.39  709.58
 2072.39  711.19 2093.42  718.17 2168.34  730.41 2300.69  732.84 2415.56     729
 2459.26  720.18 2517.94   715.2  2640.3  712.93 3438.48  711.23 3505.94  718.18
#Mann= 5 ,-1 , 0
       0     .06       0    66.2     .08       0 1284.09     .05       0
 1475.42    .032       0 2027.39     .04       0
Levee=0,,,-1,2210,731.4,,
Bank Sta=1475.42,2027.39
XS Rating Curve= 0 ,0
Exp/Cntr=0.5,0.3

Type RM Length L Ch R = 1 ,251.5   ,243.88,274.25,267.45
BEGIN DESCRIPTION:
Overbank geometry from 2011 City of Columbus LiDAR data.  Channel geometry from 2011 hydrographic survey by Resource International.
END DESCRIPTION:
Node Name=AJ
XS GIS Cut Line= 2
1827350.66056494 715094.145463691826160.55402127714892.372245193
#Sta/Elev= 30
       0  739.99  42.267  741.06 116.249  731.56 192.571  730.25 198.444  721.23
 203.143  720.51 206.667  717.28 237.188  713.28 244.236  706.23 261.525  706.07
 264.796  705.75 270.425  699.46 301.416  698.33  323.01  695.11 433.809   694.8
 453.533  692.61 541.799  699.15 781.232  698.51 791.559  699.19 793.439  705.95
 800.017706.1002 820.671  706.55 832.521  715.52 843.092  717.16  850.14  721.55
 863.051  724.09 918.737 725.833 964.331  729.711073.242  725.941134.294   721.9
#Mann= 4 ,-1 , 0
       0     .06       0 261.525    .032       0 800.017     .08       0
 918.737     .06       0
Levee=0,,,-1,972.22,730.08,,
#XS Ineff= 2 , 0
       0 142.242  731.57 919.311       0     728
Permanent Ineff=
       F       F
Bank Sta=261.525,800.017
XS Rating Curve= 0 ,0
Skew Angle= 20
Exp/Cntr=0.5,0.3

Type RM Length L Ch R = 3 ,251.3   ,,,
BEGIN DESCRIPTION:
Broad Street Bridge
Geometry from plans provided by the Franklin County Engineer's Office.
END DESCRIPTION:
Bridge Culvert--1,0,-1,-1, 0
Deck Dist Width WeirC Skew NumUp NumDn MinLoCord MaxHiCord MaxSubmerge Is_Ogee
70,98,2.6,20, 80, 79, , , 0.98, 0, 0,0,,
 105.226 199.196 220.677 220.677 222.688 238.109 246.181  255.54 269.673 272.971
 290.403 293.165 307.834 316.657  319.58 332.406  340.15 345.233  358.06 363.643
 370.887 383.714 387.135 396.541 409.367 410.627 422.194 434.119 435.021 447.848
 457.612 459.594  473.83 481.104 488.067 502.303 504.596  516.54 528.088 530.776
 545.013 551.581 559.248 573.485 575.074 587.721 598.565 601.958 613.703 622.058
  626.53 639.357  645.55 652.184 665.011 669.043 677.838 690.664 692.534 703.491
 716.027 716.318 729.145 739.519 741.972 753.718 763.012  771.15 786.503 788.581
 806.012 809.996 823.444 833.489 840.875 840.875 853.354 856.981 880.474 974.443
  730.56  732.17  732.54  732.54  732.58   732.9  733.07  733.27  733.56  733.63
  733.99  734.05  734.36  734.54   734.6  734.87  735.03  735.14   735.4  735.52
  735.67  735.94  736.01  736.19  736.44  736.46  736.64  736.83  736.84  737.01
  737.13  737.15  737.28  737.34  737.38  737.47  737.48  737.52  737.55  737.55
  737.54  737.53   737.5  737.45  737.44  737.35  737.27  737.23  737.11  737.02
  736.96  736.78  736.69  736.58  736.36  736.29  736.11  735.84   735.8  735.54
  735.24  735.23  734.89  734.61  734.53  734.17  733.89  733.62   733.1  733.02
  732.38  732.23  731.71  731.32  731.03  731.03  730.55  730.41   729.5  725.86
                     690  722.36  722.35  722.23  721.82  721.34  719.37  718.91
  714.19  712.96   706.4   706.4   706.4  714.53  718.34  720.84  725.35  726.53
  728.06  728.96  728.72  728.06  725.35  724.91  720.84  714.97  714.53   706.4
   706.4   706.4  714.87  718.24  721.47  726.19  726.65  729.02  729.78  729.96
  729.02  727.71  726.19  721.47  720.73  714.87  708.42   706.4   706.4  711.46
  714.17  720.17  722.25  724.48  727.06  727.33  727.92  727.06  726.68  724.48
  720.27  720.17  714.17  707.89   706.4   706.4  710.55  714.18  718.34   718.9
  721.33  721.53  722.22  722.29  722.35     690
 168.571 183.682 183.682 185.693 201.113 209.184 218.545 232.677 235.976 253.407
  256.17 270.839 279.662 282.584 295.411 303.155 308.238 321.065 326.646 333.891
 346.718 350.139 359.545 372.372 373.631 385.199 397.124 398.026 410.853 420.615
 422.599 436.835 444.108 451.072 465.308 467.601 479.544 491.093  493.78 508.017
 514.585 522.253  536.49 538.077 550.726  561.57 564.961 576.708 585.062 589.535
 602.362 608.554 615.188 628.015 632.046 640.842 653.669 655.539 666.496 679.032
 679.323  692.15 702.523 704.976 716.723 726.016 734.154 749.508 751.584 769.016
 773.001 786.447 796.493 803.878 803.878 816.358 819.985 843.477 937.447
  732.28  732.54  732.54  732.58   732.9  733.07  733.27  733.56  733.63  733.99
  734.05  734.36  734.54   734.6  734.87  735.03  735.14   735.4  735.52  735.67
  735.94  736.01  736.19  736.44  736.46  736.64  736.83  736.84  737.01  737.13
  737.15  737.28  737.34  737.38  737.47  737.48  737.52  737.55  737.55  737.54
  737.53   737.5  737.45  737.44  737.35  737.27  737.23  737.11  737.02  736.96
  736.78  736.69  736.58  736.36  736.29  736.11  735.84   735.8  735.54  735.24
  735.23  734.89  734.61  734.53  734.17  733.89  733.62   733.1  733.02  732.38
  732.23  731.71  731.32  731.03  731.03  730.55  730.41   729.5  725.86
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Pier Skew, UpSta & Num, DnSta & Num=  ,313.707, 4 ,276.711, 4 , 3 , 3 , 0 ,,
       7       7      14      14
     690   699.4   699.4   706.4
       7       7      14      14
     690   699.4   699.4   706.4
Pier Skew, UpSta & Num, DnSta & Num=  ,453.722, 4 ,416.725, 4 , 3 , 3 , 0 ,,
       7       7      14      14
     690   699.4   699.4   706.4
       7       7      14      14
     690   699.4   699.4   706.4
Pier Skew, UpSta & Num, DnSta & Num=  ,607.831, 4 ,570.835, 4 , 3 , 3 , 0 ,,
       7       7      14      14
     690   699.4   699.4   706.4
       7       7      14      14
     690   699.4   699.4   706.4
Pier Skew, UpSta & Num, DnSta & Num=  ,747.845, 4 ,710.849, 4 , 3 , 3 , 0 ,,
       7       7      14      14
     690   699.4   699.4   706.4
       7       7      14      14
     690   699.4   699.4   706.4
BR Coef=-1 , 1 , 1 ,0.9, 0 ,,,0.8,-1,1.33,1,
WSPro=,,,, 1 ,,,, 0 ,,,, 0 ,,,,-1 ,-1 ,-1 , 0 , 0 , 0 , 0 , 0
BC Design=,, 0 ,, 0 ,,,,,,
BC Use User HTab Curves=0
BC User HTab FreeFlow(D)= 0

Type RM Length L Ch R = 1 ,251.1   ,179.49,235.17,283.09
BEGIN DESCRIPTION:
Overbank geometry from 2011 City of Columbus LiDAR data.  Channel geometry from 2011 hydrographic survey by Resource International.
END DESCRIPTION:
XS GIS Cut Line= 3
1827493.87156461 714879.32863611 1826405.4665892714696.734513104
1826405.45671739714696.732856979
#Sta/Elev= 30
       0     736  44.626  732.36   170.3  731.87 177.348  725.32  187.92   708.5
 190.269   706.7 226.889705.6979 230.224  705.11 315.164     694  343.41  692.47
 376.131     694 383.385     692 432.954  697.94 496.543  699.58 555.077  697.14
 586.303     699 714.101  698.11 733.796     699 757.327  705.02 762.297707.1105
 786.899   709.8  797.47  717.37 810.382  718.17 817.429  722.88 839.972  728.93
 891.571727.6287 892.699727.6191  954.85  727.591001.825  721.251037.064  720.34
#Mann= 7 ,-1 , 0
       0     .08       0 226.889    .035       0 230.224    .032       0
 757.327    .035       0 762.297     .08       0 891.571     .06       0
 892.699     .05       0
Levee=0,,,-1,839.74,729.04,,
#XS Ineff= 2 , 0
       0  107.95  731.34  879.61       0  727.86
Permanent Ineff=
       F       F
Bank Sta=230.224,757.327
XS Rating Curve= 0 ,0
Skew Angle= 20
Exp/Cntr=0.5,0.3

Type RM Length L Ch R = 1 ,250.776 ,322.81,287.31,216.99
BEGIN DESCRIPTION:
Overbank geometry from 2011 City of Columbus LiDAR data.  Channel geometry from 2011 hydrographic survey by Resource International.
END DESCRIPTION:
XS GIS Cut Line= 2
1827694.99091302714805.1440731881826694.41936781714458.718250939
#Sta/Elev= 30
       0  744.84   71.17  745.75   97.39  743.22  129.86   725.5  137.35  718.89
  217.27  719.67  223.51  729.32  229.75  733.24  300.92   732.5  302.17   732.5
  312.16  731.73  314.66     720  315.91  732.32   320.9  726.57   323.4  719.41
   325.9  717.77  327.15  713.47  340.88  704.35   367.1  704.12  385.23     699
  392.05     701  435.94  696.19  606.92  693.65  652.91  697.56  852.88  695.91
   895.8  704.26   921.5  710.78  966.45  714.83 1020.14  726.84 1058.85  727.92
#Mann= 5 ,-1 , 0
       0     .08       0  300.92    .035       0  302.17     .08       0
   367.1    .032       0   895.8     .08       0
Levee=0,,,-1,1036.68,728.31,,
#XS Ineff= 2 , 0
          307.43  732.45
Permanent Ineff=
       F       F
Bank Sta=367.1,895.8
XS Rating Curve= 0 ,0
Exp/Cntr=0.3,0.1

Type RM Length L Ch R = 1 ,250.6268,445.39,376.26,241.66
BEGIN DESCRIPTION:
Overbank geometry from 2011 City of Columbus LiDAR data.  Channel geometry from 2011 hydrographic survey by Resource International.
END DESCRIPTION:
XS GIS Cut Line= 2
1827758.81230769 714410.312185691826602.38220586 714259.94043918
#Sta/Elev= 30
       0  745.24   31.25  744.38   56.25  747.05  171.24  732.45  248.73  731.51
  251.23  728.63  253.73  718.81  256.23     707  295.82  705.99  310.02     697
  338.76  698.43  378.73  695.29  443.68  699.24  522.63  696.34  610.56  697.19
  729.48  696.09  767.45  698.21  810.42  695.55  835.37  699.14  841.19  706.08
  846.19  707.25  901.18  708.25  973.68  723.35  987.43  726.31 1092.42  728.08
 1123.67  722.56 1146.16  716.17 1149.91  718.69 1154.91  719.05 1166.16  716.49
#Mann= 4 ,-1 , 0
       0     .08       0  295.82    .032       0  841.19     .06       0
  973.68     .08       0
Levee=0,,,-1,1099.68,728.71,,
#XS Ineff= 2 , 0
       0                 1099.68       0  728.71
Permanent Ineff=
       F       F
Bank Sta=295.82,841.19
XS Rating Curve= 0 ,0
Exp/Cntr=0.3,0.1

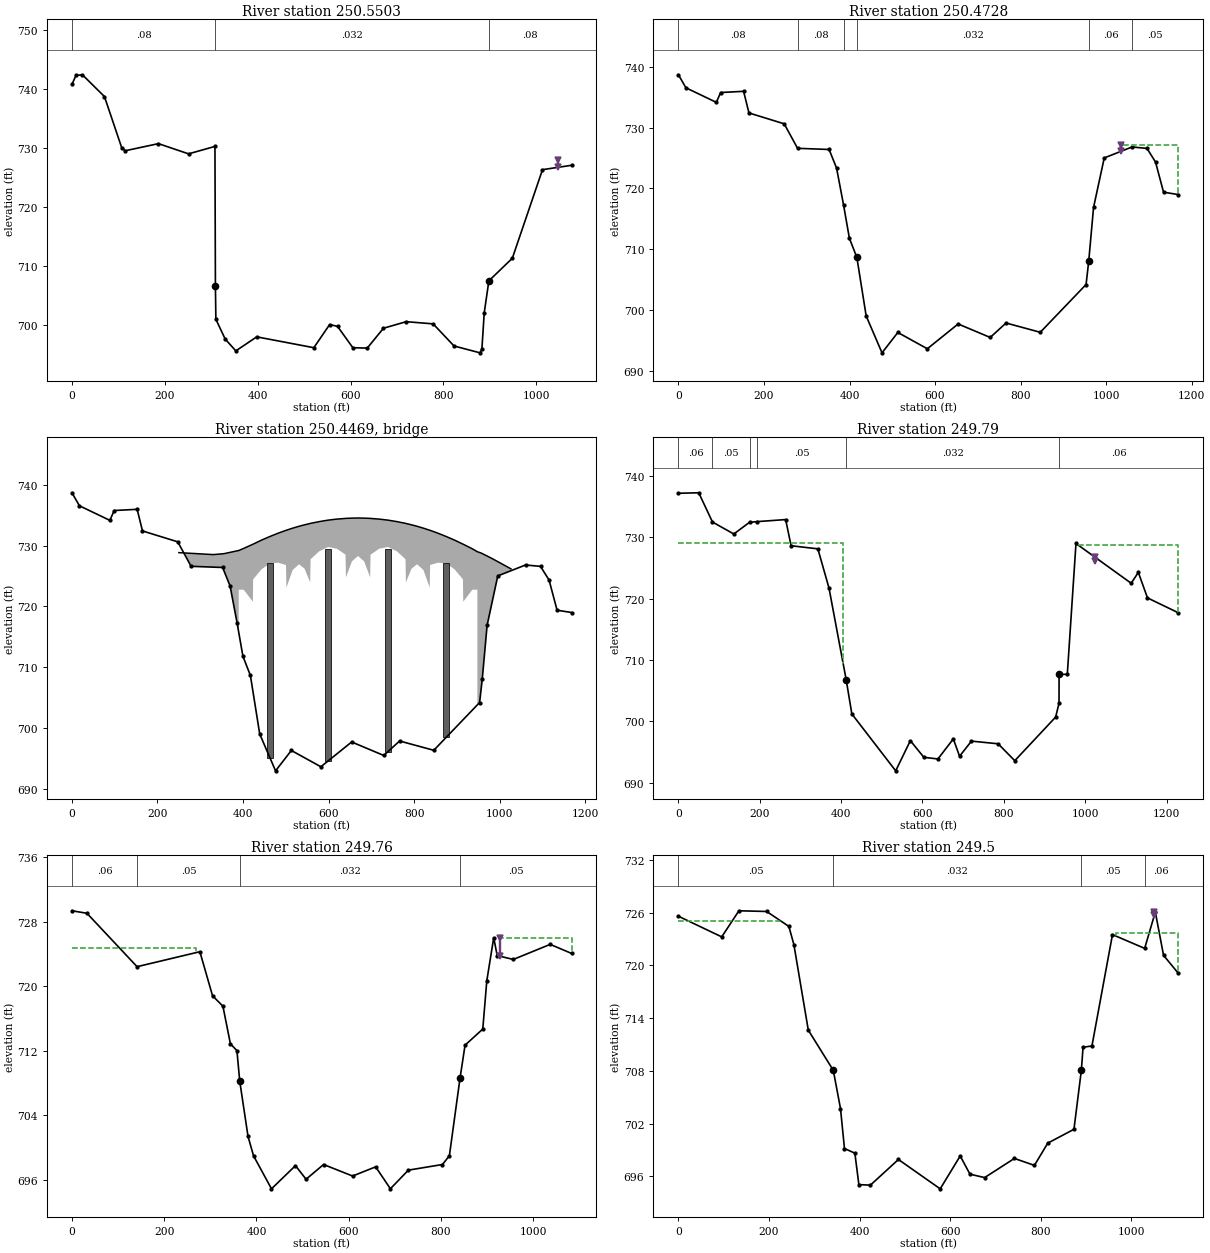
Type RM Length L Ch R = 1 ,250.5503,536.12,499.14,418.07
BEGIN DESCRIPTION:
Overbank geometry from 2011 City of Columbus LiDAR data.  Channel geometry from 2011 hydrographic survey by Resource International.
END DESCRIPTION:
Node Name=AI
XS GIS Cut Line= 2
   1827789.82406   713815.278271   1826752.47114   714099.776389
#Sta/Elev= 30
       0  740.77    8.75   742.3   22.49   742.4   69.96  738.71  107.44  729.97
  114.94  729.53  186.15  730.73  251.11     729   307.9  730.26   308.9  706.63
   309.9  700.97  329.89  697.62  352.89  695.61  397.87  697.99  520.83  696.15
  554.82  700.07  571.82  699.77  604.81  696.15   635.8  696.08  670.78  699.45
  719.77  700.56  777.75  700.19  822.73  696.44  878.72  695.28  882.71  695.92
  887.71  702.05  897.71  707.48  948.23  711.31 1013.19  726.32 1075.66  727.06
#Mann= 3 ,-1 , 0
       0     .08       0   308.9    .032       0  897.71     .08       0
Levee=0,,,-1,1045.87,728,,
Bank Sta=308.9,897.71
XS Rating Curve= 0 ,0
Exp/Cntr=0.5,0.3

Type RM Length L Ch R = 1 ,250.4728,263.74,261.23,259.9
BEGIN DESCRIPTION:
Overbank geometry from 2011 City of Columbus LiDAR data.  Channel geometry from 2011 hydrographic survey by Resource International.
END DESCRIPTION:
XS GIS Cut Line= 2
1827597.69976902713189.4370027631826588.06104028713776.602823183
#Sta/Elev= 30
       0   738.7   17.49  736.56   88.69  734.16   98.68  735.78   152.4  735.98
  164.89  732.42  247.33  730.63  278.56   726.6  352.26  726.41  369.75  723.35
  385.99  717.32  399.73   711.8  417.22  708.64 438.949699.0211  475.99  692.95
  512.98   696.3  581.98  693.62  653.98   697.7  728.98  695.48  765.98  697.86
  845.97  696.33   953.1  704.19  959.35  708.07  970.59  716.87  995.57  725.02
 1060.53  726.82  1095.5  726.59 1115.49  724.34 1134.23  719.38 1167.96     719
#Mann= 6 ,-1 , 0
       0     .08       0  278.56     .08       0  385.99     .04       0
  417.22    .032       0  959.35     .06       0 1060.53     .05       0
Levee=0,,,-1,1033.78,727.2,,
#XS Ineff= 2 , 0
       0  210.89  731.25 1033.78       0   727.2
Permanent Ineff=
       F       F
Bank Sta=417.22,959.35
XS Rating Curve= 0 ,0
Exp/Cntr=0.5,0.3

Type RM Length L Ch R = 3 ,250.4469,,,
BEGIN DESCRIPTION:
Rich Street Bridge
Geometry from HEC-RAS model prepared by DLZ and provided by the City of Columbus and from construction plans provided by the City of Columbus, Transportation Division.
END DESCRIPTION:
Bridge Culvert--1,0,-1,-1, 0
Deck Dist Width WeirC Skew NumUp NumDn MinLoCord MaxHiCord MaxSubmerge Is_Ogee
179,60,2.6,0, 52, 53, , , 0.98, 0, 0,0,,
     250   305.4   330.4 355.401   380.4  389.89  389.89  401.64  422.95  423.64
 443.139  462.89  481.64  500.39  501.36 516.139  530.89 543.891  557.01  557.89
  578.39 598.889  619.39  639.64 640.581  654.64  668.89  683.14   697.2 698.139
 718.391  738.89  759.39  779.89  780.77  793.89  806.89  821.64  836.42  837.39
 856.139 874.891  894.64  914.14  914.83  936.14 947.889 947.889  956.52  981.52
 1006.52 1026.52
  728.85  728.63  728.53  728.68  729.06   729.2   729.2  729.55  730.23  730.25
  730.91  731.51  732.04  732.52  732.54  732.88  733.19  733.43  733.65  733.67
  733.96   734.2  734.37  734.48  734.49  734.53  734.55  734.53  734.49  734.48
  734.37   734.2  733.96  733.67  733.65  733.43  733.19  732.88  732.54  732.52
  732.04  731.51  730.91  730.25  730.23  729.48     729     729  728.79  727.91
  726.95  726.18
                                             690  722.75  722.75  720.78  724.46
   726.1  727.09   727.2  726.82  723.12     726  726.94  726.21  723.96  727.76
  729.09  729.78  729.49  728.52  724.79  727.42   728.3  727.42  724.79  728.52
  729.49  729.78  729.09  727.76  723.96  726.21  726.94     726  723.12  726.82
   727.2  727.09   726.1  724.46  720.78  722.75  722.75     690
  275.11 330.509  355.51  380.51  405.51     415     415  426.75  448.06  448.75
  468.25     488  506.75   525.5  526.47  541.25     556     569  582.12     583
   603.5     624   644.5  664.75  665.69  679.75     694  708.25  722.31  723.25
   743.5     764 784.501     805  805.88     819     832  846.75  861.53   862.5
  881.25     900  919.75  939.25 939.939  961.25     973     973  981.63 1006.63
 1031.63 1056.63  1073.9
  728.85  728.63  728.53  728.68  729.06   729.2   729.2  729.55  730.23  730.25
  730.91  731.51  732.04  732.52  732.54  732.88  733.19  733.43  733.65  733.67
  733.96   734.2  734.37  734.48  734.49  734.53  734.55  734.53  734.49  734.48
  734.37   734.2  733.96  733.67  733.65  733.43  733.19  732.88  732.54  732.52
  732.04  731.51  730.91  730.25  730.23  729.48     729     729  728.79  727.91
  726.95  725.99  724.47
                                             690  722.75  722.75  720.78  724.46
   726.1  727.09   727.2  726.82  723.12     726  726.94  726.21  723.96  727.76
  729.09  729.78  729.49  728.52  724.79  727.42   728.3  727.42  724.79  728.52
  729.49  729.78  729.09  727.76  723.96  726.21  726.94     726  723.12  726.82
   727.2  727.09   726.1  724.46  720.78  722.75  722.75     690
Pier Skew, UpSta & Num, DnSta & Num=  ,462.89, 6 ,488, 6 , 3 , 3 , 0 ,,
     6.5     6.5       9       9      13      13
       0   700.9   700.9   705.9   705.9   729.4
     6.5     6.5       9       9      13      13
       0   700.9   700.9   705.9   705.9   729.4
Pier Skew, UpSta & Num, DnSta & Num=  ,598.889, 6 ,624, 6 , 3 , 3 , 0 ,,
     6.5     6.5       9       9      13      13
       0   700.9   700.9   705.9   705.9   729.4
     6.5     6.5       9       9      13      13
       0   700.9   700.9   705.9   705.9   729.4
Pier Skew, UpSta & Num, DnSta & Num=  ,738.89, 6 ,764, 6 , 3 , 3 , 0 ,,
     6.5     6.5       9       9      13      13
       0   700.9   700.9   705.9   705.9   729.4
     6.5     6.5       9       9      13      13
       0   700.9   700.9   705.9   705.9   729.4
Pier Skew, UpSta & Num, DnSta & Num=  ,874.891, 6 ,900, 6 , 3 , 3 , 0 ,,
     6.5     6.5       9       9      13      13
       0   700.9   700.9   705.9   705.9   729.4
     6.5     6.5       9       9      13      13
       0   700.9   700.9   705.9   705.9   729.4
BR Coef=-1 , 1 , 1 ,0.9, 0 ,,,0.8,-1,1.33,1,
WSPro=,,,, 1 ,,,, 0 ,,,, 0 ,,,,-1 ,-1 ,-1 , 0 , 0 , 0 , 0 , 0
BC Design=,, 0 ,, 0 ,,,,,,
BC Use User HTab Curves=0
BC User HTab FreeFlow(D)= 0

Type RM Length L Ch R = 1 ,249.79  ,243.01,240.57,234.78
BEGIN DESCRIPTION:
Overbank geometry from 2011 City of Columbus LiDAR data.  Channel geometry from 2011 hydrographic survey by Resource International.
END DESCRIPTION:
XS GIS Cut Line= 2
1827479.55039902712949.558217436 1826423.3681282713576.107161194
#Sta/Elev= 30
       0  737.17   49.97  737.25    83.7  732.48  136.17  730.53   174.9  732.44
  193.64  732.55   263.6  732.88  276.97 728.613  342.78 728.108  370.13 721.722
  412.47 706.743  426.31 701.188  534.13 691.909  570.12 696.829  603.38 694.116
  637.89 693.844  675.79 697.117  691.11 694.287  720.37 696.757  785.92  696.32
  826.87 693.563  927.28 700.675  935.58 702.907  935.79 707.641  955.96 707.648
  977.31 728.981 1113.02 722.497 1130.59  724.27 1153.08  720.11 1228.04  717.71
#Mann= 6 ,-1 , 0
       0     .06       0    83.7     .05       0   174.9     .06       0
  193.64     .05       0  412.47    .032       0  935.79     .06       0
Levee=0,,,-1,1024.4,726.13,,
#XS Ineff= 2 , 0
       0     405  729.05     983       0  728.74
Permanent Ineff=
       F       F
Bank Sta=412.47,935.79
XS Rating Curve= 0 ,0
Exp/Cntr=0.5,0.3

Type RM Length L Ch R = 1 ,249.76  ,150.75,205.87,256.95
BEGIN DESCRIPTION:
Overbank geometry from 2011 City of Columbus LiDAR data.  Channel geometry from 2011 hydrographic survey by Resource International.
END DESCRIPTION:
XS GIS Cut Line= 2
   1827260.08299   712790.621527   1826337.86075    713358.67715
#Sta/Elev= 30
       0  729.37   32.48  729.06  141.17  722.43  277.34  724.29  304.83  718.82
  327.31  717.53  343.55  712.86  357.71  712.01  363.71  708.26   381.7  701.38
  393.69  698.96  432.65  694.86  484.61  697.74  507.59  696.05  545.56  697.88
  608.51  696.45  658.47  697.59  690.45  694.87  729.42  697.18  803.36  697.88
  818.35  698.97  841.33  708.56  852.32  712.69  890.75  714.69  899.49  720.69
  914.49  726.03  921.98  723.81  956.96  723.33 1036.92   725.2 1083.14  724.08
#Mann= 4 ,-1 , 0
       0     .06       0  141.17     .05       0  363.71    .032       0
  841.33     .05       0
Levee=0,,,-1,929.12,726,,
#XS Ineff= 2 , 0
       0  269.97  724.73  929.12       0     726
Permanent Ineff=
       F       F
Bank Sta=363.71,841.33
XS Rating Curve= 0 ,0
Exp/Cntr=0.5,0.3

Type RM Length L Ch R = 1 ,249.5   ,235.08,249.49,252.77
BEGIN DESCRIPTION:
Overbank geometry from 2011 City of Columbus LiDAR data.  Channel geometry from 2011 hydrographic survey by Resource International.
END DESCRIPTION:
Node Name=AH
XS GIS Cut Line= 3
1827208.42298852712746.5258150991826142.91453844713104.247001041
1826142.90609069 713104.24983719
#Sta/Elev= 30
       0   725.6   95.62  723.25 133.619  726.22 194.922  726.14 243.954  724.44
 254.987  722.38 286.861  712.63 342.028  708.06  357.96  703.71  366.72  699.16
 389.696  698.63 398.531  695.05 424.043  694.99 485.886  697.91 578.159  694.57
 622.332  698.31 643.918  696.24 676.312  695.85 742.081  698.03 786.254  697.24
 815.703  699.77 873.609  701.35 890.002   708.1 893.683  710.69 913.296  710.83
 958.657  723.511029.766  721.941053.286  726.081071.446  721.151103.319  719.15
#Mann= 4 ,-1 , 0
       0     .05       0 342.028    .032       0 890.002     .05       0
1029.766     .06       0
Levee=0,,,-1,1051.32,726.08,,
#XS Ineff= 2 , 0
       0 229.639  725.01 966.929       0  723.66
Permanent Ineff=
       F       F
Bank Sta=342.028,890.002
XS Rating Curve= 0 ,0
Skew Angle= 11
Exp/Cntr=0.5,0.3

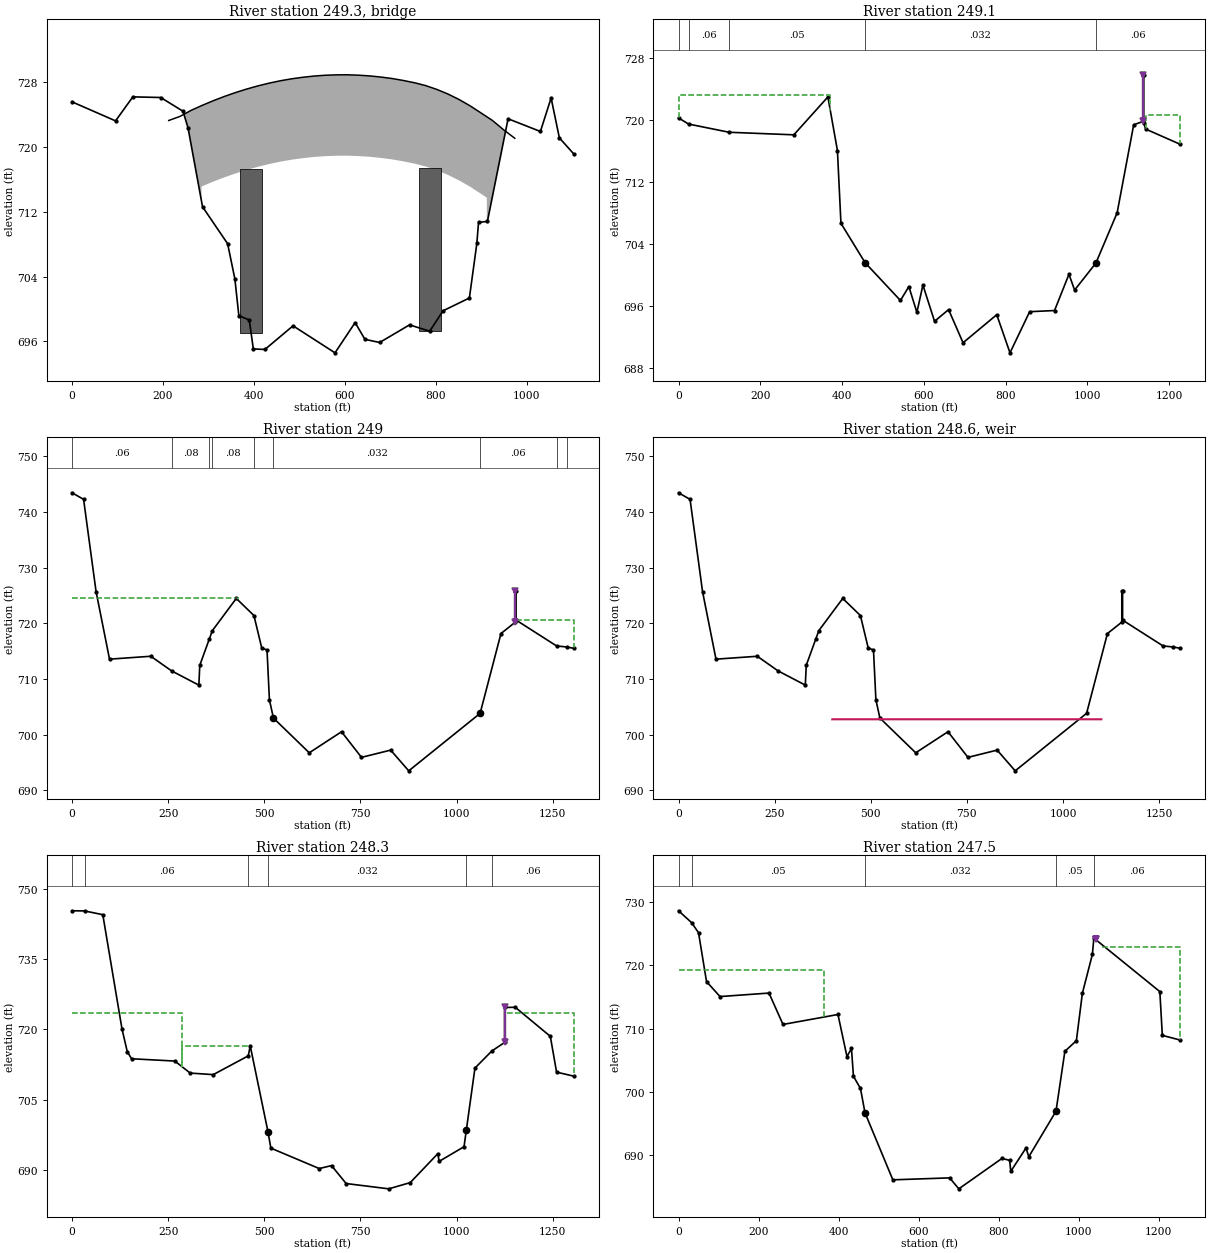
Type RM Length L Ch R = 3 ,249.3   ,,,
BEGIN DESCRIPTION:
Main Street Bridge.
Geometry from construction plans provided by the City of Columbus, Transportation Division.
END DESCRIPTION:
Bridge Culvert--1,0,-1,-1, 0
Deck Dist Width WeirC Skew NumUp NumDn MinLoCord MaxHiCord MaxSubmerge Is_Ogee
55,105,2.6,11, 36, 39, , , 0.98, 0, 0,0,,
 212.618 237.159   261.7 284.639 284.639 286.239  310.78 335.321 359.862 384.207
 408.943 433.484 458.025 482.565 507.106 531.647 556.188 580.727 605.268 629.809
  654.35  678.89 703.431 727.972 752.513 777.054 801.594 826.135 850.675 875.216
 899.756 911.929 911.929 924.297 948.838 973.379
   723.3   723.8  724.55  725.13  725.13  725.17  725.75  726.28  726.76  727.19
  727.58  727.92  728.21  728.45  728.64  728.79  728.89  728.94  728.95   728.9
  728.81  728.67  728.49  728.25  727.97  727.62  727.15  726.58   725.9  725.11
  724.21  723.76  723.76   723.3  722.15   721.1
                             680  715.13  715.17  715.75  716.28  716.76  717.19
  717.58  717.92  718.21  718.45  718.64  718.79  718.89  718.94  718.95   718.9
  718.81  718.67  718.49  718.25  717.97  717.62  717.15  716.58   715.9  715.11
  714.21  713.76     680
 332.762 371.918 396.459     421 443.941 443.941 445.541 470.082 494.622 519.163
 543.507 568.245 592.785 617.326 641.866 666.407 690.947 715.488 740.029  764.57
  789.11 813.651 838.192 862.733 887.274 911.813 936.354 960.895 985.4361009.976
1034.5171059.058 1071.23 1071.231083.5991108.139 1132.681181.7621224.178
   722.5   723.3   723.8  724.55  725.13  725.13  725.17  725.75  726.28  726.76
  727.19  727.58  727.92  728.21  728.45  728.64  728.79  728.89  728.94  728.95
   728.9  728.81  728.67  728.49  728.25  727.97  727.62  727.15  726.58   725.9
  725.11  724.21  723.76  723.76   723.3  722.15   721.1     719  717.19
                                     680  715.13  715.17  715.75  716.28  716.76
  717.19  717.58  717.92  718.21  718.45  718.64  718.79  718.89  718.94  718.95
   718.9  718.81  718.67  718.49  718.25  717.97  717.62  717.15  716.58   715.9
  715.11  714.21  713.76     680
Pier Skew, UpSta & Num, DnSta & Num=  ,393.574, 2 ,562.875, 2 , 0 , 0 , 0 ,,
   48.74   28.24
     680     718
   48.74   28.24
     680     718
Pier Skew, UpSta & Num, DnSta & Num=  ,787.324, 2 ,956.626, 2 , 0 , 0 , 0 ,,
   48.74   28.24
     680     718
   48.74   28.24
     680     718
BR Coef=-1 , 0 , 0 ,1.25, 0 ,,,0.8,-1,2,1,
WSPro=,,,, 1 ,,,, 0 ,,,, 0 ,,,,-1 ,-1 ,-1 , 0 , 0 , 0 , 0 , 0
BC Design=,, 0 ,, 0 ,,,,,,
BC Use User HTab Curves=0
BC User HTab FreeFlow(D)= 0

Type RM Length L Ch R = 1 ,249.1   ,377.23,210.84,63.5
BEGIN DESCRIPTION:
Overbank geometry from 2011 City of Columbus LiDAR data.  Channel geometry from 2011 hydrographic survey by Resource International.
END DESCRIPTION:
XS GIS Cut Line= 3
1827164.48606853712537.8261012731826129.67448986712888.366082609
1826051.02407532713024.735525452
#Sta/Elev= 30
       0  720.27  24.511  719.48 123.793  718.42 281.914  718.09 365.263  722.98
 388.548  716.06 397.127  706.67  456.28  701.58 542.624  696.71 563.228   698.5
 582.861  695.17 597.575   698.7 626.033  694.02  660.38  695.53 695.699  691.25
 778.126  694.87  810.51  689.95  858.59  695.26 919.431  695.41  954.75  700.09
 968.493  698.05  1020.5  701.531072.496  708.021112.969  719.381135.743  719.82
1135.743  725.841137.706  725.841137.706  719.561142.408  718.831227.034  716.86
#Mann= 5 ,-1 , 0
       0     .08       0  24.511     .06       0 123.793     .05       0
  456.28    .032       0  1020.5     .06       0
Levee=0,,,-1,1135.74,725.84,,
#XS Ineff= 2 , 0
       0 371.174  723.281143.997       0  720.62
Permanent Ineff=
       F       F
Bank Sta=456.28,1020.5
XS Rating Curve= 0 ,0
Skew Angle= 11
Exp/Cntr=0.5,0.3

Type RM Length L Ch R = 1 ,249     ,156.71,155.69,155.43
BEGIN DESCRIPTION:
Overbank geometry from 2011 City of Columbus LiDAR data.  Channel geometry from 2011 hydrographic survey by Resource International.
END DESCRIPTION:
XS GIS Cut Line= 4
1826591.64108561 711915.406414361826471.59965903712361.660115018
1826000.89521986713061.0957240161826000.89521986713061.095724017
#Sta/Elev= 30
       0  743.43   29.98  742.25   62.45  725.68   97.42  713.56  204.83  714.08
  258.88711.4537  329.73   708.9  332.22  712.46  356.89717.1614  364.93718.6832
  427.15  724.46  473.07721.3896  493.34  715.57  507.08   715.2  513.33  706.26
  523.74702.9878  616.95  696.75  700.86  700.53   752.8  695.93  828.72  697.23
  875.67  693.51 1061.36  703.83 1115.59  718.16    1153  720.21    1153  725.82
    1155  725.82    1155  720.57 1260.24715.9334 1286.31715.7479 1305.19  715.51
#Mann= 9 ,-1 , 0
       0     .06       0  258.88     .08       0  356.89     .06       0
  364.93     .08       0  473.07     .05       0  523.74    .032       0
 1061.36     .06       0 1260.24     .08       0 1286.31     .06       0
Levee=0,,,-1,1153,725.82,,
#XS Ineff= 2 , 0
       0   430.3  724.51 1156.65       0  720.58
Permanent Ineff=
       F       F
Bank Sta=523.74,1061.36
XS Rating Curve= 0 ,0
Exp/Cntr=0.5,0.3

Type RM Length L Ch R = 5 ,248.6   ,,,
BEGIN DESCRIPTION:
Main Street Dam
Crest elevation from survey performed by Resource International in September 2011.
END DESCRIPTION:
IW Pilot Flow=0
#Inline Weir SE= 2
     400  702.76    1100  702.77
IW Dist,WD,Coef,Skew,MaxSub,Min_El,Is_Ogee,SpillHt,DesHd
50,5,2.6,0,0.98,, 0 ,,,0,0.87,

Type RM Length L Ch R = 1 ,248.3   ,156.94,128.05,104.7
BEGIN DESCRIPTION:
Overbank geometry from 2011 City of Columbus LiDAR data.  Channel geometry from 2011 hydrographic survey by Resource International.
END DESCRIPTION:
XS GIS Cut Line= 4
1826448.43008594711850.4124498521826328.38865936712296.666150525
1825857.68389212712996.1017595231825857.67830347712996.110063883
#Sta/Elev= 30
       0  745.27   32.47  745.24   79.93  744.44  129.89  720.09  143.63  715.25
  154.87  713.76  267.28  713.27  307.25  710.71   367.2  710.38  458.37  714.38
  463.37  716.52  509.58  698.21  517.06  694.73  642.92  690.38  674.89  691.01
  712.84  687.19  823.72  686.06  879.66  687.39  951.59  693.57  954.58   691.9
 1019.51  695.03 1025.42  698.52 1047.91  711.77 1091.62   715.4    1125  717.23
    1125  724.68 1152.82  724.72    1244  718.53 1260.24  710.91  1305.2  710.05
#Mann= 6 ,-1 , 0
       0     .08       0   32.47     .06       0  458.37     .05       0
  509.58    .032       0 1025.42     .04       0 1091.62     .06       0
Levee=0,,,-1,1125,724.68,,
#XS Ineff= 3 ,-1
       0  286.74   723.6  286.74  463.47  716.52 1131.04    1400   723.6
Permanent Ineff=
       F       F       F
Bank Sta=509.58,1025.42
XS Rating Curve= 0 ,0
Exp/Cntr=0.5,0.3

Type RM Length L Ch R = 1 ,247.5   ,235.21,232.14,230.24
BEGIN DESCRIPTION:
Overbank geometry from 2011 City of Columbus LiDAR data.  Channel geometry from 2011 hydrographic survey by Resource International.
END DESCRIPTION:
Node Name=AG
XS GIS Cut Line= 2
1826355.46078369711867.4403029381825786.08287978 712985.35215663
#Sta/Elev= 30
       0   728.6   32.49  726.74   49.98  725.14   69.98  717.43  103.71  715.07
  226.17  715.62  261.16  710.67  398.61  712.24  421.11   705.6  432.35  706.88
  437.35  702.49  454.84  700.58  466.16  696.74  535.82  686.16  677.77  686.47
  700.76  684.74  808.72  689.54  827.71  689.23  830.71   687.5   868.7  691.18
   875.7   689.8  943.67  696.97  965.92  706.44  994.66   708.1 1009.65  715.58
 1034.64  721.71 1038.39  724.29 1203.33  715.85 1209.58  708.95 1254.56   708.2
#Mann= 5 ,-1 , 0
       0     .08       0   32.49     .05       0  466.16    .032       0
  943.67     .05       0 1038.39     .06       0
Levee=0,,,-1,1042.49,724.2,,
#XS Ineff= 2 , 0
       0  362.95  719.22 1058.93       0  722.94
Permanent Ineff=
       F       F
Bank Sta=466.16,943.67
XS Rating Curve= 0 ,0
Exp/Cntr=0.5,0.3