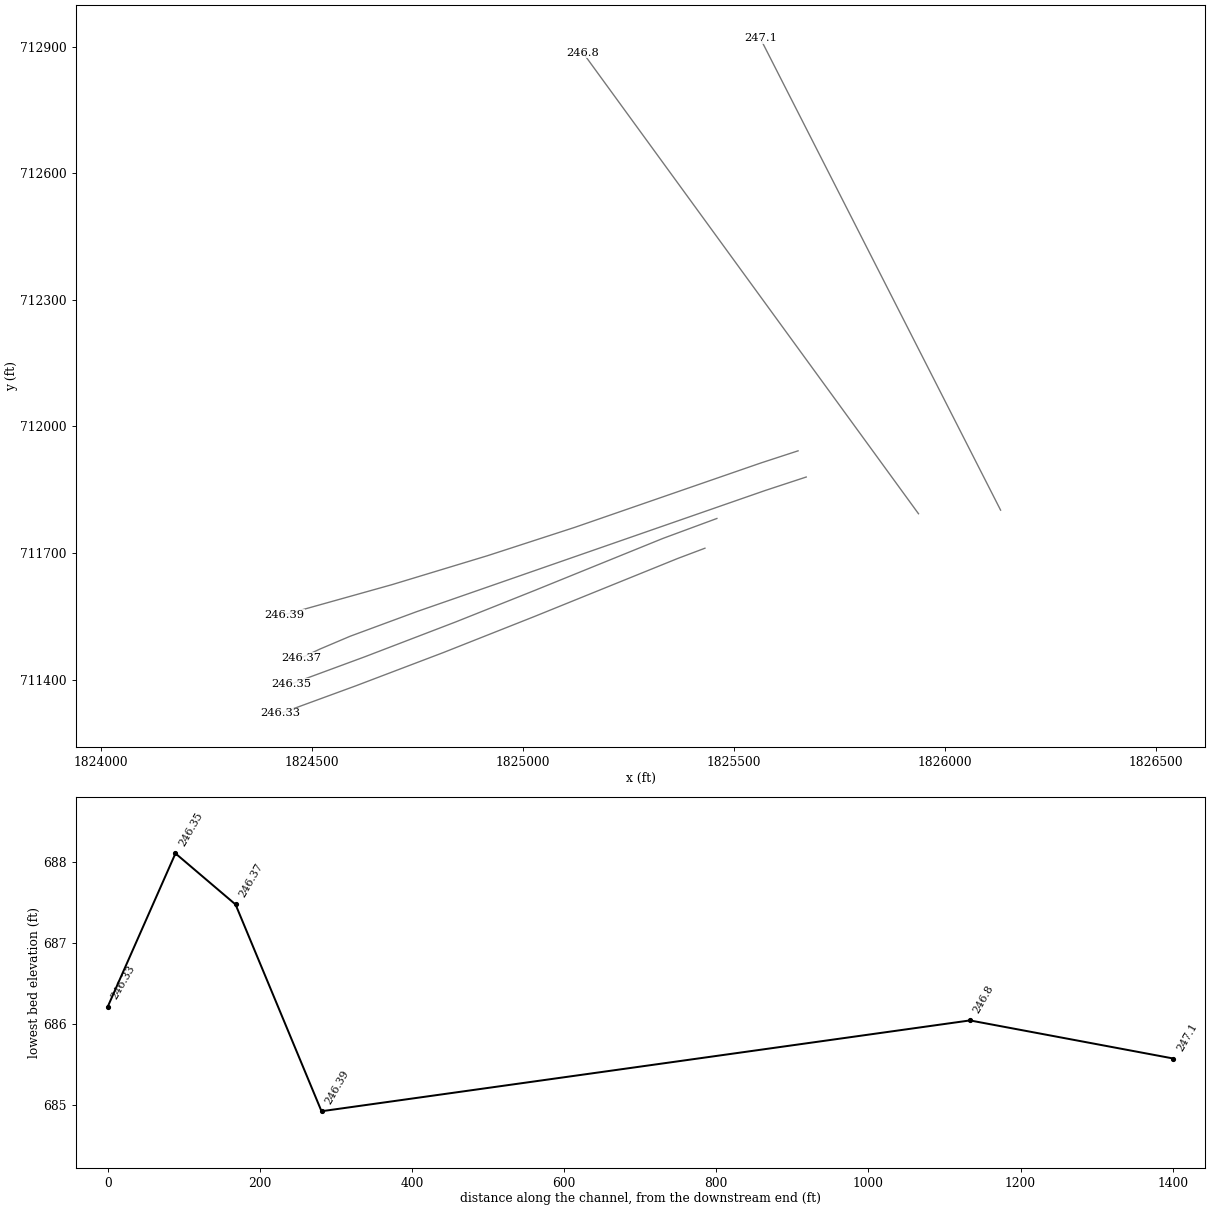
HEC-RAS study FRA-70-1321R.prj: FRA-70-1321R

--- FRA-70-1321R.g11 (geometry) --- (continued)

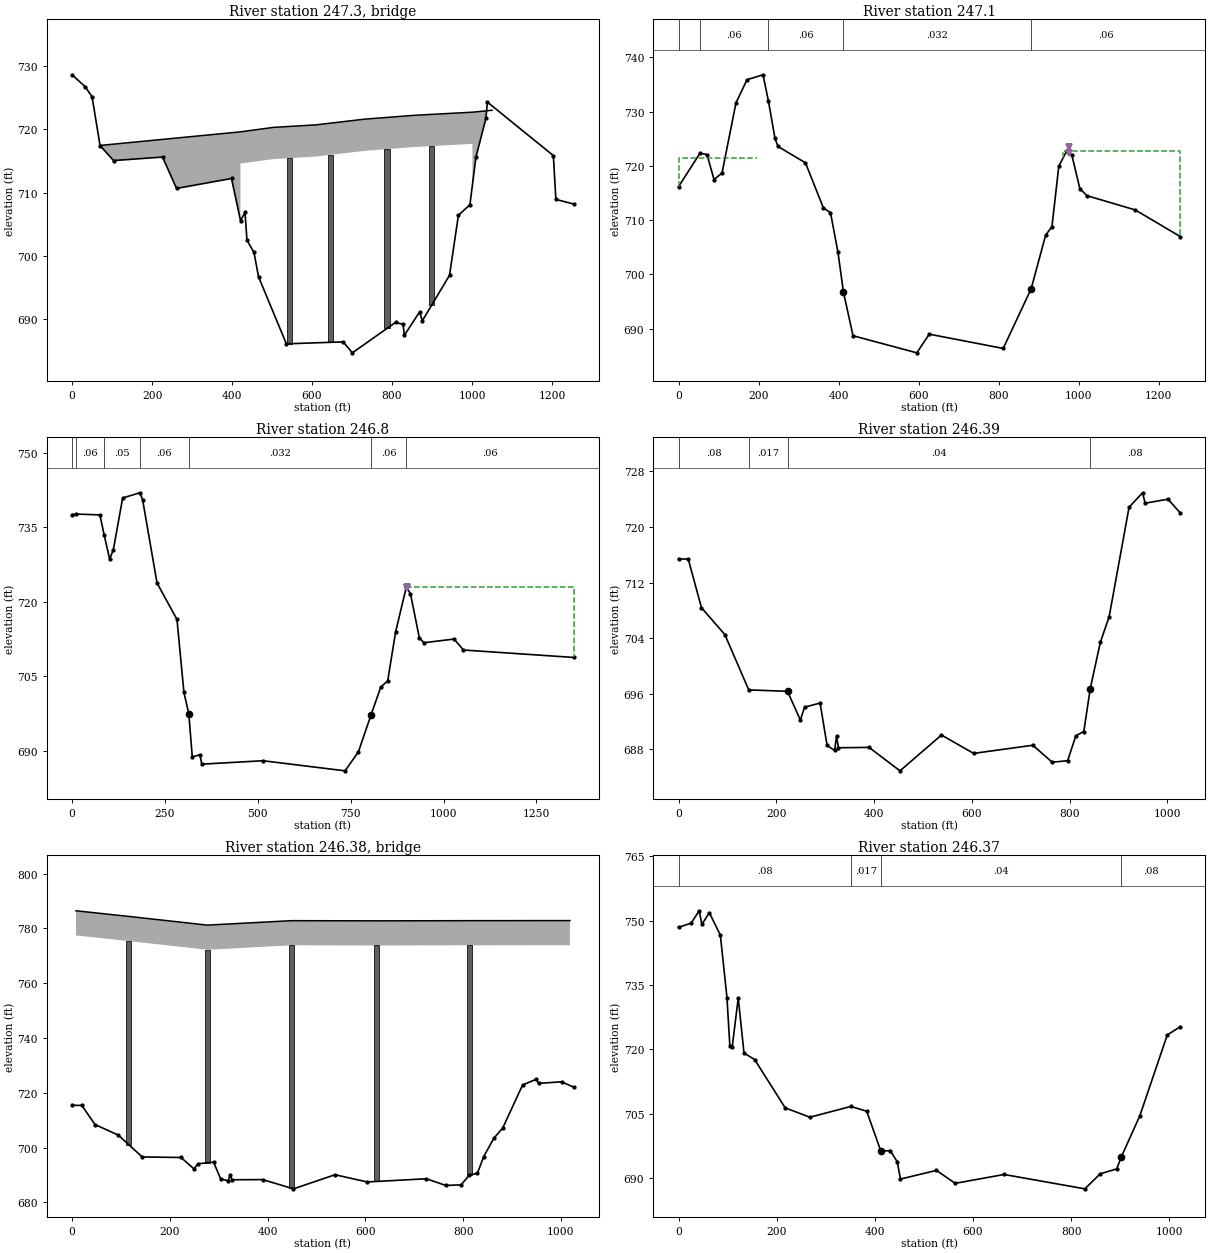
Type RM Length L Ch R = 3 ,247.3   ,,,
BEGIN DESCRIPTION:
Norfolk Southern / CSX Shared Railroad Bridge
Geometry from plans provided by Norfolk Southern.  Top chord elevations adjusted using 2011 City of Columbus LiDAR data.
END DESCRIPTION:
Bridge Culvert--1,0,-1,-1, 0
Deck Dist Width WeirC Skew NumUp NumDn MinLoCord MaxHiCord MaxSubmerge Is_Ogee
58,70,2.6,0, 10, 10, , , 0.98, 0, 0,0,,
   74.32  420.95  420.95  503.09  609.09  731.42  853.75 1000.93 1000.93    1050
  717.48   719.6   719.6   720.3   720.7   721.6   722.2   722.7   722.7     723
             680   714.6   715.3   715.7   716.6   717.2   717.7     680
     300  377.68  377.68   457.3   563.3  685.63  807.96  959.11  959.11  976.83
   718.9   719.6   719.6   720.3   720.7   721.6   722.2   722.7   722.7  722.89
             680   714.6   715.3   715.7   716.6   717.2   717.7     680
Pier Skew, UpSta & Num, DnSta & Num=  ,543, 6 ,499.73, 6 , 0 , 0 , 0 ,,
   12.92   12.92   10.92   10.92    8.92    8.17
     683     688     688     694     694   715.5
   12.92   12.92   10.92   10.92    8.92    8.17
     683     688     688     694     694   715.5
Pier Skew, UpSta & Num, DnSta & Num=  ,647.12, 6 ,603.85, 6 , 0 , 0 , 0 ,,
   12.92   12.92   10.92   10.92    8.92    8.17
     683     688     688     694     694   715.9
   12.92   12.92   10.92   10.92    8.92    8.17
     683     688     688     694     694   715.9
Pier Skew, UpSta & Num, DnSta & Num=  ,787.58, 6 ,744.31, 6 , 0 , 0 , 0 ,,
   12.92   12.92   10.92   10.92    8.92    8.17
     683     688     688     694     694   716.9
   12.92   12.92   10.92   10.92    8.92    8.17
     683     688     688     694     694   716.9
Pier Skew, UpSta & Num, DnSta & Num=  ,899.28, 6 ,856.01, 6 , 0 , 0 , 0 ,,
   12.92   12.92   10.92   10.92    8.92    8.17
     683     688     688     694     694   717.4
   12.92   12.92   10.92   10.92    8.92    8.17
     683     688     688     694     694   717.4
BR Coef=-1 , 1 , 1 ,1.25, 0 ,,,0.8,-1,2,1,
WSPro=,,,, 1 ,,,, 0 ,,,, 0 ,,,,-1 ,-1 ,-1 , 0 , 0 , 0 , 0 , 0
BC Design=,, 0 ,, 0 ,,,,,,
BC Use User HTab Curves=0
BC User HTab FreeFlow(D)= 0

Type RM Length L Ch R = 1 ,247.1   ,230.39,267.48,301.97
BEGIN DESCRIPTION:
Overbank geometry from 2011 City of Columbus LiDAR data.  Channel geometry from 2011 hydrographic survey by Resource International.
END DESCRIPTION:
XS GIS Cut Line= 2
   1826130.98354   711801.668453   1825561.60115   712919.589117
#Sta/Elev= 30
       0  716.18   53.73  722.34   71.23  722.08   88.72  717.49  108.71  718.68
   143.7  731.63  171.19  735.87  211.18  736.78  224.92  731.88  241.17  725.05
  248.66  723.58  317.39  720.56  362.38  712.22  379.87   711.4  398.61   704.1
  412.36  696.74  436.27  688.72   595.8  685.57  626.78  689.01  811.72  686.38
  881.69  697.38  917.68  707.21  933.67  708.83  950.67  719.93  970.92  722.82
  983.41  721.96  1003.4  715.82  1020.9  714.52  1142.1  711.88 1254.56  706.98
#Mann= 5 ,-1 , 0
       0     .08       0   53.73     .06       0  224.92     .06       0
  412.36    .032       0  881.69     .06       0
Levee=0,,,-1,976.83,723.55,,
#XS Ineff= 3 ,-1
       0  196.12  721.42  196.12  320.32  719.21  961.02    1253  722.83
Permanent Ineff=
       F       F       F
Bank Sta=412.36,881.69
XS Rating Curve= 0 ,0
Exp/Cntr=0.5,0.3

Type RM Length L Ch R = 1 ,246.8   ,188.11,852.52,1437.03
BEGIN DESCRIPTION:
Overbank geometry from 2011 City of Columbus LiDAR data.  Channel geometry from 2011 hydrographic survey by Resource International.
END DESCRIPTION:
XS GIS Cut Line= 2
1825936.45013878711793.1277875161825141.63412822712885.105043387
#Sta/Elev= 30
       0  737.51   11.24  737.63   74.97  737.47   86.21  733.48   101.2  728.58
   111.2   730.5  136.19  740.87  182.42  741.91  189.91  740.51  228.64  723.78
  282.37  716.46  301.11  701.79  314.18  697.53  323.54  688.85  344.25  689.27
  349.11  687.38  513.86  688.07  734.79  686.04  770.78  689.87  804.13  697.16
  830.86  702.86   849.6  704.14  870.84  713.96  899.57  722.93  910.82  721.62
  934.56  712.82  947.05  711.78 1028.26  712.52 1053.25  710.32 1350.61  708.82
#Mann= 7 ,-1 , 0
       0     .08       0   11.24     .06       0   86.21     .05       0
  182.42     .06       0  314.18    .032       0  804.13     .06       0
  899.57     .06       0
Levee=0,,,-1,900.46,723.02,,
#XS Ineff= 2 , 0
       0                  900.46       0  723.04
Permanent Ineff=
       F       F
Bank Sta=314.18,804.13
XS Rating Curve= 0 ,0
Exp/Cntr=0.5,0.3

Type RM Length L Ch R = 1 ,246.39  ,65,113,110
XS GIS Cut Line= 6
      1825651.07       711942.18      1825563.07       711913.46
      1825121.78       711760.79      1824915.38       711693.74
       1824688.8       711625.07      1824434.68       711553.99
#Sta/Elev= 30
       0  715.42   19.96  715.36  46.921  708.38  94.743  704.52 143.617  696.56
  222.95  696.36 249.252  692.22 257.877  694.07  289.63  694.67 303.898  688.58
   319.3  687.85 323.279   689.9 327.138  688.24 389.854  688.29 453.046  684.92
 537.965  690.07 603.801  687.43 724.854   688.6 764.524  686.16   796.1  686.38
 812.908  689.97 829.194  690.57 842.289  696.71 862.964  703.39 881.027  707.08
 921.815  722.83 949.411  724.91 954.668  723.411001.477  723.991026.678     722
#Mann= 4 ,-1 , 0
       0     .08       0 143.617    .017       0  222.95     .04       0
 842.289     .08       0
Bank Sta=222.95,842.289
XS Rating Curve= 0 ,0
Skew Angle= 36.5
Exp/Cntr=0.3,0.1

Type RM Length L Ch R = 3 ,246.38  ,,,
BEGIN DESCRIPTION:
FRA-71-1503L I-71-SB
END DESCRIPTION:
Bridge Culvert--1,0,-1,-1, 0
Deck Dist Width WeirC Skew NumUp NumDn MinLoCord MaxHiCord MaxSubmerge Is_Ogee
1,109.5,2.6,36.5, 7, 7, , , 0.98, 0, 0,0,,
   8.033 116.043 276.814 448.985 623.473  813.821018.628
  786.41 784.353781.1778 782.801 782.738 782.801 782.829
  777.41 775.353772.1778 773.801 773.738 773.801 773.829
   8.045   166.6 327.372 500.092 678.103 877.1071014.403
  783.71 782.498 780.225 777.985 777.566779.2638781.5989
  774.71 773.498 771.225 768.985 768.566770.2639772.5989
Pier Skew, UpSta & Num, DnSta & Num=  ,116.043, 6 ,166.6, 6 , 0 , 0 , 0 ,,
      10      10      10      10       8       8
     650     693   695.2   700.2   700.2 775.353
      10      10      10      10       8       8
     650     693   695.2   700.2   700.2 773.498
Pier Skew, UpSta & Num, DnSta & Num=  ,276.814, 6 ,327.372, 6 , 0 , 0 , 0 ,,
      10      10      10      10       8       8
     650     693   695.2   700.2   700.2 772.178
      10      10      10      10       8       8
     650     693   695.2   700.2   700.2 771.225
Pier Skew, UpSta & Num, DnSta & Num=  ,448.985, 6 ,500.092, 6 , 0 , 0 , 0 ,,
      10      10      10      10       8       8
     650     693   695.2   700.2   700.2 773.801
      10      10      10      10       8       8
     650     693   695.2   700.2   700.2 768.985
Pier Skew, UpSta & Num, DnSta & Num=  ,623.473, 6 ,678.103, 6 , 0 , 0 , 0 ,,
      10      10      10      10       8       8
     650     693   695.2   700.2   700.2 773.738
      10      10      10      10       8       8
     650     693   695.2   700.2   700.2 768.566
Pier Skew, UpSta & Num, DnSta & Num=  ,813.82, 6 ,877.107, 6 , 0 , 0 , 0 ,,
      10      10      10      10       8       8
     650     693   695.2   700.2   700.2 773.801
      10      10      10      10       8       8
     650     693   695.2   700.2   700.2 770.264
BR Coef=-1 , 0 , 0 ,, 0 ,,,0.8,-1,,0,
WSPro=,,,, 1 ,,,, 0 ,,,, 0 ,,,,-1 ,-1 ,-1 , 0 , 0 , 0 , 0 , 0
BC Design=,, 0 ,, 0 ,,,,,,
BC Use User HTab Curves=0
BC User HTab FreeFlow(D)= 0

Type RM Length L Ch R = 1 ,246.37  ,25,79,66
XS GIS Cut Line= 6
      1825670.41       711880.14       1825573.3       711848.23
       1824747.1       711560.98      1824589.71       711502.83
       1824517.5       711472.18      1824473.41       711451.37
#Sta/Elev= 30
       0  748.46  25.699  749.43  41.961  752.32  47.717  749.15  62.741  751.88
  85.185  746.65  98.681  732.08 104.542  720.79 109.389  720.57  121.64  731.96
   133.4  719.15 155.152  717.61 217.339  706.36 267.564  704.17  351.02  706.68
 383.391  705.58 412.186  696.29 431.277  696.37 445.634  693.79 452.202  689.75
 525.626  691.77 563.648  688.75 663.286  690.82 827.948  687.47 858.977  690.96
 892.924  692.13 902.249  694.92 940.038  704.53 995.898  723.371022.458  725.29
#Mann= 4 ,-1 , 0
       0     .08       0  351.02    .017       0 412.186     .04       0
 902.249     .08       0
Bank Sta=412.186,902.249
XS Rating Curve= 0 ,0
Skew Angle= 36.5
Exp/Cntr=0.3,0.1

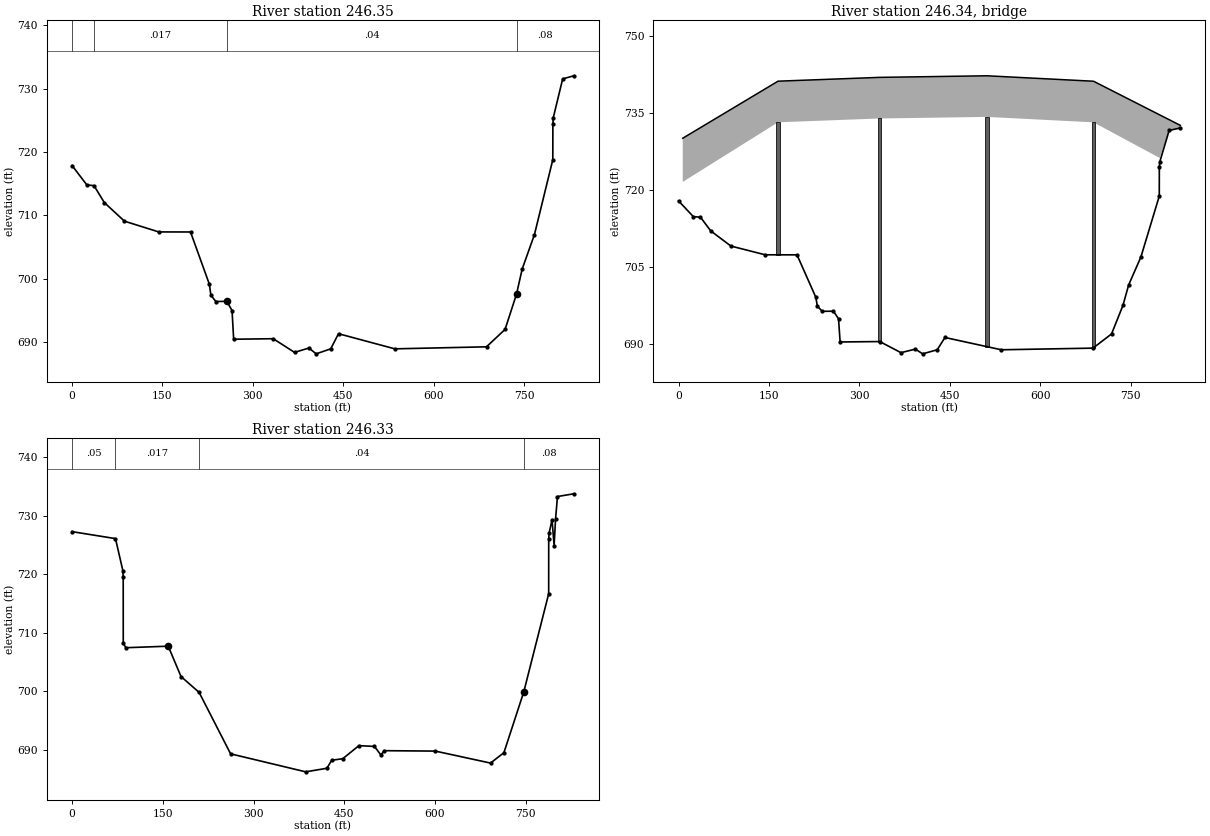
Type RM Length L Ch R = 1 ,246.35  ,76,89,68
XS GIS Cut Line= 6
      1825458.76       711781.91      1825331.26        711734.8
      1825027.19       711611.44      1824839.22       711536.51
      1824624.49       711454.18      1824449.47       711389.63
#Sta/Elev= 30
       0  717.86  24.534   714.8   36.42  714.68  53.519  712.01  86.895  709.07
 143.781  707.37 196.562  707.36 227.816   699.1 230.337  697.38 238.495  696.37
 256.947   696.4  265.45  694.93 268.126  690.41 333.808  690.49 369.106  688.33
 393.001  689.02 404.995   688.1 429.183  688.89 442.092  691.28 535.521  688.89
 687.698  689.21 718.498  691.97 737.465  697.54 746.891  701.51  767.22  706.95
 797.689  718.79 797.789  724.38 798.458  725.42 814.065  731.56 832.617  732.05
#Mann= 4 ,-1 , 0
       0     .08       0   36.42    .017       0 256.947     .04       0
 737.465     .08       0
Bank Sta=256.947,737.465
XS Rating Curve= 0 ,0
Skew Angle= 39.75
Exp/Cntr=0.3,0.1

Type RM Length L Ch R = 3 ,246.34  ,,,
BEGIN DESCRIPTION:
FRA-70-1323C Ramp D3
END DESCRIPTION:
Bridge Culvert--1,0,-1,-1, 0
Deck Dist Width WeirC Skew NumUp NumDn MinLoCord MaxHiCord MaxSubmerge Is_Ogee
1,86,2.6,39.75, 6, 6, , , 0.98, 0, 0,0,,
   6.995 165.108 333.036 511.631 688.573 832.614
  730.05  741.15  741.89   742.2  741.14 732.552
  721.55  733.15  733.89   734.2  733.14 724.052
   8.417 168.227 336.115 514.121 684.263  822.43
  729.98  741.15  741.89   742.2  741.14 734.306
  721.48  733.15  733.89   734.2  733.14 725.806
Pier Skew, UpSta & Num, DnSta & Num=  ,165.108, 4 ,168.227, 4 , 0 , 0 , 0 ,,
     5.5     5.5       5       5
     648   697.2   697.2  733.15
     5.5     5.5       5       5
     648   697.2   697.2  733.15
Pier Skew, UpSta & Num, DnSta & Num=  ,333.036, 4 ,336.115, 4 , 0 , 0 , 0 ,,
     5.5     5.5       5       5
   648.5   697.2   697.2  733.89
     5.5     5.5       5       5
   648.5   697.2   697.2  733.89
Pier Skew, UpSta & Num, DnSta & Num=  ,511.631, 4 ,514.121, 4 , 0 , 0 , 0 ,,
     5.5     5.5       5       4
     645   697.2   697.2   734.2
       5       5     4.5     4.5
     645   697.2   697.2   734.2
Pier Skew, UpSta & Num, DnSta & Num=  ,688.573, 4 ,684.263, 4 , 0 , 0 , 0 ,,
     5.5     5.5       5       5
   635.5   697.2   697.2  733.14
     5.5     5.5       5       5
   635.5   697.2   697.2  733.14
BR Coef=-1 , 0 , 0 ,, 0 ,,,0.8,-1,,0,
WSPro=,,,, 1 ,,,, 0 ,,,, 0 ,,,,-1 ,-1 ,-1 , 0 , 0 , 0 , 0 , 0
BC Design=,, 0 ,, 0 ,,,,,,
BC Use User HTab Curves=0
BC User HTab FreeFlow(D)= 0

Type RM Length L Ch R = 1 ,246.33  ,1.5,5,21.5
XS GIS Cut Line= 6
      1825430.43       711711.43      1825366.18       711687.23
      1825025.53       711549.27      1824810.24       711464.05
      1824603.22       711385.38        1824425.       711320.09
#Sta/Elev= 30
       0  727.31  71.764  726.12  83.958  720.65  84.542  719.57  84.642   708.2
   89.04  707.45 158.981  707.71 180.117  702.52 210.071   699.8 262.106  689.29
 386.243  686.21 421.302  686.82 429.229  688.19 447.581  688.46 474.145  690.69
 499.924  690.56 510.511   689.1 516.123  689.83 600.542  689.76 691.819  687.71
 713.946  689.49 746.715  699.87 787.948  716.68 788.009  726.03 788.593  727.02
 793.506  729.35 796.935  724.92 799.311  729.45 802.471  733.32  829.58  733.79
#Mann= 4 ,-1 , 0
       0     .05       0  71.764    .017       0 210.071     .04       0
 746.715     .08       0
Bank Sta=158.981,746.715
XS Rating Curve= 0 ,0
Skew Angle= 39.75
Exp/Cntr=0.3,0.1